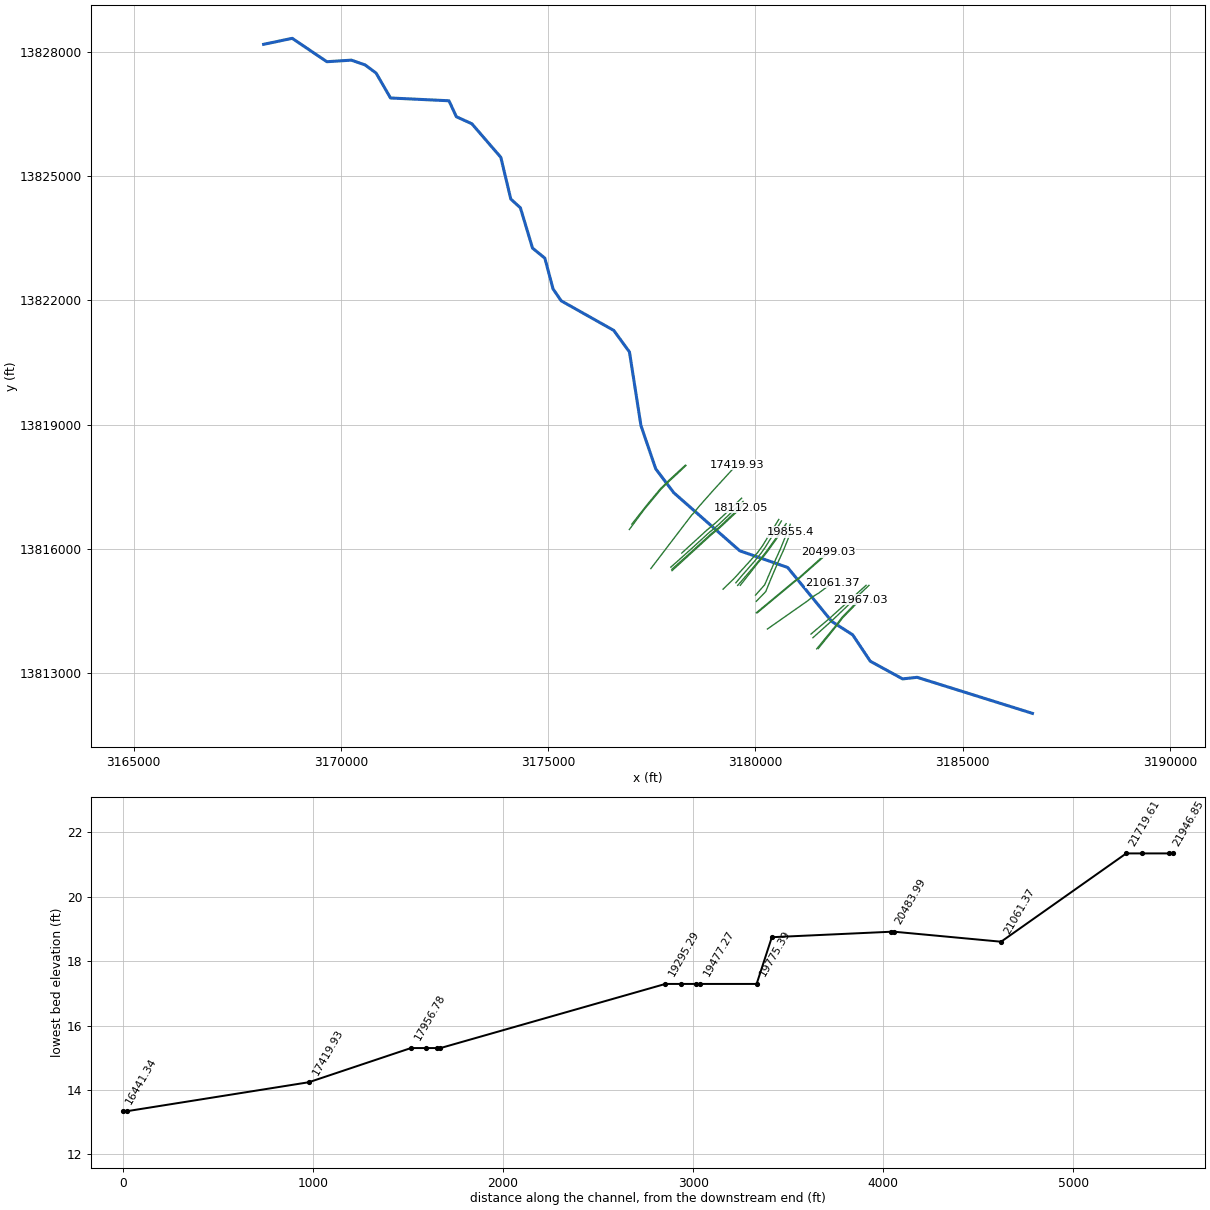
--- I101-00-00.prj (project) ---

Proj Title=I101-00-00
Current Plan=p03
Default Exp/Contr=.3,.1
English Units
Geom File=g03
Geom File=g02
Flow File=f03
Flow File=f01
Plan File=p03
Plan File=p01
Y Axis Title=Elevation
X Axis Title(PF)=Main Channel Distance
X Axis Title(XS)=Station
BEGIN DESCRIPTION:
Vince Basin
Little Vince Bayou
I101-00-00
Flood Hazard Model
10, 2, 1 & 0.2% Events
Filename: I101_00_00.prj
Prepared by: Perry Vaught	Date: 06-01-04
Reviewed by: __________	Date:
Status: (FINAL)
END DESCRIPTION:
DSS Export Rating Curves= 0
DSS Export Rating Curve Sorted= 0
DSS Export Volume Flow Curves= 0
DXF OffsetX= 0
DXF OffsetY= 0
DXF ScaleX= 1
DXF ScaleY= 10

--- I101-00-00.p03 (plan) ---

Plan Title=Floodway
Version=Version 3.0.1  Mar 2001
Short Identifier=Floodway0607
Geom File=g03
Flow File=f03
Subcritical Flow
K Sum by GR= 0
Std Step Tol= 0.003
Critical Tol= 0.003
Num of Std Step Trials= 20
Max Error Tol= 0.1
Flow Tol Ratio= 0.001
Split Flow NTrial= 30
Split Flow Tol= 0.02
Split Flow Ratio= 0.02
Log Output Level= 0
Friction Slope Method= 0
Unsteady Friction Slope Method= 2
Secant Critical Depth
Global Vel Dist= 0 , 0 , 0
Global Log Level= 0
CheckData=True
Encroach Param=-1 ,0,0, 2
Encroach River=I101-00-00
Encroach Reach=I101-00-00_0002
Encroach Node=21967.03
       1  4978.8  5022.7
Encroach Node=21946.85
       1 4979.51 5015.83
Encroach Node=21873
       1 4979.45 5015.83
Encroach Node=21800.05
       1 4979.45 5015.77
Encroach Node=21719.61
       1  4947.7  5028.2
Encroach Node=21061.37
       1 4952.54 5037.46
Encroach Node=20499.03
       1 4957.17 5018.95
Encroach Node=20483.99
       1 4957.71 5018.95
Encroach Node=20169
       1 4921.57 5048.43
Encroach Node=19855.4
       1 4921.57 5048.43
Encroach Node=19775.39
       1    4960 5033.07
Encroach Node=19477.27
       1 4966.93 5033.07
Encroach Node=19456.34
       1 4966.93 5033.07
Encroach Node=19416
       1 4966.93 5033.07
Encroach Node=19377.44
       1 4966.93 5033.07
Encroach Node=19295.29
       1 4966.93 5033.07
Encroach Node=18112.05
       1 4958.68 5041.32
Encroach Node=18091.96
       1 4958.68 5041.32
Encroach Node=18063
       1 4958.68 5041.32
Encroach Node=18036.95
       1 4958.68 5041.32
Encroach Node=17956.78
       1 4958.68 5041.32
Encroach Node=17419.93
       1 4967.95 5032.05
Encroach Node=16461.61
       1    4959    5041
Encroach Node=16441.34
       1 4966.55 5033.45
Encroach Node=16408
       1 4966.55 5033.45
Encroach Node=16375.47
       1 4966.55 5033.45
Encroach Node=16294.47
       1    4959 5033.45
Encroach Node=15849.67
       1 4966.54 5033.46
Encroach Node=15711.66
       1 4966.22 5033.78
Encroach Node=15691.2
       1 4966.22 5033.78
Encroach Node=15662
       1 4966.22 5033.78
Encroach Node=15634.38
       1 4966.22 5033.78
Encroach Node=15551.22
       1 4966.22    5038
Encroach Node=15283.37
       1 4954.42 5045.58
Encroach Node=15261.69
       1 4954.42 5045.58
Encroach Node=15220
       1 4954.42 5045.58
Encroach Node=15180.67
       1 4954.42 5045.58
Encroach Node=15094.52
       1 4954.42    5060
Encroach Node=14349.11
       1  4950.2  5049.8
Encroach Node=13615.84
       1    4960    5043
Encroach Node=13595.84
       1 4965.68 5034.32
Encroach Node=13562
       1 4965.68 5034.32
Encroach Node=13530.83
       1 4965.68 5034.32
Encroach Node=13450.83
       1    4954    5051
Encroach Node=12660.89
       1 4965.17    5028
Encroach Node=12640.88
       1 4965.17 5034.83
Encroach Node=12602
       1 4965.17 5034.83
Encroach Node=12565.83
       1 4965.17 5034.83
Encroach Node=12484.03
       1 4965.17 5034.83
Encroach Node=11752.27
       1 4965.49 5034.52
Encroach Node=11732.27
       1 4964.91  5035.1
Encroach Node=11719
       1 4964.91  5035.1
Encroach Node=11707.26
       1 4964.93 5035.07
Encroach Node=11627.26
       1    4965 5035.01
Encroach Node=10635.42
       1 4952.16 5047.84
Encroach Node=10614.46
       1 4952.16 5047.84
Encroach Node=10579
       1 4946.84 5047.84
Encroach Node=10544.14
       1 4946.84 5043.16
Encroach Node=10464.1
       1 4951.84 5048.16
Encroach Node=9878.991
       1    4911 5055.81
Encroach Node=9145.984
       1 4947.16 5042.84
Encroach Node=9125.983
       1 4952.16 5047.84
Encroach Node=9088
       1 4952.16 5047.84
Encroach Node=9052.804
       1 4947.16 5042.84
Encroach Node=8972.667
       1 4952.16 5047.84
Encroach Node=8328.821
       1 4957.31 5042.69
Encroach Node=8305.976
       1 4957.31 5042.69
Encroach Node=8258
       1    4957    5052
Encroach Node=8212.45
       1 4957.31    5052
Encroach Node=8029.999
       1 4957.31 5042.69
Encroach Node=7678.89
       1 4943.07 5056.93
Encroach Node=7658.071
       1 4943.07 5056.93
Encroach Node=7621
       1 4943.07 5056.93
Encroach Node=7585.936
       1 4943.07 5056.93
Encroach Node=7503.557
       1 4943.07 5056.93
Encroach Node=6999.813
       1 4943.09 5056.91
Encroach Node=6977.161
       1 4943.09 5056.91
Encroach Node=6931
       1 4943.09 5056.91
Encroach Node=6886.71
       1 4943.09 5056.91
Encroach Node=6795.392
       1 4943.09 5056.91
Encroach Node=6679.12
       1 4932.02 5087.98
Encroach Node=6654.895
       1 4945.91 5074.09
Encroach Node=6474
       1 4945.91 5074.09
Encroach Node=6294.895
       1 4945.91 5074.09
Encroach Node=6155.104
       1 4931.68 5068.32
Encroach Node=6130.177
       1 4931.68 5068.32
Encroach Node=6075
       1 4931.68 5068.32
Encroach Node=6021.246
       1 4931.68 5068.32
Encroach Node=5754.045
       1 4947.16 5052.84
Encroach Node=5732.308
       1 4947.16 5052.84
Encroach Node=5694
       1 4947.16 5052.84
Encroach Node=5657.445
       1 4947.16 5052.84
Encroach Node=5576.476
       1 4942.16 5047.84
Encroach Node=5335.797
       1 4966.06 5033.94
Encroach Node=4030.521
       1 4938.48 5061.52
Encroach Node=4010.506
       1 4938.48 5061.52
Encroach Node=3978
       1 4938.48 5061.52
Encroach Node=3947.031
       1 4938.48 5061.52
Encroach Node=3866.9
       1 4938.48 5061.52
Encroach Node=3158.447
       1    4920    5139
Encroach Node=3141
       1    4900    5120
Encroach Node=3124.185
       1 4921.61    5100
Encroach Node=3101.083
       1 4921.61 5078.39
Encroach Node=3069
       1 4909.31  5090.7
Encroach Node=3038.584
       1    4897 5078.39
Encroach Node=3028.045
       1    4918    5103
Encroach Node=3008
       1    4918    5103
Encroach Node=2988.153
       1 4921.61    5058
Encroach Node=2927.186
       1 4949.79 5050.21
Encroach Node=2881
       1 4949.79 5050.21
Encroach Node=2835.781
       1 4949.79 5050.21
Encroach Node=2737.14
       1    4900    5170
Encroach Node=2536.894
       1 4943.84 5056.16
Encroach Node=2516.65
       1 4943.84 5056.16
Encroach Node=2473
       1 4943.84 5056.16
Encroach Node=2430.546
       1 4943.84 5056.16
Encroach Node=2346.33
       1  4932.1  5137.9
Encroach Node=2323
       1  4932.1  5137.9
Encroach Node=2300.226
       1  4927.1  5132.9
Encroach Node=1822.68
       1  4918.5  5165.5
Encroach Node=1817
       1  4918.5  5165.5
Encroach Node=1812.292
       1    4922    5169
Encroach Node=1407.221
       1  4945.1  5054.9
Encroach Node=1397.221
       1  4945.1  5054.9
Encroach Node=1375
       1  4945.1  5054.9
Encroach Node=1354.027
       1  4945.1  5054.9
Encroach Node=1313.987
       1  4945.1  5054.9
Encroach Node=1117.683
       1 4903.78 5096.22
Encroach Node=1091.049
       1 4903.78 5096.22
Encroach Node=1065
       1 4903.78 5096.22
Encroach Node=1039.716
       1 4903.78 5096.22
Encroach Node=944.518
       1 4903.78 5096.22
Encroach Node=813.601
       1 4907.67 5092.33
Encroach Node=789.832
       1 4907.67 5092.33
Encroach Node=754
       1 4907.67 5092.33
Encroach Node=719.211
       1 4907.67 5092.33
Encroach Node=638.642
       1    4931 5092.33
Encroach Node=241.471
       1 4890.86 5109.14
Computation Interval=1HOUR
Output Interval=1HOUR
Run HTab= 0
Run UNet= 0
Run PostProcess= 0
UNET Theta= 1
UNET ZTol= 0.02
UNET ZSATol= 0.1
UNET MxIter= 20
UNET MaxInSteps= 20
UNET DtIC= 0
UNET DtMin= 0
UNET MaxCRTS= 20
UNET WFStab= 2
UNET SFStab= 1
UNET WFX= 1
UNET SFX= 1
UNET Convert EG Bridges=-1
UNET Use Existing IB Tables=-1
Instantaneous Interval=1HOUR
Write IC File= 0
IC Time=0
Write Velocity= 0
Write Detailed= 0

--- I101-00-00.p01 (plan) ---

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Plan Title=FEMA Effective June 2007
Short Identifier=FEMAeff0607
Geom File=g02
Flow File=f01
Std Step Tol= 0.01
Critical Tol= 0.01
Max Error Tol= 0.3
Encroach Param=-1 ,0,0, 0

--- I101-00-00.f03 (steady flow) ---

Flow Title=Floodway
Version=Version 3.0.1  Mar 2001
Number of Profiles= 2
Profile Names=1PCT_100yr, 1PCTFloodway_100yrFW
River Rch & RM=I101-00-00,I101-00-00_0002      ,21967.03
     790     790
River Rch & RM=I101-00-00,I101-00-00_0002      ,21719.61
     876     876
River Rch & RM=I101-00-00,I101-00-00_0002      ,21061.37
     956     956
River Rch & RM=I101-00-00,I101-00-00_0002      ,20499.03
    1057    1057
River Rch & RM=I101-00-00,I101-00-00_0002      ,19855.4
    1071    1071
River Rch & RM=I101-00-00,I101-00-00_0002      ,19477.27
    1125    1125
River Rch & RM=I101-00-00,I101-00-00_0002      ,19456.34
    1154    1154
River Rch & RM=I101-00-00,I101-00-00_0002      ,19295.29
    1388    1388
River Rch & RM=I101-00-00,I101-00-00_0002      ,18112.05
    1422    1422
River Rch & RM=I101-00-00,I101-00-00_0002      ,17956.78
    1547    1547
River Rch & RM=I101-00-00,I101-00-00_0002      ,17419.93
    1797    1797
River Rch & RM=I101-00-00,I101-00-00_0002      ,16461.61
    1844    1844
River Rch & RM=I101-00-00,I101-00-00_0002      ,16294.47
    2908    2908
River Rch & RM=I101-00-00,I101-00-00_0002      ,15551.22
    3002    3002
River Rch & RM=I101-00-00,I101-00-00_0002      ,15094.52
    3163    3163
River Rch & RM=I101-00-00,I101-00-00_0002      ,14349.11
    3330    3330
River Rch & RM=I101-00-00,I101-00-00_0002      ,13615.84
    3369    3369
River Rch & RM=I101-00-00,I101-00-00_0002      ,13450.83
    3561    3561
River Rch & RM=I101-00-00,I101-00-00_0002      ,12660.89
    3972    3972
River Rch & RM=I101-00-00,I101-00-00_0002      ,10635.42
    4304    4304
River Rch & RM=I101-00-00,I101-00-00_0002      ,9145.984
    4571    4571
River Rch & RM=I101-00-00,I101-00-00_0002      ,8029.999
    4923    4923
River Rch & RM=I101-00-00,I101-00-00_0002      ,6654.895
    5038    5038
River Rch & RM=I101-00-00,I101-00-00_0002      ,5335.797
    5161    5161
River Rch & RM=I101-00-00,I101-00-00_0002      ,3947.031
    5271    5271
River Rch & RM=I101-00-00,I101-00-00_0002      ,2737.14
    5395    5395
River Rch & RM=I101-00-00,I101-00-00_0002      ,1407.221
    5505    5505
Boundary for River Rch & Prof#=I101-00-00,I101-00-00_0002      , 1
Up Type= 0
Dn Type= 3
Dn Slope=.0017
Boundary for River Rch & Prof#=I101-00-00,I101-00-00_0002      , 2
Up Type= 0
Dn Type= 3
Dn Slope=.0017
DSS Import GetInterval= 0
DSS Import GetPeak= 0
DSS Import FillOption= 0

--- I101-00-00.f01 (steady flow) ---

Flow Title=FEMA Effective June 2007
Version=Version 3.0.1  Mar 2001
Number of Profiles= 4
Profile Names=10PCT_10yr, 2PCT_50yr, 1PCT_100yr, 0.2PCT_500yr
River Rch & RM=I101-00-00,I101-00-00_0002      ,21967.03
     457     676     790    1128
River Rch & RM=I101-00-00,I101-00-00_0002      ,21719.61
     509     750     876    1245
River Rch & RM=I101-00-00,I101-00-00_0002      ,21061.37
     559     820     956    1355
River Rch & RM=I101-00-00,I101-00-00_0002      ,20499.03
     621     908    1057    1492
River Rch & RM=I101-00-00,I101-00-00_0002      ,19855.4
     629     919    1071    1510
River Rch & RM=I101-00-00,I101-00-00_0002      ,19775.39
     663     967    1125    1585
River Rch & RM=I101-00-00,I101-00-00_0002      ,19456.34
     680     992    1154    1623
River Rch & RM=I101-00-00,I101-00-00_0002      ,19295.29
     826    1196    1388    1939
River Rch & RM=I101-00-00,I101-00-00_0002      ,18112.05
     847    1225    1422    1985
River Rch & RM=I101-00-00,I101-00-00_0002      ,17956.78
     925    1334    1547    2152
River Rch & RM=I101-00-00,I101-00-00_0002      ,17419.93
    1082    1552    1797    2485
River Rch & RM=I101-00-00,I101-00-00_0002      ,16461.61
    1112    1593    1844    2549
River Rch & RM=I101-00-00,I101-00-00_0002      ,16294.47
    1762    2514    2908    4001
River Rch & RM=I101-00-00,I101-00-00_0002      ,15551.22
    1820    2596    3002    4130
River Rch & RM=I101-00-00,I101-00-00_0002      ,15094.52
    1919    2735    3163    4349
River Rch & RM=I101-00-00,I101-00-00_0002      ,14349.11
    2021    2880    3330    4576
River Rch & RM=I101-00-00,I101-00-00_0002      ,13615.84
    2044    2913    3369    4629
River Rch & RM=I101-00-00,I101-00-00_0002      ,13450.83
    2162    3080    3561    4890
River Rch & RM=I101-00-00,I101-00-00_0002      ,12660.89
    2411    3435    3972    5456
River Rch & RM=I101-00-00,I101-00-00_0002      ,10635.42
    2612    3723    4304    5915
River Rch & RM=I101-00-00,I101-00-00_0002      ,9145.984
    2773    3954    4571    6283
River Rch & RM=I101-00-00,I101-00-00_0002      ,8029.999
    2986    4258    4923    6769
River Rch & RM=I101-00-00,I101-00-00_0002      ,6654.895
    3055    4357    5038    6915
River Rch & RM=I101-00-00,I101-00-00_0002      ,5335.797
    3129    4463    5161    7073
River Rch & RM=I101-00-00,I101-00-00_0002      ,3947.031
    3195    4558    5271    7213
River Rch & RM=I101-00-00,I101-00-00_0002      ,2737.14
    3269    4664    5395    7371
River Rch & RM=I101-00-00,I101-00-00_0002      ,1407.221
    3335    4759    5505    7512
Boundary for River Rch & Prof#=I101-00-00,I101-00-00_0002      , 1
Up Type= 0
Dn Type= 3
Dn Slope=.0017
Boundary for River Rch & Prof#=I101-00-00,I101-00-00_0002      , 2
Up Type= 0
Dn Type= 3
Dn Slope=.0017
Boundary for River Rch & Prof#=I101-00-00,I101-00-00_0002      , 3
Up Type= 0
Dn Type= 3
Dn Slope=.0017
Boundary for River Rch & Prof#=I101-00-00,I101-00-00_0002      , 4
Up Type= 0
Dn Type= 3
Dn Slope=.0017
DSS Import GetInterval= 0
DSS Import GetPeak= 0
DSS Import FillOption= 0

--- I101-00-00.g03 (geometry) ---

Geom Title=I101-00-00 June 2007 (Floodway)
Version=Version 3.0.1  Mar 2001

River Reach=I101-00-00     ,I101-00-00_0002
Reach XY= 30
      3186685.25       13812034.      3183902.75       13812904.
       3183552.5       13812866.        3182773.       13813292.
       3182347.5       13813930.      3181844.75       13814251.
      3180778.25       13815555.      3179622.75       13815957.
      3178030.75       13817358.        3177596.       13817933.
       3177238.5       13818979.       3176961.5       13820754.
      3176582.75       13821275.      3175315.25       13821988.
       3175117.5       13822276.      3174919.75       13823018.
      3174622.25       13823261.        3174330.       13824233.
      3174098.25       13824444.       3173857.5       13825451.
      3173158.75       13826261.      3172784.75       13826431.
      3172606.25       13826816.      3171195.75       13826883.
        3170848.       13827484.       3170582.5       13827681.
     3170251.274    13827796.295     3169659.889    13827758.316
     3168824.353    13828322.573        3168134.       13828178.

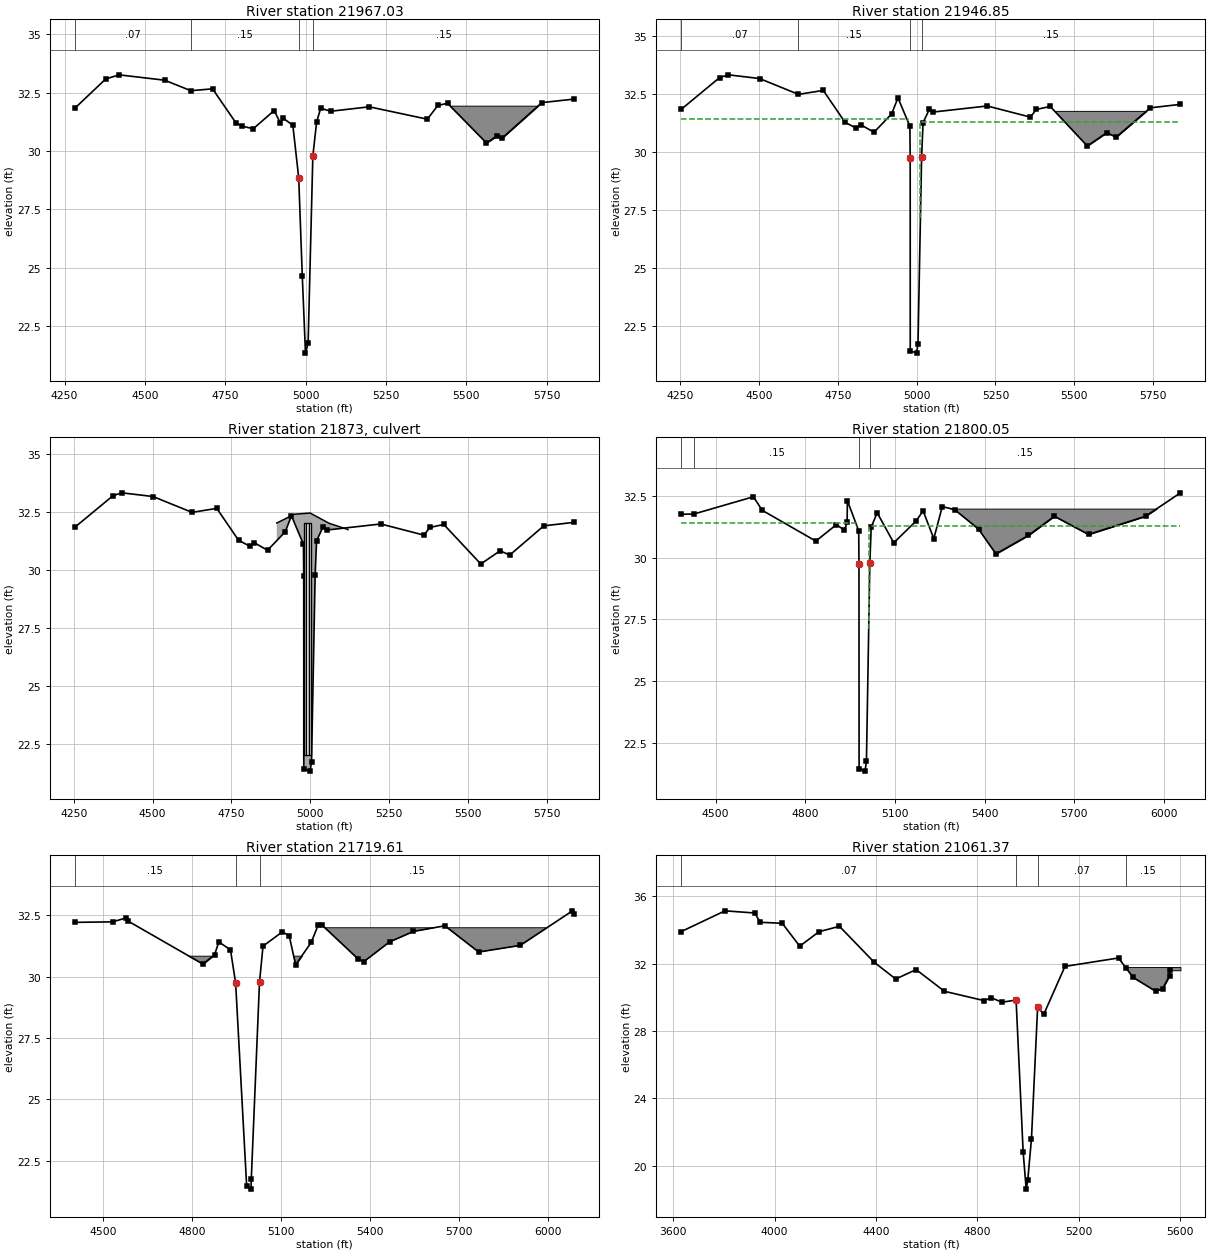
Type RM Length L Ch R = 1 ,21967.03,19.7,20.18,20.88
XS GIS Cut Line= 6
 3181516.644222813813598.3519885     3181942.375    13814124.843
     3181955.685    13814145.423     3181977.392    13814168.336
     3182102.002    13814335.577     3182528.158    13814774.051
#Sta/Elev= 30
 4282.15   31.83 4377.92   33.08 4419.49   33.26 4561.52   33.03 4643.09   32.58
 4710.57   32.66 4783.47    31.2 4803.59   31.06 4837.22   30.95 4902.41   31.73
 4921.76   31.19  4928.5   31.42  4960.5    31.1  4978.8   28.84  4989.8   24.66
 4999.81   21.34    5008   21.76  5022.7   29.78  5034.6   31.25  5047.3   31.83
 5078.61    31.7 5198.25   31.89 5379.06   31.36 5411.89   31.95 5441.81   32.04
  5563.1   30.34 5595.21   30.64 5610.86   30.54  5735.4   32.07 5835.43   32.22
#Mann= 4 ,-1 , 0
 4282.15     .07       0 4643.09     .15       0  4978.8    .015       0
  5022.7     .15       0
#Block Obstruct= 1 ,-1
 5440.34 5767.44   31.94
Bank Sta=4978.8,5022.7
XS Rating Curve= 0
Exp/Cntr=.5,.3

Type RM Length L Ch R = 1 ,21946.85,178.35,146.8,116.35
XS GIS Cut Line= 6
  3181480.309553 13813591.842254     3181922.152    13814129.119
     3181930.153    13814145.121     3181962.086    13814181.261
     3182086.741    13814348.571     3182513.816     13814787.99
#Sta/Elev= 30
 4253.64   31.83 4374.87   33.19  4403.1   33.31 4501.66   33.15 4625.21   32.47
 4703.81   32.64 4772.82   31.27 4807.59   31.02 4823.34   31.16 4864.77   30.84
  4920.7   31.63 4940.73   32.32 4978.57    31.1 4979.56   29.75 4979.75   21.44
 4999.81   21.34 5004.28   21.75 5015.77   29.78 5020.37   31.25  5040.4   31.83
 5052.97   31.71 5224.08   31.97 5361.04   31.49 5379.44   31.82 5423.79   31.95
  5541.2   30.25 5602.82   30.82 5632.86   30.63 5741.05   31.89 5836.84   32.04
#Mann= 4 ,-1 , 0
 4253.64     .07       0 4625.21     .15       0 4979.56    .015       0
 5015.77     .15       0
#XS Ineff= 2 , 0
       0    4972    31.4    5012       0    31.3
Permanent Ineff=
       F       F
#Block Obstruct= 1 ,-1
 5423.32  5795.8   31.76
Bank Sta=4979.56,5015.77
XS Rating Curve= 0
Exp/Cntr=.5,.3

Type RM Length L Ch R = 2 ,21873   ,,,
BEGIN DESCRIPTION:
WICHITA ST
END DESCRIPTION:
Bridge Culvert--1,0,-1,-1, 0
Deck Dist Width WeirC Skew NumUp NumDn MinLoCord MaxHiCord MaxSubmerge Is_Ogee
1,133,2.6,0, 5, 5, , , .95, 0, 0,0,,
    4894    4950    5000    5060    5120
   32.01   32.39   32.44      32   31.73
                                        
    4894    4950    5000    5060    5120
   32.01   32.39   32.44      32   31.73
                                        
BR Coef=-1 , 0 , 0 ,, 0 ,,,.8,-1,,0,
WSPro=,,,, 1 ,,,, 0 ,,,, 0 ,,,,-1 ,-1 ,-1 , 0 , 0 , 0 , 0 , 0
Multiple Barrel Culv=2,10,8,133,.012,.7,1,8,3,22.028,21.821, 3,Culvert #1  , 0 ,1
  4983.9  4983.9    4992    4992  5000.1  5000.1
Culvert Bottom n=.012
BC Design=,, 0 ,, 0 ,,,,,,
BC HTab HWMax=33.31

Type RM Length L Ch R = 1 ,21800.05,85.68,80.43,74.04
XS GIS Cut Line= 5
      3181388.16    13813859.564      3181830.04    13814255.428
     3181860.872    13814283.296     3181871.545    13814294.562
     3182740.003     13815122.58
#Sta/Elev= 30
 4385.32   31.77 4427.37   31.78 4626.39   32.48 4655.84   31.93 4835.19   30.68
 4904.09   31.35 4930.71   31.12 4939.78   31.44 4940.73   32.32 4978.57    31.1
 4979.45   29.75 4979.81   21.44 4999.81   21.34 5004.43   21.74 5015.77   29.78
 5020.37   31.25  5040.4   31.83 5095.71   30.61 5170.89    31.5 5193.85   31.91
 5229.73   30.78 5258.05   32.08 5299.17   31.96 5379.24   31.17 5437.43   30.16
 5546.18   30.91 5632.97   31.69 5747.35   30.95  5938.1   31.69 6054.73   32.64
#Mann= 4 ,-1 , 0
 4385.32     .07       0 4427.37     .15       0 4979.45    .015       0
 5015.77     .15       0
#XS Ineff= 2 , 0
       0    4972    31.4    5012       0    31.3
Permanent Ineff=
       F       F
#Block Obstruct= 1 ,-1
 5263.03 6031.93      32
Bank Sta=4979.45,5015.77
XS Rating Curve= 0
Exp/Cntr=.5,.3

Type RM Length L Ch R = 1 ,21719.61,671.7,658.25,624.65
XS GIS Cut Line= 4
      3181341.47    13813947.966     3181777.096     13814315.41
     3181790.038    13814327.108     3182672.404     13815125.18
#Sta/Elev= 29
 4405.48   32.22 4532.89   32.24 4577.66    32.4 4585.16   32.27 4837.18   30.52
  4876.7    30.9    4891   31.42  4930.3    31.1  4947.7   29.75 4984.91   21.46
 4999.81   21.34 5000.53   21.76  5028.2   29.78    5040   31.25  5104.9   31.83
 5128.25   31.68 5149.93   30.49  5202.6    31.4 5226.14   32.11 5238.13   32.12
 5359.62   30.74 5379.31   30.61 5466.68   31.42 5547.48   31.85 5653.45   32.08
  5767.5   31.01 5907.85   31.28 6083.63   32.69 6088.92   32.56
#Mann= 3 ,-1 , 0
 4405.48     .15       0  4947.7    .015       0  5028.2     .15       0
#Block Obstruct= 3 ,-1
 5241.39 6162.19      32    4765    4880   30.86    5135    5180   30.86
Bank Sta=4947.7,5028.2
XS Rating Curve= 0
Exp/Cntr=.3,.1

Type RM Length L Ch R = 1 ,21061.37,553.6,562.34,583.88
XS GIS Cut Line= 6
     3180290.147    13814069.531     3181268.091    13814754.644
     3181360.753    13814830.864     3181431.077    13814878.448
     3181529.152    13814936.973     3181859.277    13815185.602
#Sta/Elev= 30
 3632.24    33.9 3804.51   35.13 3922.13      35 3943.02   34.45 4030.22   34.39
 4099.25   33.03 4175.25   33.89 4255.89   34.21 4393.19   32.07 4477.77   31.08
 4558.25   31.64 4669.98   30.35 4825.55    29.8  4855.1   29.97 4895.94    29.7
 4952.54   29.83 4980.43    20.8 4992.37    18.6  4998.5   19.12 5013.23    21.6
 5037.46    29.4 5061.87   28.99 5145.39   31.83 5356.62   32.33 5385.29   31.75
 5413.88   31.18 5502.46   30.36 5530.39   30.51 5557.79   31.27 5558.67    31.6
#Mann= 4 ,-1 , 0
 3632.24     .07       0 4952.54    .035       0 5037.46     .07       0
 5385.29     .15       0
#Block Obstruct= 1 ,-1
 5356.62 5600.84   31.79
Bank Sta=4952.54,5037.46
XS Rating Curve= 0
Exp/Cntr=.3,.1

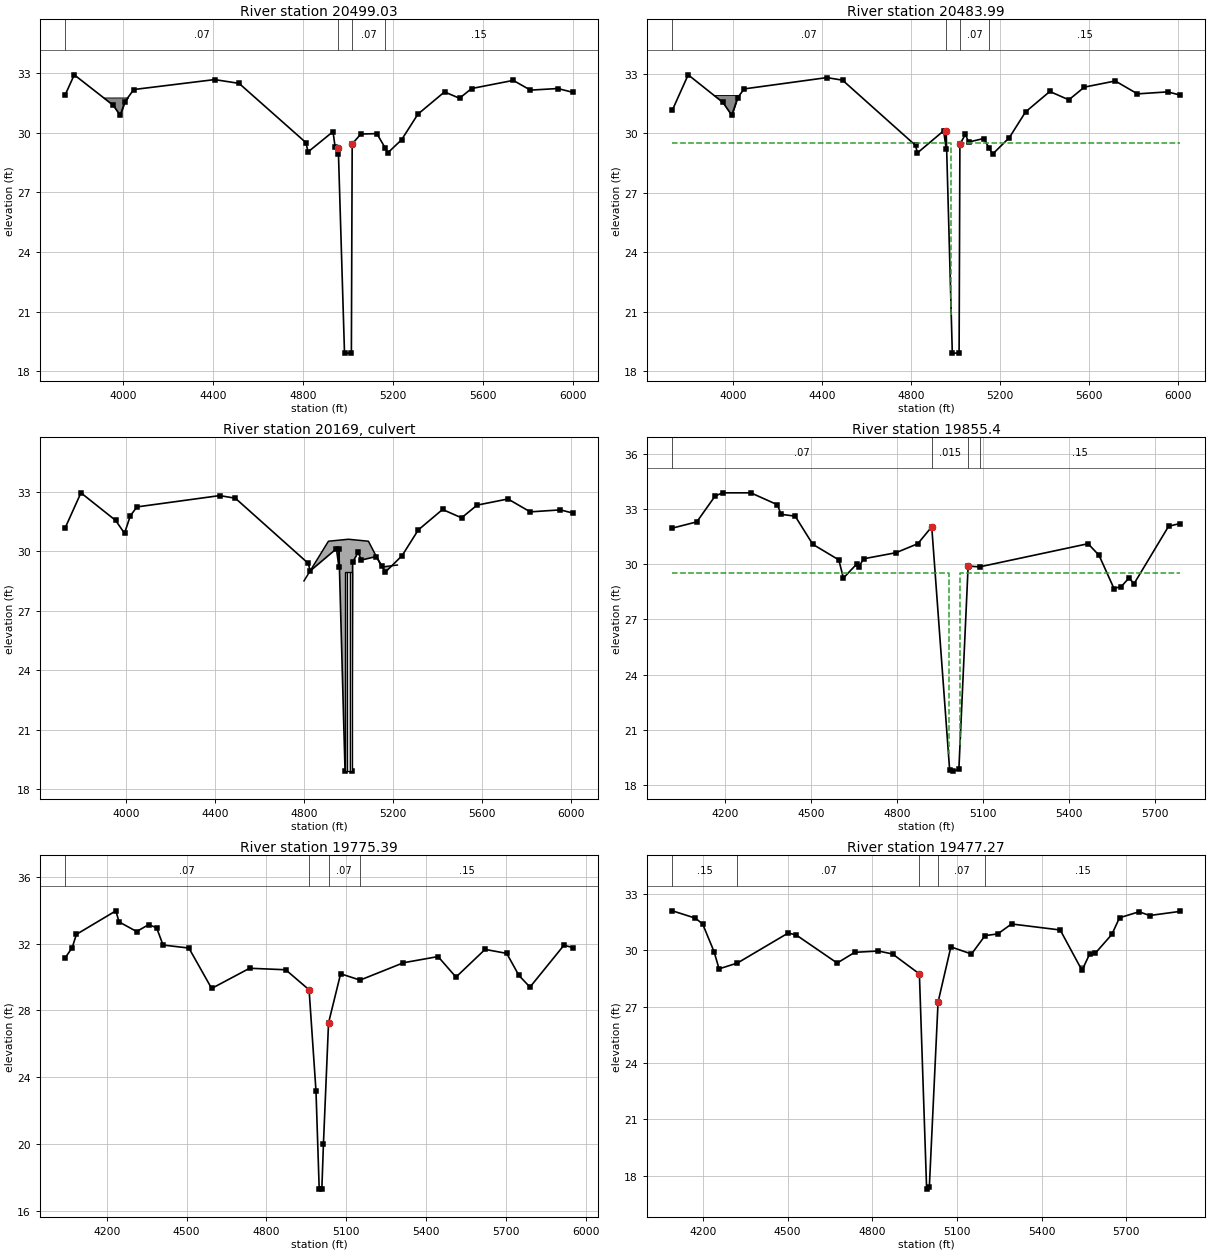
Type RM Length L Ch R = 1 ,20499.03,15.13,15.04,15.82
XS GIS Cut Line= 6
 3180045.584526713814461.7884609     3180960.471    13815221.701
     3180979.705    13815234.629     3181049.842    13815285.716
     3181075.952    13815307.872     3181768.033    13815918.805
#Sta/Elev= 30
 3742.98   31.91 3783.36   32.92 3956.31   31.39 3987.68   30.88 4008.05   31.56
 4048.07   32.18 4407.34   32.68 4516.02   32.49 4813.05   29.51 4822.84   29.04
 4933.72   30.06 4943.02   29.29 4956.04   28.93 4957.17   29.23 4984.81   18.91
 5015.34   18.91 5018.95   29.44  5057.4   29.94 5128.71   29.96 5166.61   29.22
    5178      29 5238.47   29.65  5311.1   30.94 5429.47   32.06 5496.06   31.74
 5549.83   32.23 5734.94   32.64 5811.52   32.15  5933.1   32.23 5999.64   32.04
#Mann= 4 ,-1 , 0
 3742.98     .07       0 4957.17    .015       0 5018.95     .07       0
 5166.61     .15       0
#Block Obstruct= 1 ,-1
 3788.87 4061.97   31.78
Bank Sta=4957.17,5018.95
XS Rating Curve= 0
Exp/Cntr=.5,.3

Type RM Length L Ch R = 1 ,20483.99,500.6,628.59,728.41
XS GIS Cut Line= 6
 3180022.107617213814461.7878942     3180951.472    13815233.726
     3180971.102     13815246.92     3181040.561    13815297.513
     3181071.546    13815323.806     3181762.113    13815939.733
#Sta/Elev= 30
 3725.63   31.17 3796.53   32.94 3952.55   31.55 3992.62    30.9 4018.64   31.78
 4048.54   32.23 4420.51    32.8 4491.01   32.67  4819.6   29.38 4827.56      29
 4946.03   30.12 4957.03   29.21 4957.17   30.09 4984.81   18.91 5015.34   18.91
 5018.95   29.44  5043.7   29.94 5057.89   29.55 5126.13   29.73 5149.83   29.26
 5165.85   28.94 5241.14   29.77 5314.33   31.07 5423.47    32.1 5509.01   31.68
 5578.82   32.32 5717.84   32.63 5817.92   31.98 5953.52   32.08 6009.33   31.92
#Mann= 4 ,-1 , 0
 3725.63     .07       0 4957.17    .015       0 5018.95     .07       0
 5149.83     .15       0
#XS Ineff= 2 , 0
       0    4980    29.5    5020       0    29.5
Permanent Ineff=
       F       F
#Block Obstruct= 1 ,-1
 3834.03 4073.53   31.92
Bank Sta=4957.17,5018.95
XS Rating Curve= 0
Exp/Cntr=.5,.3

Type RM Length L Ch R = 2 ,20169   ,,,
BEGIN DESCRIPTION:
PASADENA BLVD
END DESCRIPTION:
Bridge Culvert--1,0,-1,-1, 0
Deck Dist Width WeirC Skew NumUp NumDn MinLoCord MaxHiCord MaxSubmerge Is_Ogee
5,605,2.6,0, 6, 6, , , .95, 0, 0,0,,
    4800    4910    5000    5090    5150    5220
    28.5    30.5    30.6    30.5    29.2    29.3
                                                
    4800    4910    5000    5090    5150    5220
    28.5    30.5    30.6    30.5    29.2    29.3
                                                
BR Coef=-1 , 0 , 0 ,, 0 ,,,.8,-1,,0,
WSPro=,,,, 1 ,,,, 0 ,,,, 0 ,,,,-1 ,-1 ,-1 , 0 , 0 , 0 , 0 , 0
Multiple Barrel Culv=2,10,10,605,.012,.7,1,8,3,18.94,18.83, 3,Culvert #1  , 0 ,5
  4989.9  4989.9    5000    5000  5010.1  5010.1
Culvert Bottom n=.012
BC Design=,, 0 ,, 0 ,,,,,,
BC HTab HWMax=32.94

Type RM Length L Ch R = 1 ,19855.4 ,80.09,80.01,80.24
XS GIS Cut Line= 6
      3180021.82    13814737.863     3180248.825    13814970.939
      3180408.88    13815360.675     3180557.748    13815707.388
      3180678.85    13815972.938     3180856.545    13816411.541
#Sta/Elev= 30
 4017.48   31.97 4102.58   32.31 4165.99   33.71 4192.07   33.89 4290.77   33.89
 4383.68   33.24 4395.93   32.72 4445.46   32.62 4506.59   31.09 4597.57   30.24
 4613.59   29.25 4660.33   30.02 4666.72   29.84  4684.2    30.3 4796.88   30.63
 4872.95   31.12 4921.57   32.04 4983.97   18.81 4996.11   18.74 5016.16   18.83
 5048.43    29.9 5088.52   29.86 5466.58   31.12  5504.8   30.49 5556.97   28.68
 5582.57   28.79 5609.54   29.26 5626.81   28.94 5747.38   32.07 5787.24   32.22
#Mann= 4 ,-1 , 0
 4017.48     .07       0 4921.57    .015       0 5048.43     .07       0
 5088.52     .15       0
#XS Ineff= 2 , 0
       0    4980    29.5    5020       0    29.5
Permanent Ineff=
       F       F
Bank Sta=4921.57,5048.43
XS Rating Curve= 0
Exp/Cntr=.5,.3

Type RM Length L Ch R = 1 ,19775.39,384.04,298.11,238.94
XS GIS Cut Line= 6
 3180003.639680513814887.4523628     3180224.297    13815136.245
      3180484.37     13815739.29     3180605.367    13816004.609
     3180704.535    13816248.623     3180840.233    13816595.472
#Sta/Elev= 30
 4043.78   31.14 4070.23   31.76 4085.98   32.55 4234.28   33.96 4245.96    33.3
 4312.04   32.72 4357.25   33.13 4387.11   32.95 4411.45   31.91 4508.53   31.73
 4593.98   29.31 4736.56   30.52 4872.07   30.43    4960   29.23  4985.9   23.17
    4998    17.3  5007.9   17.29  5013.9      20 5033.07   27.25 5078.48   30.19
 5151.52   29.81 5314.58   30.85 5444.47   31.22 5511.76   29.99  5621.1   31.65
 5702.41   31.41 5748.15   30.09 5789.71   29.39 5917.39    31.9 5950.51   31.76
#Mann= 4 ,-1 , 0
 4043.78     .07       0    4960    .015       0 5033.07     .07       0
 5151.52     .15       0
Bank Sta=4960,5033.07
XS Rating Curve= 0
Exp/Cntr=.3,.1

Type RM Length L Ch R = 1 ,19477.27,24.2,20.93,20.97
XS GIS Cut Line= 6
      3179635.76    13815124.069     3180059.778    13815662.679
     3180181.107    13815801.504     3180295.335    13815946.238
     3180620.497    13816400.022 3180727.086896113816552.3150462
#Sta/Elev= 30
 4091.97   32.11 4173.12   31.72    4199   31.41 4239.36   29.94 4257.21   29.02
 4322.19   29.33 4502.37   30.93  4530.9   30.82 4675.56   29.33 4738.02    29.9
 4821.49   29.97 4872.07   29.81 4966.93   28.75 4992.57   17.29 5002.16   17.41
 5033.07   27.25 5078.48   30.19 5151.52   29.81 5199.62   30.79 5244.49   30.88
 5293.43   31.41 5465.79   31.09 5542.97   28.94 5570.34   29.82 5589.92   29.85
 5648.55   30.85 5675.93   31.74 5745.37   32.06 5782.43   31.86 5890.32   32.08
#Mann= 5 ,-1 , 0
 4091.97     .15       0 4322.19     .07       0 4966.93    .015       0
 5033.07     .07       0 5199.62     .15       0
#Block Obstruct= 1 ,-1
    5524    5560    29.2
Bank Sta=4966.93,5033.07
XS Rating Curve= 0
Exp/Cntr=.5,.3

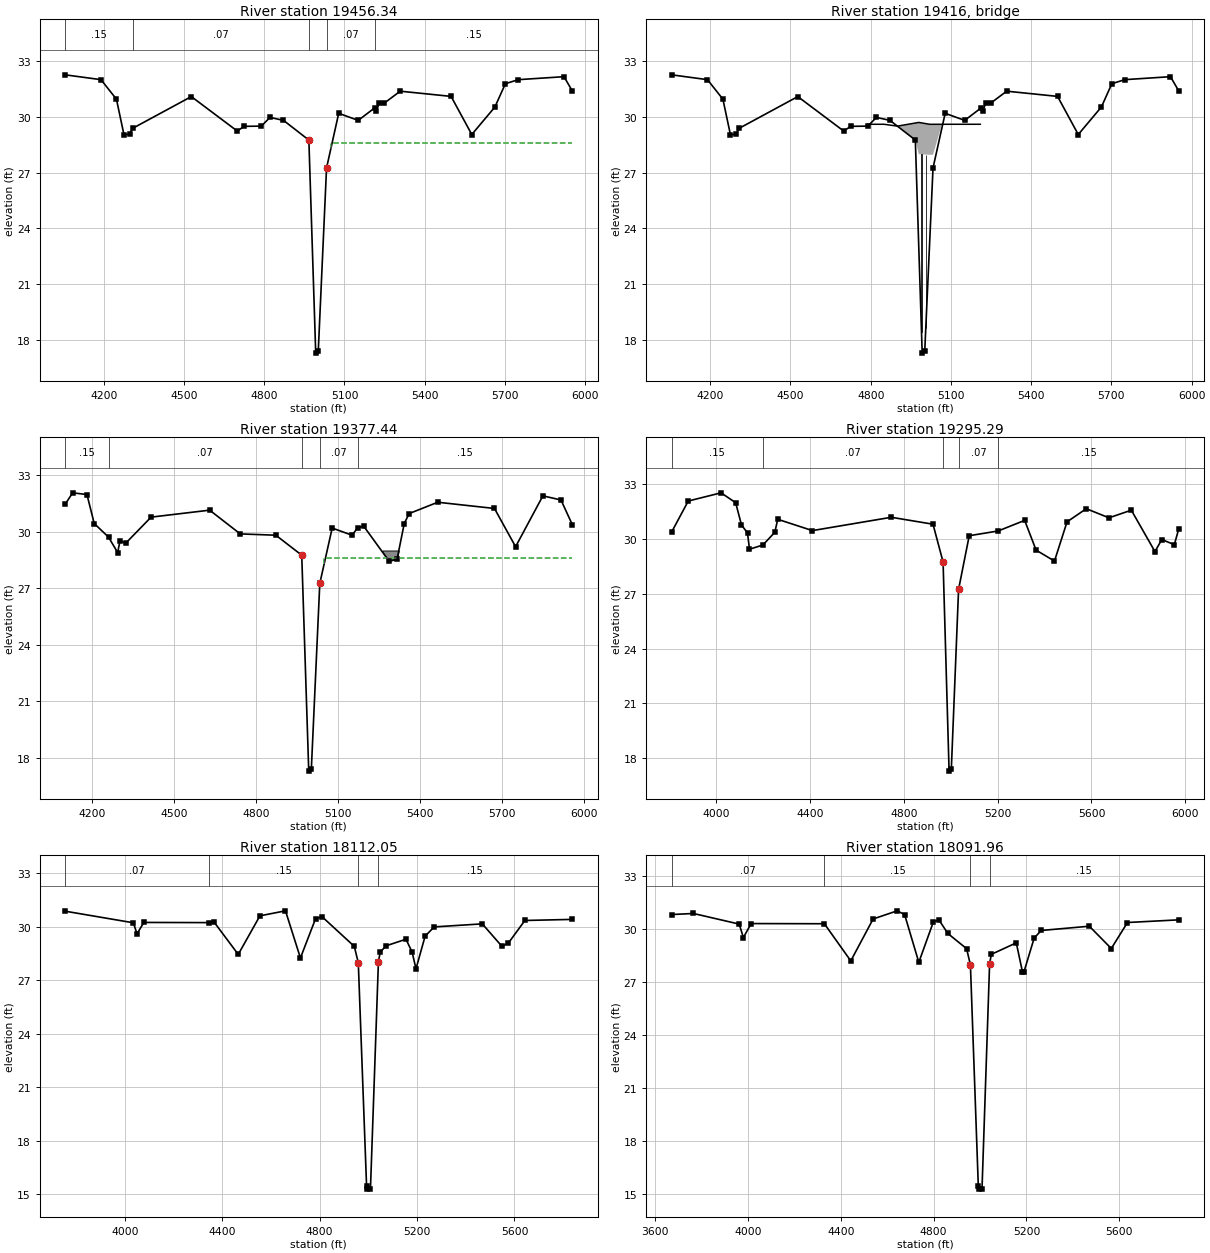
Type RM Length L Ch R = 1 ,19456.34,79.61,78.9,87.93
XS GIS Cut Line= 6
      3179571.97    13815121.169     3179788.122    13815368.755
     3180165.312    13815813.864      3180279.36    13815958.281
     3180516.246    13816288.413 3180741.384893513816611.7225468
#Sta/Elev= 30
  4055.6   32.26 4189.64      32 4247.39   30.95 4275.51   29.04 4296.28   29.06
 4307.77   29.38 4527.46   31.09 4698.75   29.24 4725.81   29.49 4789.16    29.5
 4821.49   29.97 4872.07   29.81 4966.93   28.75 4992.57   17.29 5002.16   17.41
 5033.07   27.25 5078.48   30.19 5151.52   29.81 5213.82   30.49 5219.76   30.32
 5230.53   30.77 5248.12   30.73  5308.6   31.38 5498.72    31.1 5576.19   29.05
 5662.67   30.53  5701.7   31.78 5749.74      32 5921.04   32.16 5952.04   31.39
#Mann= 5 ,-1 , 0
  4055.6     .15       0 4307.77     .07       0 4966.93    .015       0
 5033.07     .07       0 5213.82     .15       0
#XS Ineff= 2 , 0
       0    4963    28.6    5049       0    28.6
Permanent Ineff=
       F       F
Bank Sta=4966.93,5033.07
XS Rating Curve= 0
Exp/Cntr=.5,.3

Type RM Length L Ch R = 3 ,19416   ,,,
BEGIN DESCRIPTION:
BURKE ST
END DESCRIPTION:
Bridge Culvert--1,0,-1,-1, 0
Deck Dist Width WeirC Skew NumUp NumDn MinLoCord MaxHiCord MaxSubmerge Is_Ogee
5,59,2.6,0, 6, 6, , , .95, 0, 0,0,,
    4790    4850    4900    4980    5020    5210
    29.6    29.6    29.5    29.7    29.6    29.6
   27.99   27.99   27.99   27.99   27.96   27.96
    4790    4850    4900    4980    5020    5210
    29.6    29.6    29.5    29.7    29.6    29.6
   27.99   27.99   27.99   27.99   27.96   27.96
Pier Skew, UpSta & Num, DnSta & Num=  ,4990, 4 ,4990, 4 , 3 , 3 , 0 ,,
     1.2     1.2       2       2
      17   25.96   25.97    28.5
     1.2     1.2       2       2
      17   25.96   25.97    28.5
Pier Skew, UpSta & Num, DnSta & Num=  ,5006, 4 ,5006, 4 , 3 , 3 , 0 ,,
     1.2     1.2       2       2
      17   25.96   25.97    28.5
     1.2     1.2       2       2
      17   25.96   25.97    28.5
BR Coef=-1 , 1 , 0 ,, 0 ,,,.8,-1,2,0,
WSPro=,,,, 1 ,,,, 0 ,,,, 0 ,,,,-1 ,-1 ,-1 , 0 , 0 , 0 , 0 , 0
BC Design=,, 0 ,, 0 ,,,,,,
BC HTab HWMax=32.26

Type RM Length L Ch R = 1 ,19377.44,98.87,82.15,78.2
XS GIS Cut Line= 6
      3179528.47    13815184.963     3179677.462    13815360.881
     3179977.615     13815703.16     3180147.633    13815913.373
     3180244.268    13816051.674 3180628.521920513816676.6354733
#Sta/Elev= 30
 4099.94   31.45 4127.35   32.06 4179.82   31.97 4206.53   30.43 4258.89   29.71
 4292.34   28.89 4301.01   29.51 4321.47   29.38 4414.89   30.77 4629.54   31.14
 4741.53   29.88 4872.07   29.81 4966.93   28.75 4992.57   17.29 5002.16   17.41
 5033.07   27.25 5078.48   30.19 5151.52   29.81 5171.34    30.2 5194.02   30.29
 5286.59   28.44 5316.26   28.54 5342.62   30.43 5360.64   30.96 5465.33   31.56
  5673.2   31.23  5750.6    29.2 5850.64    31.9 5916.96   31.68 5958.44   30.37
#Mann= 5 ,-1 , 0
 4099.94     .15       0 4258.89     .07       0 4966.93    .015       0
 5033.07     .07       0 5171.34     .15       0
#XS Ineff= 2 , 0
       0    4963    28.6    5049       0    28.6
Permanent Ineff=
       F       F
#Block Obstruct= 1 ,-1
    5263    5327      29
Bank Sta=4966.93,5033.07
XS Rating Curve= 0
Exp/Cntr=.5,.3

Type RM Length L Ch R = 1 ,19295.29,1164.82,1183.23,1088.46
XS GIS Cut Line= 6
      3179220.71    13815031.229     3179478.231    13815281.327
     3179551.228    13815359.349      3180046.85    13815906.562
     3180163.824    13816066.211      3180564.95     13816713.45
#Sta/Elev= 30
 3808.91   30.39 3879.79   32.09 4019.74   32.54 4082.04      32 4106.98   30.78
 4132.67   30.34  4141.1   29.45 4198.34   29.68 4249.22   30.38 4261.57   31.09
 4409.52   30.47 4746.06    31.2    4924   30.82 4966.93   28.75 4992.57   17.29
 5002.16   17.41 5033.07   27.25 5078.48   30.19 5201.96   30.45    5315   31.03
 5363.76    29.4 5442.14    28.8 5495.78   30.95 5577.86   31.67 5674.64   31.17
 5769.95   31.59 5870.75   29.32    5900   29.98 5953.48    29.7 5972.41   30.57
#Mann= 5 ,-1 , 0
 3808.91     .15       0 4198.34     .07       0 4966.93    .015       0
 5033.07     .07       0 5201.96     .15       0
Bank Sta=4966.93,5033.07
XS Rating Curve= 0
Exp/Cntr=.3,.1

Type RM Length L Ch R = 1 ,18112.05,20.13,20.09,20.24
XS GIS Cut Line= 6
      3177988.73    13815477.833     3178389.001    13815843.345
     3178936.542    13816344.376     3179073.278    13816455.465
     3179156.518    13816527.336 3179657.665475813816996.2716544
#Sta/Elev= 30
 3754.92   30.86 4035.13   30.21 4050.01   29.59 4077.97   30.23 4345.38   30.22
 4364.83   30.28 4465.69   28.44 4554.77    30.6 4659.64   30.88 4721.03   28.24
 4783.17   30.44  4809.9   30.55 4942.24   28.89 4958.68   27.97 4992.58   15.49
 4993.85    15.3 5008.63   15.32 5041.32   28.04 5048.75   28.57 5072.52   28.92
 5154.47   29.29 5179.63   28.57 5195.58   27.63 5232.99   29.46 5270.23   29.98
 5467.88   30.15 5548.61   28.89  5574.7   29.07 5642.66   30.34 5837.45    30.4
#Mann= 4 ,-1 , 0
 3754.92     .07       0 4345.38     .15       0 4958.68    .015       0
 5041.32     .15       0
Bank Sta=4958.68,5041.32
XS Rating Curve= 0
Exp/Cntr=.5,.3

Type RM Length L Ch R = 1 ,18091.96,55.37,55.01,55.67
XS GIS Cut Line= 6
      3177982.93     13815509.73     3178420.031    13815898.848
     3178923.475    13816359.528     3179060.433    13816470.798
     3179143.143    13816542.211      3179699.56    13817066.876
#Sta/Elev= 30
 3671.24   30.82 3765.13   30.88 3962.51   30.28 3980.44   29.52 4013.95   30.31
 4329.42    30.3 4443.21    28.2  4539.5   30.57 4643.19   31.03 4675.07   30.82
 4736.31   28.12 4799.45   30.42 4822.94   30.52 4861.29   29.75 4942.24   28.89
 4958.68   27.97 4992.58   15.49 4993.85    15.3 5008.63   15.32 5041.32   28.04
 5048.75   28.57 5156.28   29.22    5183   27.57  5189.5   27.59  5233.3   29.49
 5263.68   29.92 5471.11   30.16 5565.55    28.9 5635.37   30.37 5856.36   30.52
#Mann= 4 ,-1 , 0
 3671.24     .07       0 4329.42     .15       0 4958.68    .015       0
 5041.32     .15       0
#XS Ineff= 2 , 0
       0    4958    26.8    5042       0    26.9
Permanent Ineff=
       F       F
Bank Sta=4958.68,5041.32
XS Rating Curve= 0
Exp/Cntr=.5,.3

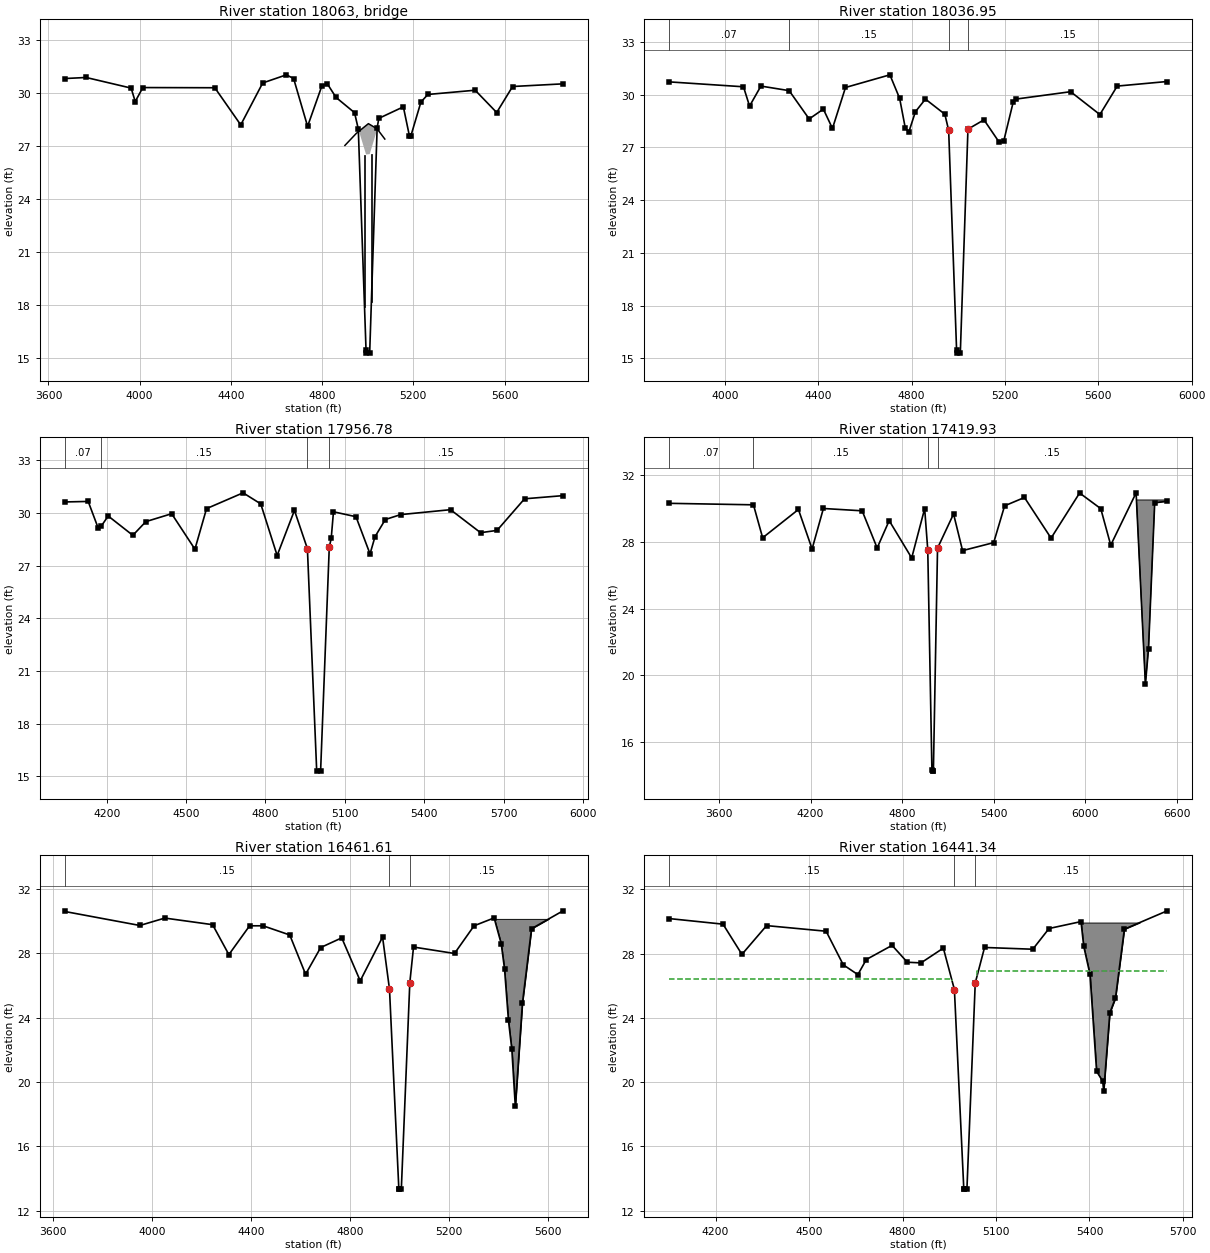
Type RM Length L Ch R = 3 ,18063   ,,,
BEGIN DESCRIPTION:
BEUSCH DR
END DESCRIPTION:
Bridge Culvert--1,0,-1,-1, 0
Deck Dist Width WeirC Skew NumUp NumDn MinLoCord MaxHiCord MaxSubmerge Is_Ogee
5,42,2.6,0, 5, 5, , , .95, 0, 0,0,,
    4900    4950    5003    5041    5075
   27.04   27.72   28.27   27.98    27.4
           26.49   26.54    26.6
    4900    4950    5003    5041    5075
   27.04   27.72   28.27   27.98    27.4
           26.49   26.54    26.6
Pier Skew, UpSta & Num, DnSta & Num=  ,4986, 4 ,4986, 4 , 3 , 3 , 0 ,,
     1.2     1.2       2       2
      15   24.49    24.5      27
     1.2     1.2       2       2
      15   24.49    24.5      27
Pier Skew, UpSta & Num, DnSta & Num=  ,5016, 4 ,5016, 4 , 3 , 3 , 0 ,,
     1.2     1.2       2       2
      15   24.49    24.5      27
     1.2     1.2       2       2
      15   24.49    24.5      27
BR Coef=-1 , 1 , 0 ,, 0 ,,,.8,-1,2,0,
WSPro=,,,, 1 ,,,, 0 ,,,, 0 ,,,,-1 ,-1 ,-1 , 0 , 0 , 0 , 0 , 0
BC Design=,, 0 ,, 0 ,,,,,,
BC HTab HWMax=31.05

Type RM Length L Ch R = 1 ,18036.95,80.54,80.17,80.97
XS GIS Cut Line= 6
      3177959.73    13815561.925     3178411.517    13815965.609
     3178887.541    13816401.198      3179025.11    13816512.964
     3179106.361    13816583.117     3179702.459    13817148.067
#Sta/Elev= 30
 3759.68   30.73 4079.43   30.45 4105.42   29.35 4154.04   30.49  4275.1   30.23
 4360.84   28.62 4421.67   29.18 4460.71   28.08 4516.51   30.41  4706.8   31.13
 4748.61   29.79 4772.85    28.1 4788.23   27.89 4816.15   29.03    4859   29.75
 4942.24   28.89 4958.68   27.97 4992.58   15.49 4993.85    15.3 5008.63   15.32
 5041.32   28.04    5110   28.57 5175.51   27.29 5194.52   27.36 5235.49   29.59
 5246.99   29.75 5481.31   30.17 5606.67   28.87 5680.98   30.49 5895.04   30.75
#Mann= 4 ,-1 , 0
 3759.68     .07       0  4275.1     .15       0 4958.68    .015       0
 5041.32     .15       0
#XS Ineff= 2 , 0
       0    4958    26.8    5042       0    26.9
Permanent Ineff=
       F       F
Bank Sta=4958.68,5041.32
XS Rating Curve= 0
Exp/Cntr=.5,.3

Type RM Length L Ch R = 1 ,17956.78,484.75,536.85,571.59
XS GIS Cut Line= 6
      3178222.86    13815901.422     3178835.273    13816461.809
     3178973.732    13816574.296      3179052.86    13816642.617
      3179275.04    13816850.637     3179667.663     13817226.36
#Sta/Elev= 30
 4041.35   30.63 4130.13   30.66 4167.95   29.14 4178.85   29.24 4205.76   29.83
 4298.86   28.73 4348.06   29.51 4445.59   29.96 4533.53   27.94 4577.44   30.25
 4715.59   31.15 4782.37   30.52 4844.35   27.58  4909.7   30.15 4958.68   27.97
 4993.85    15.3 5008.63   15.32 5041.32   28.04 5048.75   28.57 5057.23   30.07
 5142.31   29.79 5195.39   27.67  5214.2   28.65 5253.18   29.63 5311.32   29.91
 5499.63   30.19 5613.19   28.88 5675.51   29.01 5779.45   30.81  5924.8   30.99
#Mann= 4 ,-1 , 0
 4041.35     .07       0 4178.85     .15       0 4958.68    .015       0
 5041.32     .15       0
Bank Sta=4958.68,5041.32
XS Rating Curve= 0
Exp/Cntr=.3,.1

Type RM Length L Ch R = 1 ,17419.93,977.01,958.33,931.74
XS GIS Cut Line= 6
      3177477.44    13815527.693     3178455.813    13816809.983
     3178513.602    13816870.798      3178636.76    13817024.081
     3178986.984    13817419.641     3179553.567    13818038.223
#Sta/Elev= 30
 3271.57   30.32 3825.88   30.23 3886.02   28.25 4120.42   29.95 4210.06   27.58
 4284.04   30.01 4538.08   29.87 4636.32   27.64 4715.17   29.28 4862.63   27.04
  4947.7      30 4967.95   27.53 4995.24   14.31 5000.92   14.24 5004.88   14.27
 5032.05   27.63 5136.98   29.68 5196.04   27.48 5399.96   27.96 5471.55   30.17
 5601.62   30.67 5775.97   28.23 5962.91   30.94 6101.56      30 6166.87   27.81
 6333.24   30.95 6394.15   19.46 6414.45   21.59 6455.06   30.35 6533.66   30.44
#Mann= 4 ,-1 , 0
 3271.57     .07       0 3825.88     .15       0 4967.95    .015       0
 5032.05     .15       0
#Block Obstruct= 1 ,-1
    6310 6536.76   30.52
Bank Sta=4967.95,5032.05
XS Rating Curve= 0
Exp/Cntr=.3,.1

Type RM Length L Ch R = 1 ,16461.61,20.16,20.27,20.01
XS GIS Cut Line= 6
 3176958.220372713816470.8035861     3177316.977    13816952.931
     3177716.997    13817435.605     3177921.885    13817638.199
     3178112.435    13817813.424     3178325.096    13818015.081
#Sta/Elev= 30
 3648.56   30.59 3951.73   29.72 4052.51   30.18 4245.25   29.77 4310.93   27.91
 4394.59    29.7  4448.8    29.7 4556.57   29.13 4620.47   26.69 4681.45   28.35
 4766.33   28.95 4840.85   26.28 4931.08      29    4959   25.76 4996.72   13.35
 4998.11   13.34 5006.79   13.36    5041   26.17    5056   28.38  5221.3   27.98
 5300.18    29.7  5381.2   30.19 5409.75   28.59 5423.08   27.03 5438.95   23.83
 5452.57   22.03 5466.68   18.48 5495.39    24.9 5532.08   29.52 5659.07   30.63
#Mann= 3 ,-1 , 0
 3648.56     .15       0    4959    .015       0    5041     .15       0
#Block Obstruct= 2 ,-1
                         5379.62 5659.07   30.13
Bank Sta=4959,5041
XS Rating Curve= 0
Exp/Cntr=.5,.3

Type RM Length L Ch R = 1 ,16441.34,64.87,65.87,62.67
XS GIS Cut Line= 6
      3177019.35    13816602.246     3177408.257    13817095.134
     3177639.407    13817371.948     3177702.158    13817449.056
     3177907.991    13817652.593     3178307.698    13818020.881
#Sta/Elev= 30
 4050.26   30.18 4223.97   29.83 4284.69   27.95 4363.86   29.74 4554.94   29.39
 4609.92    27.3 4656.76   26.69 4683.92   27.63 4766.53   28.51 4815.51   27.46
 4859.31   27.42 4931.08   28.34 4966.55   25.76 4996.72   13.35 4998.11   13.34
 5006.79   13.36 5033.45   26.17 5063.31   28.38 5218.12   28.27 5270.25   29.56
 5372.88   29.99 5381.42   28.47 5401.65   26.71 5422.88   20.67 5442.55   20.05
 5445.66   19.42 5465.33   24.31  5483.5   25.24    5512   29.52 5649.37   30.66
#Mann= 3 ,-1 , 0
 4050.26     .15       0 4966.55    .015       0 5033.45     .15       0
#XS Ineff= 2 , 0
       0    4959    26.4    5039       0    26.9
Permanent Ineff=
       F       F
#Block Obstruct= 2 ,-1
                         5371.48 5649.37   29.93
Bank Sta=4966.55,5033.45
XS Rating Curve= 0
Exp/Cntr=.5,.3