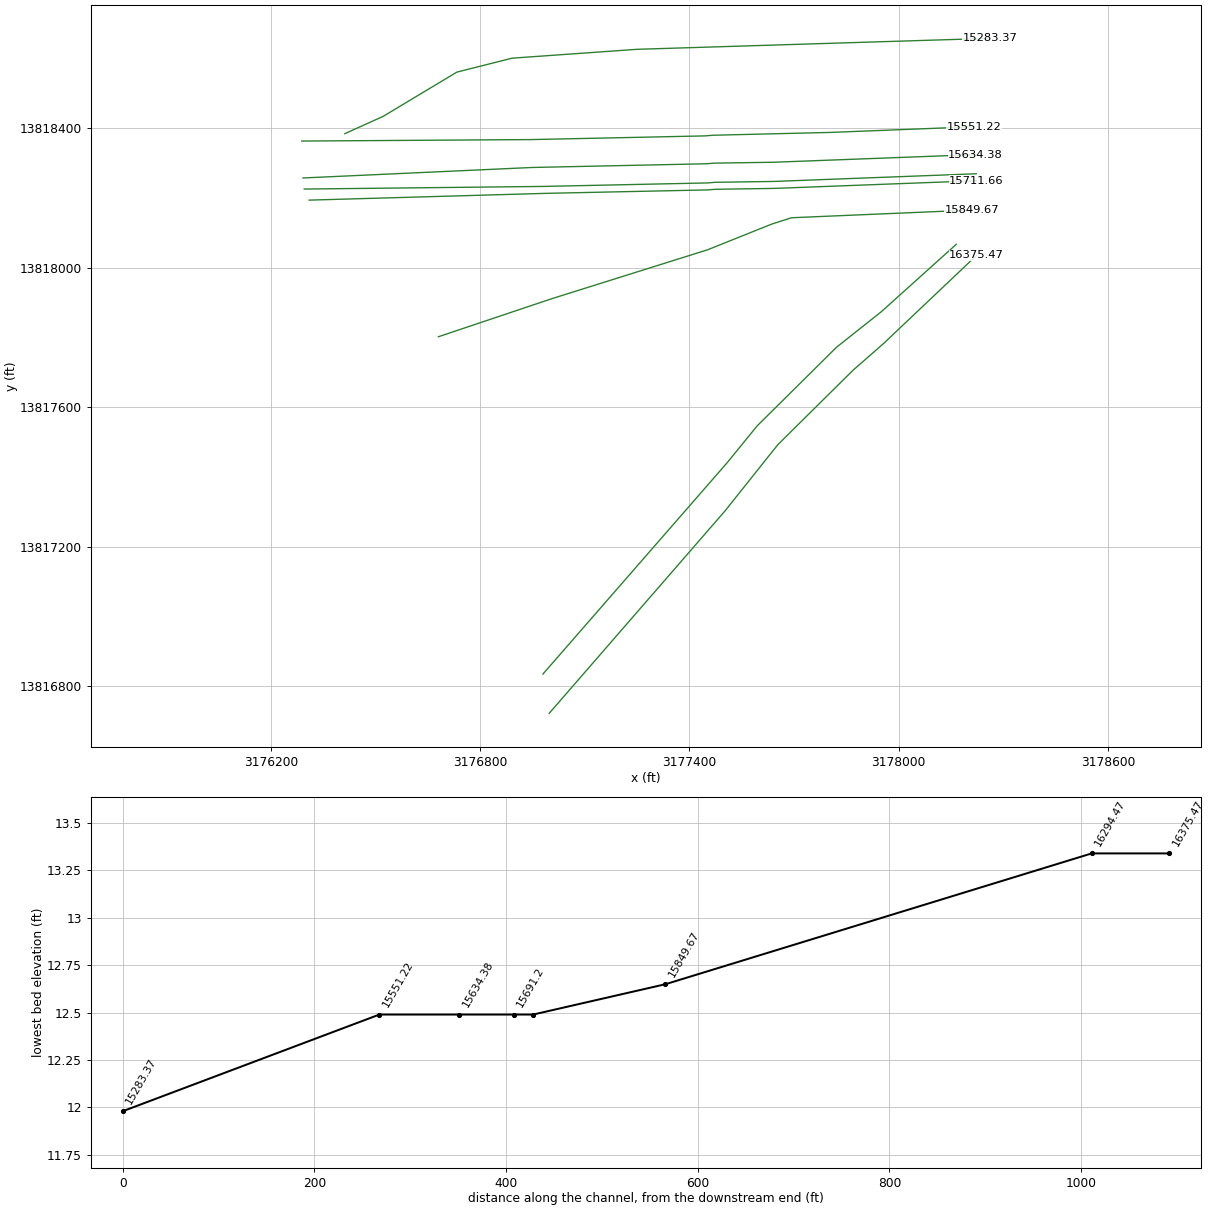
HEC-RAS study I101-00-00.prj: I101-00-00

--- I101-00-00.g03 (geometry) --- (continued)

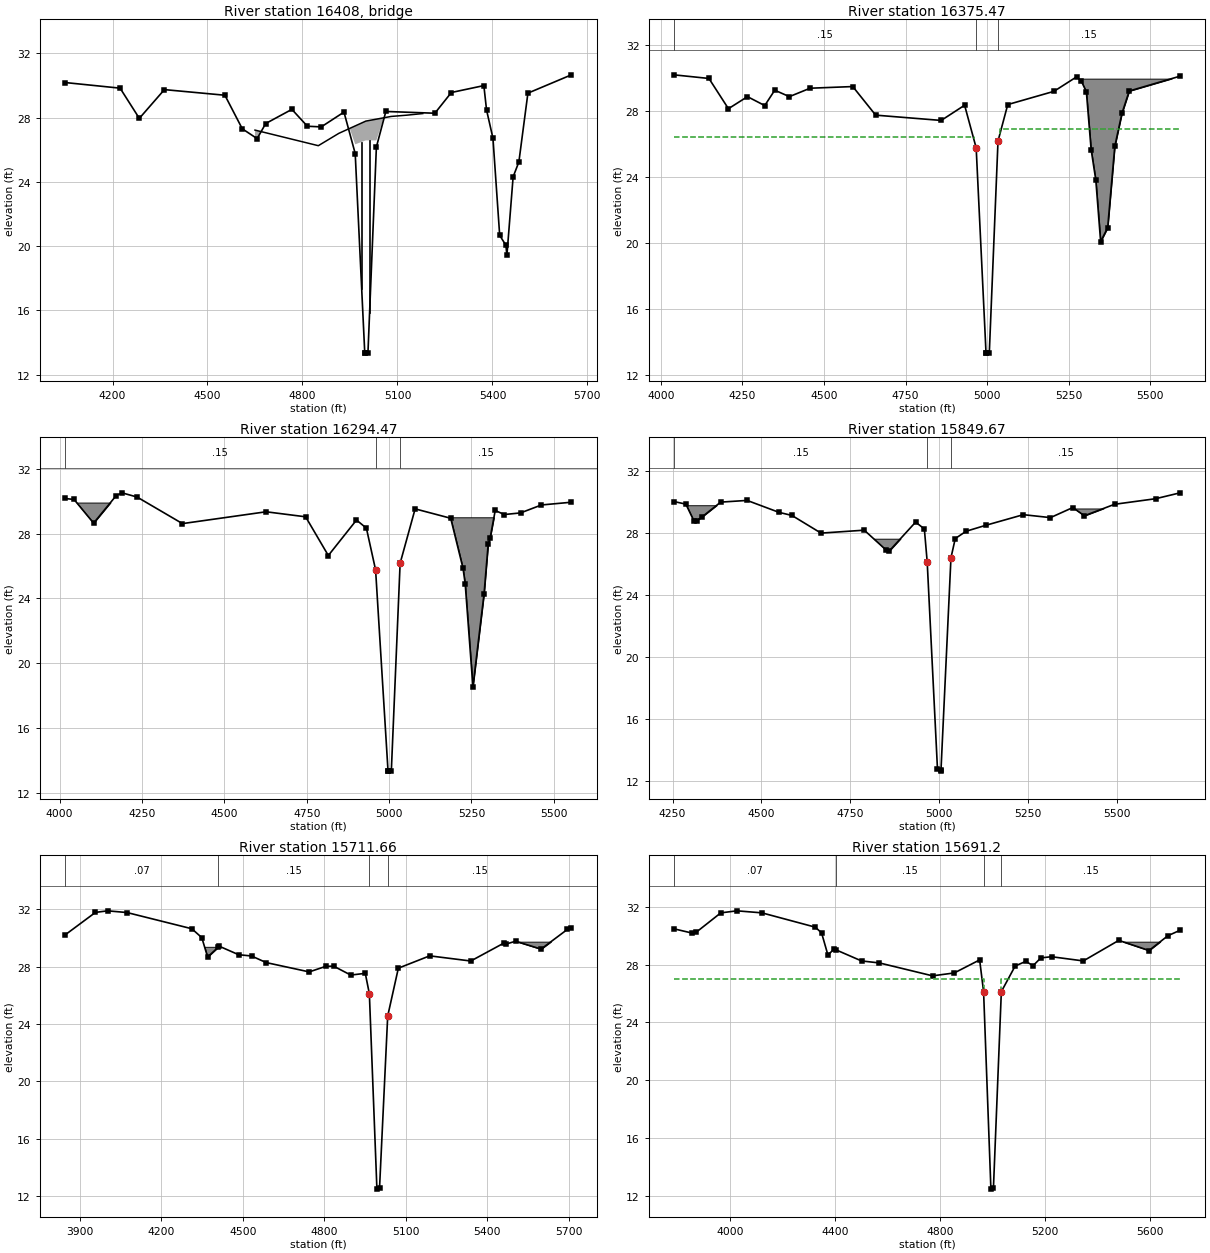
Type RM Length L Ch R = 3 ,16408   ,,,
BEGIN DESCRIPTION:
MARTHA LN
END DESCRIPTION:
Bridge Culvert--1,0,-1,-1, 0
Deck Dist Width WeirC Skew NumUp NumDn MinLoCord MaxHiCord MaxSubmerge Is_Ogee
10,40,2.6,0, 7, 7, , , .95, 0, 0,0,,
    4650    4850    4915    5000    5080    5130    5180
   27.22   26.25   27.02   27.78   28.07   28.15   28.25
           25.97   25.96   26.58   26.58
    4650    4850    4915    5000    5080    5130    5180
   27.22   26.25   27.02   27.78   28.07   28.15   28.25
           25.97   25.96   26.58   26.58
Pier Skew, UpSta & Num, DnSta & Num=  ,4987, 4 ,4987, 4 , 3 , 3 , 0 ,,
     1.2     1.2       2       2
      13   24.49    24.5      27
     1.2     1.2       2       2
      13   24.49    24.5      27
Pier Skew, UpSta & Num, DnSta & Num=  ,5012, 4 ,5012, 4 , 3 , 3 , 0 ,,
     1.2     1.2       2       2
      13   24.49    24.5      27
     1.2     1.2       2       2
      13   24.49    24.5      27
BR Coef=-1 , 1 , 0 ,, 0 ,,,.8,-1,2,0,
WSPro=,,,, 1 ,,,, 0 ,,,, 0 ,,,,-1 ,-1 ,-1 , 0 , 0 , 0 , 0 , 0
BC Design=,, 0 ,, 0 ,,,,,,
BC HTab HWMax=30.66

Type RM Length L Ch R = 1 ,16375.47,81.1,81.01,74.61
XS GIS Cut Line= 6
      3176998.17    13816722.233     3177502.299    13817302.575
     3177653.931    13817492.773     3177869.201    13817705.822
     3177956.581    13817782.331     3178223.606    13818035.379
#Sta/Elev= 30
 4039.94   30.18  4147.6   29.96 4207.31   28.13 4265.61   28.86 4318.57   28.32
 4349.24   29.25 4394.08   28.86 4457.68   29.37  4588.4   29.47 4658.54   27.74
 4859.31   27.42 4931.08   28.34 4966.55   25.76 4996.72   13.35 4998.11   13.34
 5006.79   13.36 5033.45   26.17 5063.31   28.38 5204.81   29.18 5274.47   30.06
 5288.78    29.8 5304.25   29.15 5318.84   25.66 5333.18   23.81 5347.94   20.09
 5369.53   20.93 5391.34   25.85 5413.14   27.84 5435.55    29.2 5591.49    30.1
#Mann= 3 ,-1 , 0
 4039.94     .15       0 4966.55    .015       0 5033.45     .15       0
#XS Ineff= 2 , 0
       0    4959    26.4    5039       0    26.9
Permanent Ineff=
       F       F
#Block Obstruct= 1 ,-1
 5274.85 5591.49   29.95
Bank Sta=4966.55,5033.45
XS Rating Curve= 0
Exp/Cntr=.5,.3

Type RM Length L Ch R = 1 ,16294.47,619.96,444.8,352.36
XS GIS Cut Line= 6
      3176980.53    13816835.162     3177509.755    13817442.353
     3177594.575    13817546.579     3177822.111    13817771.995
     3177950.213    13817873.612     3178165.612    13818067.276
#Sta/Elev= 30
 4016.55   30.17 4043.71   30.11 4103.01   28.65 4171.72   30.35 4189.19   30.52
 4235.01   30.26 4372.77   28.62 4626.59   29.35 4746.59   29.04 4815.51   26.65
    4901   28.84 4931.08   28.34    4959   25.76 4996.72   13.35 4998.11   13.34
 5006.79   13.36 5033.45   26.17    5079   29.53 5186.98   28.95 5224.39   25.86
 5230.98    24.9 5254.41   18.55 5288.26   24.29 5300.79   27.36 5306.79   27.75
 5322.12   29.43 5349.58   29.18 5398.96   29.28 5462.26   29.77 5553.32   29.94
#Mann= 3 ,-1 , 0
 4016.55     .15       0    4959    .015       0 5033.45     .15       0
#Block Obstruct= 2 ,-1
 4030.25 4173.11   29.92 5179.74 5381.65   29.01
Bank Sta=4959,5033.45
XS Rating Curve= 0
Exp/Cntr=.3,.1

Type RM Length L Ch R = 1 ,15849.67,247.01,138.01,88.22
XS GIS Cut Line= 6
      3176680.56    13817802.117     3177005.363    13817911.112
     3177453.043    13818051.663     3177636.372    13818125.153
     3177693.267    13818143.327     3178211.646    13818165.453
#Sta/Elev= 30
 4253.43   30.05 4287.31   29.88 4310.41   28.78 4317.41   28.81 4332.52   29.05
 4385.36   30.01 4459.75   30.12 4549.44   29.35  4585.9   29.15 4667.74   28.01
 4789.42    28.2 4850.88   26.92 4859.08   26.84 4933.97   28.72 4958.58   28.28
 4966.54   26.16 4995.48   12.79 5004.22   12.65 5005.36   12.71 5033.46   26.42
 5045.56   27.66 5076.09   28.13 5130.76   28.51 5237.19    29.2 5313.44   29.01
 5376.41   29.66 5408.89   29.13 5493.78   29.87 5609.43   30.23 5678.36   30.61
#Mann= 3 ,-1 , 0
 4253.43     .15       0 4966.54    .015       0 5033.46     .15       0
#Block Obstruct= 3 ,-1
 4242.02 4388.24   29.81 5376.41 5470.55    29.6    4800    4900   27.65
Bank Sta=4966.54,5033.46
XS Rating Curve= 0
Exp/Cntr=.3,.1

Type RM Length L Ch R = 1 ,15711.66,20.33,20.46,20.72
XS GIS Cut Line= 6
      3176310.01     13818193.84      3176991.08    13818213.336
     3177453.394    13818223.163     3177474.752    13818224.958
     3177642.648    13818227.432     3178223.507    13818249.433
#Sta/Elev= 30
 3845.37   30.22 3957.09   31.79 4002.03    31.9 4073.56   31.78 4312.21   30.65
 4348.97   30.03 4370.32   28.68 4408.71   29.35 4413.37   29.43 4484.67   28.84
 4532.08   28.75 4586.24   28.29  4744.7   27.64 4805.96   28.03  4834.7   28.04
 4897.72   27.42 4951.19   27.54 4966.22   26.12 4994.05   12.49 5003.69   12.56
 5033.78   24.56    5073    27.9 5188.49   28.76 5339.81    28.4 5463.74   29.67
 5469.31   29.58    5505   29.78 5598.74   29.23 5695.41    30.6 5710.49   30.67
#Mann= 4 ,-1 , 0
 3845.37     .07       0 4408.71     .15       0 4966.22    .015       0
 5033.78     .15       0
#Block Obstruct= 2 ,-1
 4342.65 4413.48   29.39 5506.02 5681.31   29.75
Bank Sta=4966.22,5033.78
XS Rating Curve= 0
Exp/Cntr=.5,.3

Type RM Length L Ch R = 1 ,15691.2 ,55.9,56.82,56.97
XS GIS Cut Line= 6
       3176295.9    13818225.601     3176980.523    13818233.116
     3177452.343    13818243.146      3177473.78    13818244.947
     3177642.155    13818247.427     3178222.714    13818269.417
#Sta/Elev= 30
 3786.86   30.47 3857.22   30.17 3872.75   30.24 3965.78   31.57 4027.19   31.71
 4122.34   31.57  4325.8   30.58 4349.49   30.18 4373.53   28.66 4397.22   29.07
 4403.65   29.02 4501.47   28.25 4569.86   28.11 4771.88   27.22 4854.58   27.42
 4951.19   28.32 4966.22   26.12 4994.05   12.49 5003.69   12.56 5033.78   26.13
 5086.43    27.9 5126.91   28.22 5154.52   27.92  5184.2   28.46 5225.02   28.54
 5345.88   28.25 5480.95   29.67 5595.97   28.97  5667.9   29.99 5714.34   30.37
#Mann= 4 ,-1 , 0
 3786.86     .07       0 4403.65     .15       0 4966.22    .015       0
 5033.78     .15       0
#XS Ineff= 2 , 0
       0 4966.22      27 5033.78       0      27
Permanent Ineff=
       F       F
#Block Obstruct= 1 ,-1
  5481.2 5670.04   29.58
Bank Sta=4966.22,5033.78
XS Rating Curve= 0
Exp/Cntr=.5,.3

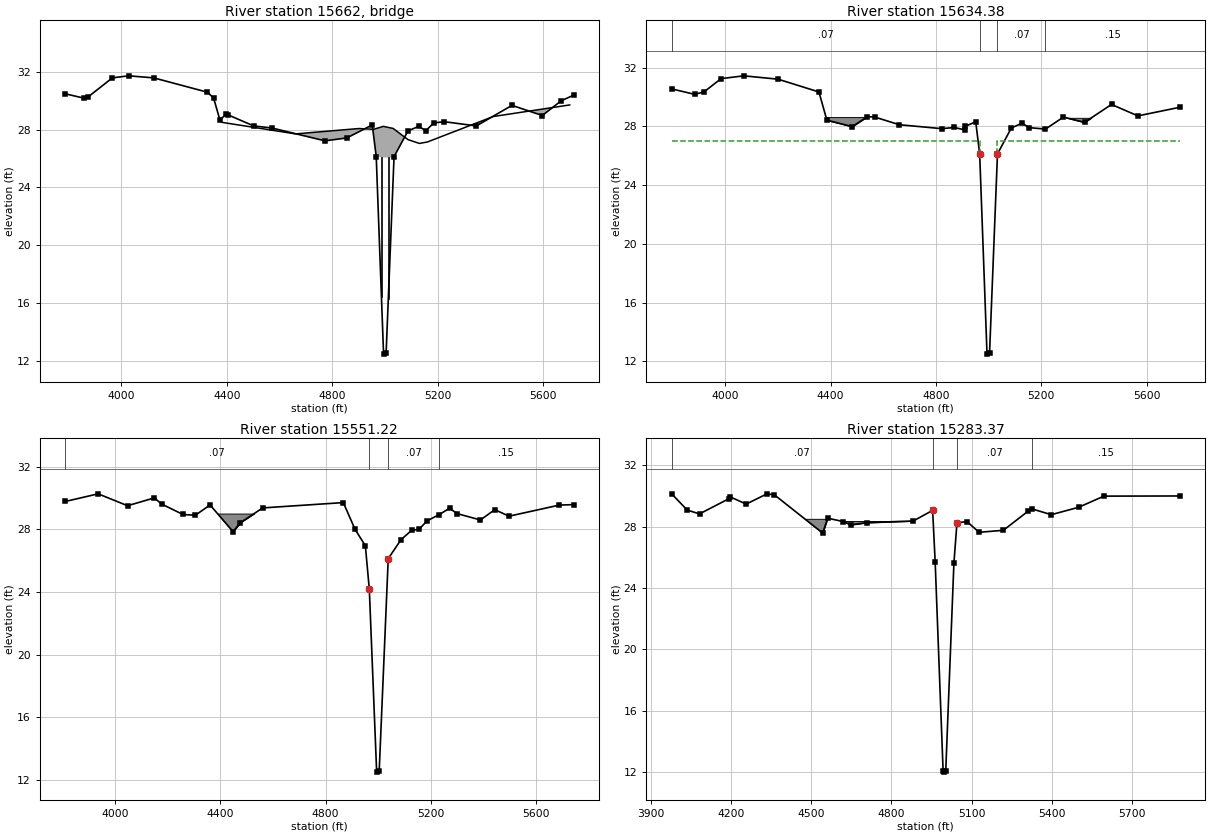
Type RM Length L Ch R = 3 ,15662   ,,,
BEGIN DESCRIPTION:
BLAKE ST
END DESCRIPTION:
Bridge Culvert--1,0,-1,-1, 0
Deck Dist Width WeirC Skew NumUp NumDn MinLoCord MaxHiCord MaxSubmerge Is_Ogee
9,37,2.6,0, 11, 11, , , .95, 0, 0,0,,
    4380    4660    4900    4957    4993    5030    5087    5130    5160    5410
    5700
    28.5    27.7   28.07   28.02   28.22   28.08    27.3   27.04   27.14    28.9
    29.7
                           26.07   26.07   26.07   26.07
        
    4380    4660    4900    4957    4993    5030    5087    5130    5160    5410
    5700
    28.5    27.7   28.07   28.02   28.22   28.08    27.3   27.04   27.14    28.9
    29.7
                           26.07   26.07   26.07   26.07
        
Pier Skew, UpSta & Num, DnSta & Num=  ,4986, 4 ,4986, 4 , 3 , 3 , 0 ,,
     1.2     1.2       2       2
      12   24.06   24.07    26.5
     1.2     1.2       2       2
      12   24.06   24.07    26.5
Pier Skew, UpSta & Num, DnSta & Num=  ,5012, 4 ,5012, 4 , 3 , 3 , 0 ,,
     1.2     1.2       2       2
      12   24.06   24.07    26.5
     1.2     1.2       2       2
      12   24.06   24.07    26.5
BR Coef=-1 , 1 , 0 ,, 0 ,,,.8,-1,2,0,
WSPro=,,,, 1 ,,,, 0 ,,,, 0 ,,,,-1 ,-1 ,-1 , 0 , 0 , 0 , 0 , 0
BC Design=,, 0 ,, 0 ,,,,,,
BC HTab HWMax=31.71

Type RM Length L Ch R = 1 ,15634.38,81.32,83.16,82.86
XS GIS Cut Line= 6
      3176292.37    13818257.362     3176948.807    13818287.454
     3177449.453    13818298.097     3177471.107    13818299.916
     3177640.801    13818302.413     3178220.536    13818324.374
#Sta/Elev= 30
 3797.08   30.56 3883.77   30.19  3919.4   30.35 3984.83   31.26 4070.97   31.45
 4201.21   31.22 4356.12   30.35 4386.15   28.43 4482.36   27.99 4539.88   28.67
 4567.95   28.64 4661.13   28.12 4822.42   27.85  4870.3   27.93 4910.93   27.76
  4911.8   28.01 4951.19   28.32 4966.22   26.12 4994.05   12.49 5003.69   12.56
 5033.78   26.13 5086.43    27.9 5126.91   28.22 5154.52   27.92 5215.75   27.82
 5284.24   28.64 5364.24   28.28 5466.59    29.5 5566.72   28.72 5726.57   29.31
#Mann= 4 ,-1 , 0
 3797.08     .07       0 4966.22    .015       0 5033.78     .07       0
 5215.75     .15       0
#XS Ineff= 2 , 0
       0 4966.22      27 5033.78       0      27
Permanent Ineff=
       F       F
#Block Obstruct= 2 ,-1
 4373.55 4538.64   28.64 5284.45 5403.79   28.59
Bank Sta=4966.22,5033.78
XS Rating Curve= 0
Exp/Cntr=.5,.3

Type RM Length L Ch R = 1 ,15551.22,249.04,267.85,265.89
XS GIS Cut Line= 6
      3176288.84    13818363.233     3176948.831    13818367.472
      3177445.25    13818378.025     3177467.219    13818379.871
     3177807.231    13818388.052     3178217.367    13818404.311
#Sta/Elev= 30
 3812.06   29.78 3937.14   30.27 4048.58   29.51  4150.4   30.01 4177.61   29.62
 4259.08   28.95 4305.87    28.9 4361.79   29.56 4449.06   27.85 4476.88   28.43
 4561.69   29.37 4867.49   29.71  4911.8   28.01 4951.19   26.95 4966.22   24.16
 4994.05   12.49 5003.69   12.56    5038   26.13 5086.43   27.34 5126.91   27.94
 5154.52      28 5186.02   28.55 5230.96   28.94 5270.99   29.35 5298.61   29.01
  5387.8    28.6 5442.56   29.26 5496.14   28.84 5687.06   29.55 5741.22   29.58
#Mann= 4 ,-1 , 0
 3812.06     .07       0 4966.22    .015       0    5038     .07       0
 5230.96     .15       0
#Block Obstruct= 1 ,-1
 4378.78 4532.69   29.01
Bank Sta=4966.22,5038
XS Rating Curve= 0
Exp/Cntr=.3,.1

Type RM Length L Ch R = 1 ,15283.37,20.32,21.68,20.74
XS GIS Cut Line= 6
      3176412.35    13818384.407     3176522.057    13818433.915
       3176733.5    13818560.859     3176891.973    13818600.859
     3177249.907    13818626.258     3178262.949    13818657.742
#Sta/Elev= 30
    3977   30.14  4035.1   29.08 4081.22   28.83 4190.03   29.81 4194.75   29.95
 4256.07   29.47 4334.06   30.14 4362.02   30.07 4542.45   27.58 4561.25   28.55
 4619.82   28.33 4647.72   28.12 4707.43   28.26 4882.07   28.37 4954.42   29.06
 4963.91   25.69 4993.64   12.05 4998.81   11.98 5003.44   12.03 5034.11   25.63
 5045.58   28.25 5083.02   28.33 5128.34   27.63 5219.35   27.76 5311.39      29
 5327.68   29.15 5398.79   28.78 5500.81   29.26 5596.01   29.99 5880.88      30
#Mann= 4 ,-1 , 0
    3977     .07       0 4954.42    .015       0 5045.58     .07       0
 5327.68     .15       0
#Block Obstruct= 2 ,-1
 4455.12 4561.88   28.51 4580.26 4909.41   28.37
Bank Sta=4954.42,5045.58
XS Rating Curve= 0
Exp/Cntr=.5,.3