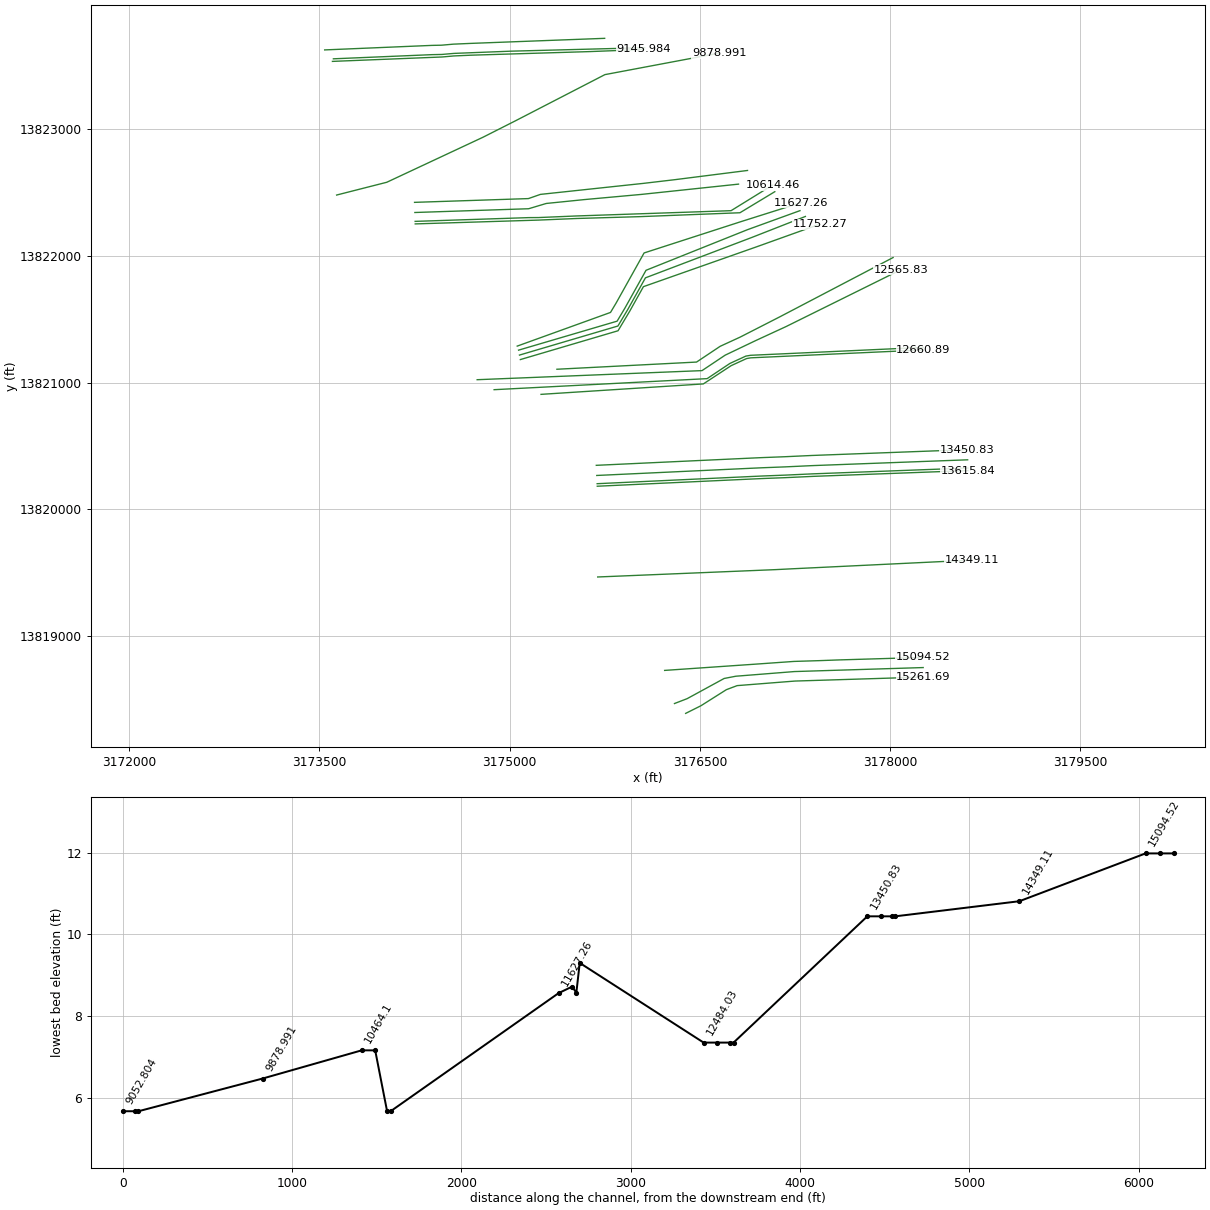
HEC-RAS study I101-00-00.prj: I101-00-00

--- I101-00-00.g03 (geometry) --- (continued)

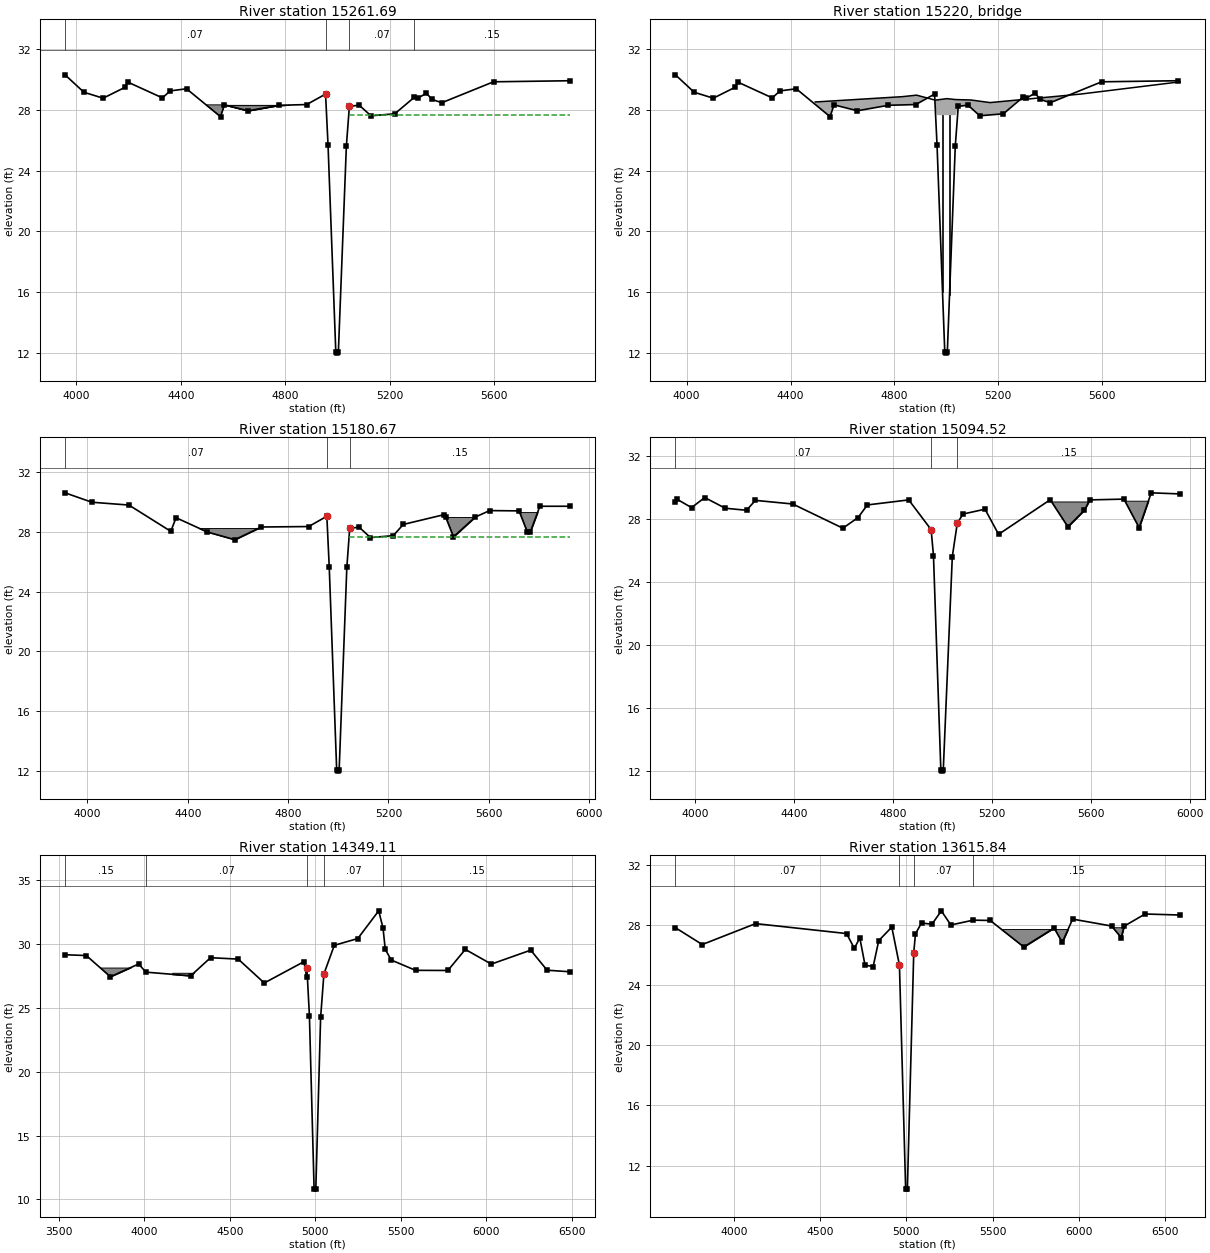
Type RM Length L Ch R = 1 ,15261.69,76.19,81.02,77.65
XS GIS Cut Line= 6
      3176387.65    13818391.465     3176507.642    13818451.459
     3176708.797    13818578.504     3176793.494    13818610.266
      3177248.89    13818646.236     3178262.354    13818677.733
#Sta/Elev= 30
 3956.55   30.33 4028.92   29.18 4102.48   28.79 4185.57    29.5 4197.06   29.85
 4329.47   28.81 4359.32   29.27 4421.92   29.41 4552.07   27.57 4567.26   28.35
 4657.34   27.96 4776.26   28.32 4882.07   28.37 4954.42   29.06 4963.91   25.69
 4993.64   12.05 4998.81   11.98 5003.44   12.03 5034.11   25.63 5045.58   28.25
 5083.02   28.33 5128.34   27.63 5219.35   27.76  5293.8   28.84 5307.75   28.79
 5340.95   29.12 5361.77   28.71 5399.63   28.49 5597.71   29.87 5889.91   29.94
#Mann= 4 ,-1 , 0
 3956.55     .07       0 4954.42    .015       0 5045.58     .07       0
  5293.8     .15       0
#XS Ineff= 2 , 0
       0    4958   27.66    5043       0    27.7
Permanent Ineff=
       F       F
#Block Obstruct= 3 ,-1
 4482.87  4567.7   28.35 4567.71 4813.56   28.35 4568.26 4814.99   28.33
Bank Sta=4954.42,5045.58
XS Rating Curve= 0
Exp/Cntr=.5,.3

Type RM Length L Ch R = 3 ,15220   ,,,
BEGIN DESCRIPTION:
SOUTHMORE AVE
END DESCRIPTION:
Bridge Culvert--1,0,-1,-1, 0
Deck Dist Width WeirC Skew NumUp NumDn MinLoCord MaxHiCord MaxSubmerge Is_Ogee
10,60,2.6,0, 10, 10, , , .95, 0, 0,0,,
    4495    4830    4885    4957    5002    5035    5095    5168    5516    5900
   28.54   28.89   28.99   28.66   28.76    28.7   28.67    28.5   29.06   29.87
                           27.67   27.67   27.67   27.67
    4495    4830    4885    4957    5002    5035    5095    5168    5516    5900
   28.54   28.89   28.99   28.66   28.76    28.7   28.67    28.5   29.06   29.87
                           27.67   27.67   27.67   27.67
Pier Skew, UpSta & Num, DnSta & Num=  ,4985, 2 ,4985, 2 , 0 , 0 , 0 ,,
       2       2
      11    28.5
       2       2
      11    28.5
Pier Skew, UpSta & Num, DnSta & Num=  ,5012, 2 ,5012, 2 , 0 , 0 , 0 ,,
       2       2
      11    28.5
       2       2
      11    28.5
BR Coef=-1 , 1 , 0 ,, 0 ,,,.8,-1,2,0,
WSPro=,,,, 1 ,,,, 0 ,,,, 0 ,,,,-1 ,-1 ,-1 , 0 , 0 , 0 , 0 , 0
BC Design=,, 0 ,, 0 ,,,,,,
BC HTab HWMax=30.33

Type RM Length L Ch R = 1 ,15180.67,81.27,86.15,82.79
XS GIS Cut Line= 6
      3176299.42    13818469.104     3176399.222    13818507.492
     3176691.152     13818666.73     3176782.907    13818684.375
     3177245.078    13818721.155     3178260.124      13818752.7
#Sta/Elev= 30
 3910.56   30.63 4017.48      30 4165.42   29.81 4332.14   28.05  4353.3   28.96
  4477.3   28.01 4587.54   27.49  4692.8   28.34 4882.07   28.37 4954.42   29.06
 4963.91   25.69 4993.64   12.05 4998.81   11.98 5003.44   12.03 5034.11   25.63
 5045.58   28.25 5083.02   28.33 5128.34   27.63 5219.35   27.76 5259.01   28.51
 5420.06   29.16 5428.61   28.99 5459.23   27.68 5545.59      29 5603.49   29.44
 5720.75   29.42 5753.72      28 5765.78   28.02 5803.78   29.73 5923.13   29.73
#Mann= 3 ,-1 , 0
 3910.56     .07       0 4954.42    .015       0 5045.58     .15       0
#XS Ineff= 2 , 0
       0    4958   27.66    5043       0    27.7
Permanent Ineff=
       F       F
#Block Obstruct= 3 ,-1
 4439.03 4685.52   28.27 5417.25 5648.69   29.01 5712.45 5839.97   29.34
Bank Sta=4954.42,5045.58
XS Rating Curve= 0
Exp/Cntr=.5,.3

Type RM Length L Ch R = 1 ,15094.52,746.73,745.41,747.22
XS GIS Cut Line= 6
      3176221.79    13818730.253     3176931.167    13818779.081
     3177241.011    13818801.067     3177444.681    13818807.341
     3177590.192    13818812.737     3178257.746    13818832.664
#Sta/Elev= 30
  3921.7   29.09 3927.49   29.28 3986.84   28.74 4040.32   29.38  4122.9    28.7
 4209.12   28.57 4244.51    29.2 4395.46   28.97 4598.04   27.43 4659.49   28.11
 4696.93   28.91    4864   29.23 4954.42   27.34 4963.91   25.69 4993.64   12.05
 4998.81   11.98 5003.44   12.03    5040   25.63    5060   27.74 5083.02   28.33
 5172.03   28.64 5226.85   27.04 5435.33   29.24 5506.64   27.52 5572.97   28.57
 5595.24   29.23  5732.9   29.28 5794.45   27.46 5843.23   29.68  5960.2   29.61
#Mann= 3 ,-1 , 0
  3921.7     .07       0 4954.42    .015       0    5060     .15       0
#Block Obstruct= 3 ,-1
                         5434.91 5606.87   29.13 5730.38 5857.62   29.18
Bank Sta=4954.42,5060
XS Rating Curve= 0
Exp/Cntr=.3,.1

Type RM Length L Ch R = 1 ,14349.11,725.53,733.27,724.62
XS GIS Cut Line= 4
     3175693.998    13819466.846     3177095.878    13819524.831
     3177232.314    13819531.653     3178644.427    13819599.871
#Sta/Elev= 30
 3535.09   29.16 3659.61    29.1  3800.5   27.44 3966.26   28.44 4007.64    27.8
 4270.25   27.51 4386.38   28.93 4548.39   28.82 4700.84   26.95 4933.11   28.62
 4948.13   27.44  4950.2   28.13 4964.94    24.4 4992.43   10.81 5002.49   10.85
 5030.54   24.25  5049.8   27.66 5110.66    29.9    5248   30.43 5370.41    32.6
 5395.76   31.25  5408.7   29.59 5443.33   28.75 5586.11   27.94  5775.2   27.93
 5877.02   29.58 6029.38   28.43 6259.82   29.52 6355.77   27.95 6488.53   27.83
#Mann= 5 ,-1 , 0
 3535.09     .15       0 4007.64     .07       0  4950.2    .015       0
  5049.8     .07       0 5395.76     .15       0
#Block Obstruct= 2 ,-1
  3695.9  3938.1   28.16 4162.23 4317.66   27.75
Bank Sta=4950.2,5049.8
XS Rating Curve= 0
Exp/Cntr=.3,.1

Type RM Length L Ch R = 1 ,13615.84,20.03,20,20.02
XS GIS Cut Line= 6
     3175690.629    13820182.368     3176889.961    13820238.329
     3176992.305    13820242.987     3177175.349    13820250.079
     3177390.726    13820260.044     3178613.978    13820305.781
#Sta/Elev= 30
 3661.36   27.81 3817.01   26.69 4126.19   28.08 4653.38   27.42 4698.58   26.44
 4730.36   27.13 4760.57   25.32  4807.8   25.23    4840   26.95 4915.73   27.85
    4960   25.32 4996.01   10.44 5006.03   10.47    5043   26.16    5053   27.41
 5088.07   28.12 5148.71   28.04 5202.77   28.93 5258.07   27.99 5387.69   28.31
 5486.18   28.29 5680.83   26.53 5856.57   27.79 5903.72   26.83 5963.83   28.38
 6189.79   27.92 6245.52   27.15 6262.35   27.91 6384.05   28.72 6587.35   28.65
#Mann= 4 ,-1 , 0
 3661.36     .07       0    4960    .015       0    5043     .07       0
 5387.69     .15       0
#Block Obstruct= 5 ,-1
                                                 5505.49 5855.95   27.72
 5857.88 5976.64   27.72 6171.66 6307.79   27.84
Bank Sta=4960,5043
XS Rating Curve= 0
Exp/Cntr=.5,.3

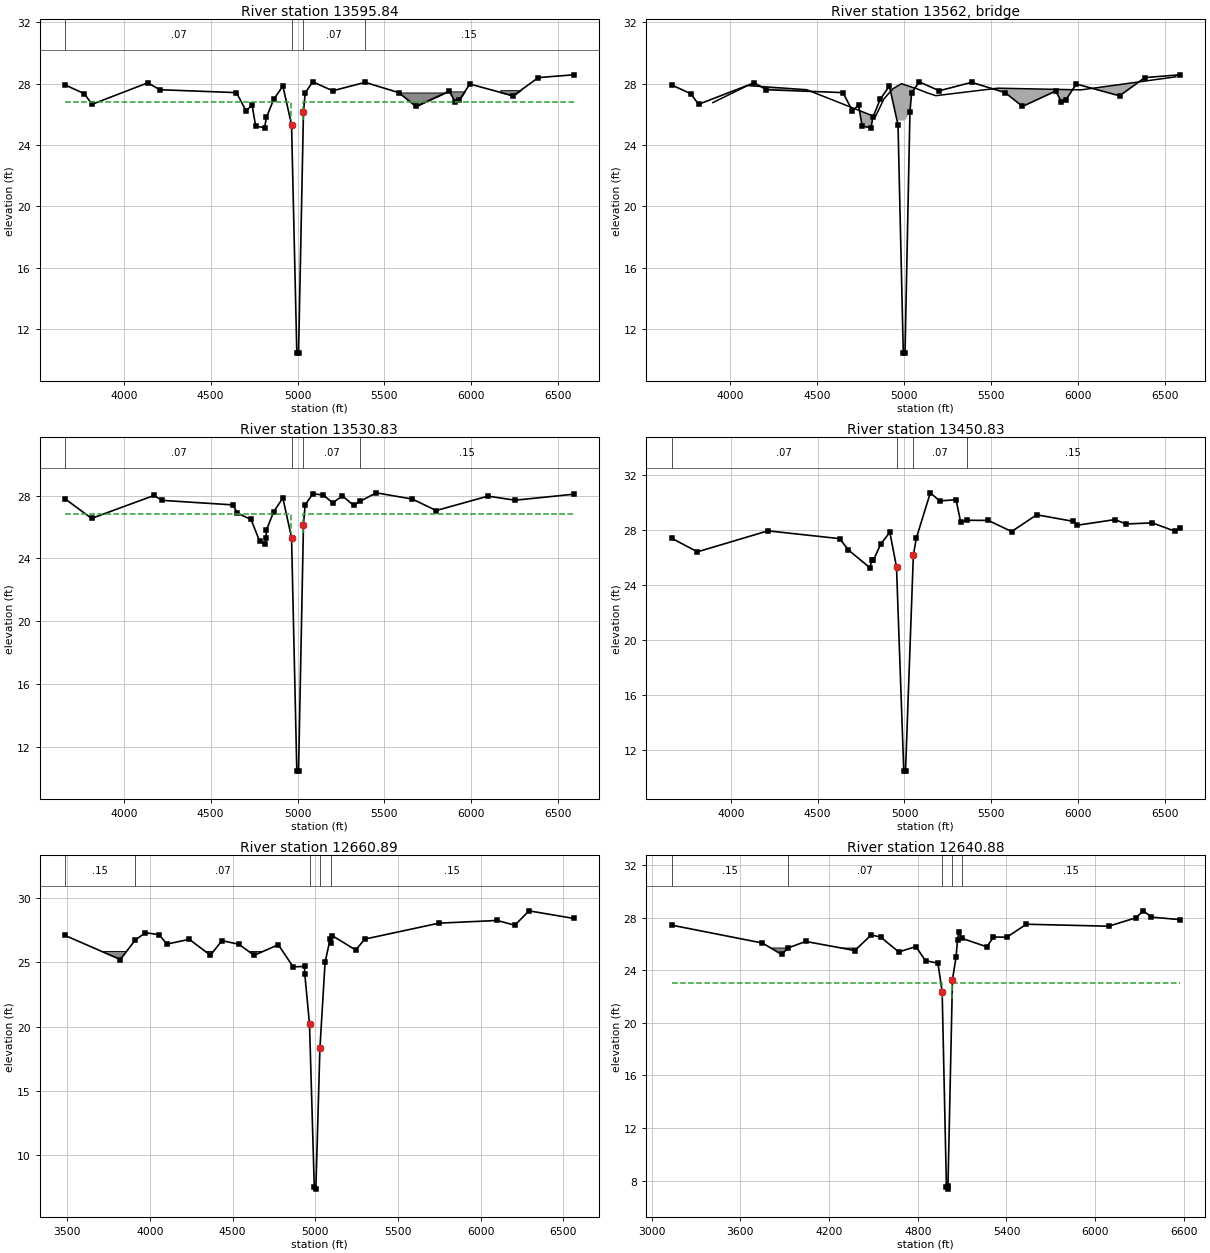
Type RM Length L Ch R = 1 ,13595.84,65.09,65.01,65.06
XS GIS Cut Line= 6
     3175689.697    13820202.346      3176889.04    13820258.307
     3176991.539    13820262.973     3177174.454    13820270.059
      3177389.89    13820280.027      3178613.23    13820325.767
#Sta/Elev= 30
 3662.74   27.92 3772.36   27.35 3817.51   26.66 4138.45   28.06  4207.1   27.61
 4648.66   27.42 4703.13   26.24 4738.74    26.6 4758.91   25.24 4810.12   25.13
 4821.37   25.82 4863.03   26.98 4915.73   27.85 4965.68   25.32 4996.01   10.44
 5006.03   10.47 5034.32   26.16 5044.01   27.41 5088.07   28.12 5202.77   27.54
 5389.18   28.09 5582.69   27.42 5682.03   26.52 5873.25   27.52 5906.03   26.84
 5930.68   26.93 5992.05   27.98 6241.24   27.21 6386.37    28.4 6588.91   28.58
#Mann= 4 ,-1 , 0
 3662.74     .07       0 4965.68    .015       0 5034.32     .07       0
 5389.18     .15       0
#XS Ineff= 2 , 0
       0    4960    26.8  5033.4       0    26.8
Permanent Ineff=
       F       F
#Block Obstruct= 5 ,-1
                                                 5566.39 5869.78   27.43
 5869.78 6040.22    27.5 6167.14 6324.27   27.58
Bank Sta=4965.68,5034.32
XS Rating Curve= 0
Exp/Cntr=.5,.3

Type RM Length L Ch R = 3 ,13562   ,,,
BEGIN DESCRIPTION:
JENKINS RD
END DESCRIPTION:
Bridge Culvert--1,0,-1,-1, 0
Deck Dist Width WeirC Skew NumUp NumDn MinLoCord MaxHiCord MaxSubmerge Is_Ogee
8,38,2.6,0, 13, 13, , , .95, 0, 0,0,,
    3900    4100    4440    4835    4885    4937    4985    5077    5130    5183
    5540    6020    6565
   26.77   27.88   27.61   25.84   27.02   27.68      28   27.66   27.42   27.22
   27.71    27.6   28.45
                            25.6    25.6    25.6    25.6    25.6    25.6    25.6
                        
    3900    4100    4440    4835    4885    4937    4985    5077    5130    5183
    5540    6020    6565
   26.77   27.88   27.61   25.84   27.02   27.68      28   27.66   27.42   27.22
   27.71    27.6   28.45
                            25.6    25.6    25.6    25.6    25.6    25.6    25.6
                        
BR Coef=-1 , 0 , 0 ,, 0 ,,,.8,-1,,0,
WSPro=,,,, 1 ,,,, 0 ,,,, 0 ,,,,-1 ,-1 ,-1 , 0 , 0 , 0 , 0 , 0
BC Design=,, 0 ,, 0 ,,,,,,
BC HTab HWMax=28.61

Type RM Length L Ch R = 1 ,13530.83,80.11,80,80.08
XS GIS Cut Line= 6
     3175686.668    13820267.276     3176886.048    13820323.238
     3176989.051    13820327.927     3177171.545    13820334.994
     3177387.174    13820344.971     3178610.802    13820390.722
#Sta/Elev= 30
 3662.47   27.79 3814.37   26.55 4173.53   28.01 4220.22    27.7 4628.53   27.41
 4652.82   26.89 4732.52   26.48 4781.84    25.1 4812.88   24.92 4818.52   25.29
 4821.37   25.82 4863.03   26.98 4915.73   27.85 4965.68   25.32 4996.01   10.44
 5006.03   10.47 5034.32   26.16 5044.01   27.41 5088.07   28.12 5148.71   28.04
 5202.77   27.54 5258.07   27.99 5323.37   27.38    5360   27.64 5453.59   28.18
 5661.93   27.78 5798.44   27.05 6096.61   27.97 6252.79   27.71 6589.24   28.09
#Mann= 4 ,-1 , 0
 3662.47     .07       0 4965.68    .015       0 5034.32     .07       0
    5360     .15       0
#XS Ineff= 2 , 0
       0    4960    26.8  5033.4       0    26.8
Permanent Ineff=
       F       F
Bank Sta=4965.68,5034.32
XS Rating Curve= 0
Exp/Cntr=.5,.3

Type RM Length L Ch R = 1 ,13450.83,638.03,789.94,810.16
XS GIS Cut Line= 6
     3175682.939    13820347.189     3176882.365    13820403.154
     3176985.988     13820407.87     3177167.965    13820414.914
     3177383.831    13820424.902     3178607.813    13820470.666
#Sta/Elev= 30
  3659.2   27.41 3807.58   26.42 4213.76   27.95    4627   27.38 4676.59   26.56
 4801.78   25.25 4810.96   25.83 4821.37   25.82 4863.03   26.98 4915.73   27.85
    4954   25.32 4996.01   10.44 5006.03   10.47    5051   26.16    5068   27.41
 5148.71   30.72 5202.77   30.13 5296.89   30.22 5323.83   28.58 5357.16   28.72
  5482.3   28.71 5617.01    27.9 5761.57   29.12 5968.35   28.65 5995.48   28.36
 6212.43   28.77 6275.33   28.45 6427.05   28.53 6558.51   27.92 6586.71   28.18
#Mann= 4 ,-1 , 0
  3659.2     .07       0    4954    .015       0    5051     .07       0
 5357.16     .15       0
Bank Sta=4954,5051
XS Rating Curve= 0
Exp/Cntr=.3,.1

Type RM Length L Ch R = 1 ,12660.89,20.25,20,21.68
XS GIS Cut Line= 6
 3175247.261336713820906.7729681      3176526.89    13820989.005
     3176746.194    13821133.066     3176867.985    13821189.102
     3176901.326    13821194.795     3178261.847    13821257.005
#Sta/Elev= 30
 3487.48   27.09 3820.81   25.22 3910.63   26.73 3972.38   27.31 4055.67   27.15
 4102.61   26.42 4238.14   26.79 4366.04   25.55 4435.39   26.69 4537.15   26.41
 4630.04   25.55 4776.35   26.37  4866.1   24.65 4935.03   24.68 4936.57   24.09
 4965.17   20.18 4994.02    7.49 5003.45    7.35    5028    18.3 5059.34   25.02
 5090.76   26.85 5093.63   26.47  5102.4   27.08 5244.39   25.96 5299.64   26.81
 5747.87   28.05 6099.71   28.26 6207.11   27.89 6292.34   29.01 6562.01   28.42
#Mann= 5 ,-1 , 0
 3487.48     .15       0 3910.63     .07       0 4965.17    .015       0
    5028     .07       0 5093.63     .15       0
#Block Obstruct= 1 ,-1
    3700    4680   25.85
Bank Sta=4965.17,5028
XS Rating Curve= 0
Exp/Cntr=.5,.3

Type RM Length L Ch R = 1 ,12640.88,86.52,75.06,151.63
XS GIS Cut Line= 6
 3174877.278353313820943.5363626     3176556.912    13821030.705
     3176736.305    13821150.504     3176862.126    13821208.392
     3176899.253     13821214.73     3178260.909    13821276.983
#Sta/Elev= 30
 3136.38   27.44 3749.76   26.08 3880.48   25.21 3922.81    25.7 4042.07    26.2
 4375.05   25.51  4486.3    26.7 4550.75   26.52 4671.83    25.4 4787.74   25.81
 4852.54   24.73 4936.57   24.55 4965.17   22.36 4994.02    7.49 5003.45    7.35
 5004.41    7.57 5034.83    23.3 5059.34   25.02    5069   26.34 5077.82   26.92
  5097.5   26.44 5267.72   25.79 5311.81   26.54 5401.88   26.52 5534.63   27.51
 6090.96   27.36 6272.84   27.99 6325.55   28.53 6380.34   28.05 6573.25   27.86
#Mann= 5 ,-1 , 0
 3136.38     .15       0 3922.81     .07       0 4965.17    .015       0
 5034.83     .07       0  5097.5     .15       0
#XS Ineff= 2 , 0
       0    4966      23    5032       0      23
Permanent Ineff=
       F       F
#Block Obstruct= 1 ,-1
    3788    4430    25.7
Bank Sta=4965.17,5034.83
XS Rating Curve= 0
Exp/Cntr=.5,.3

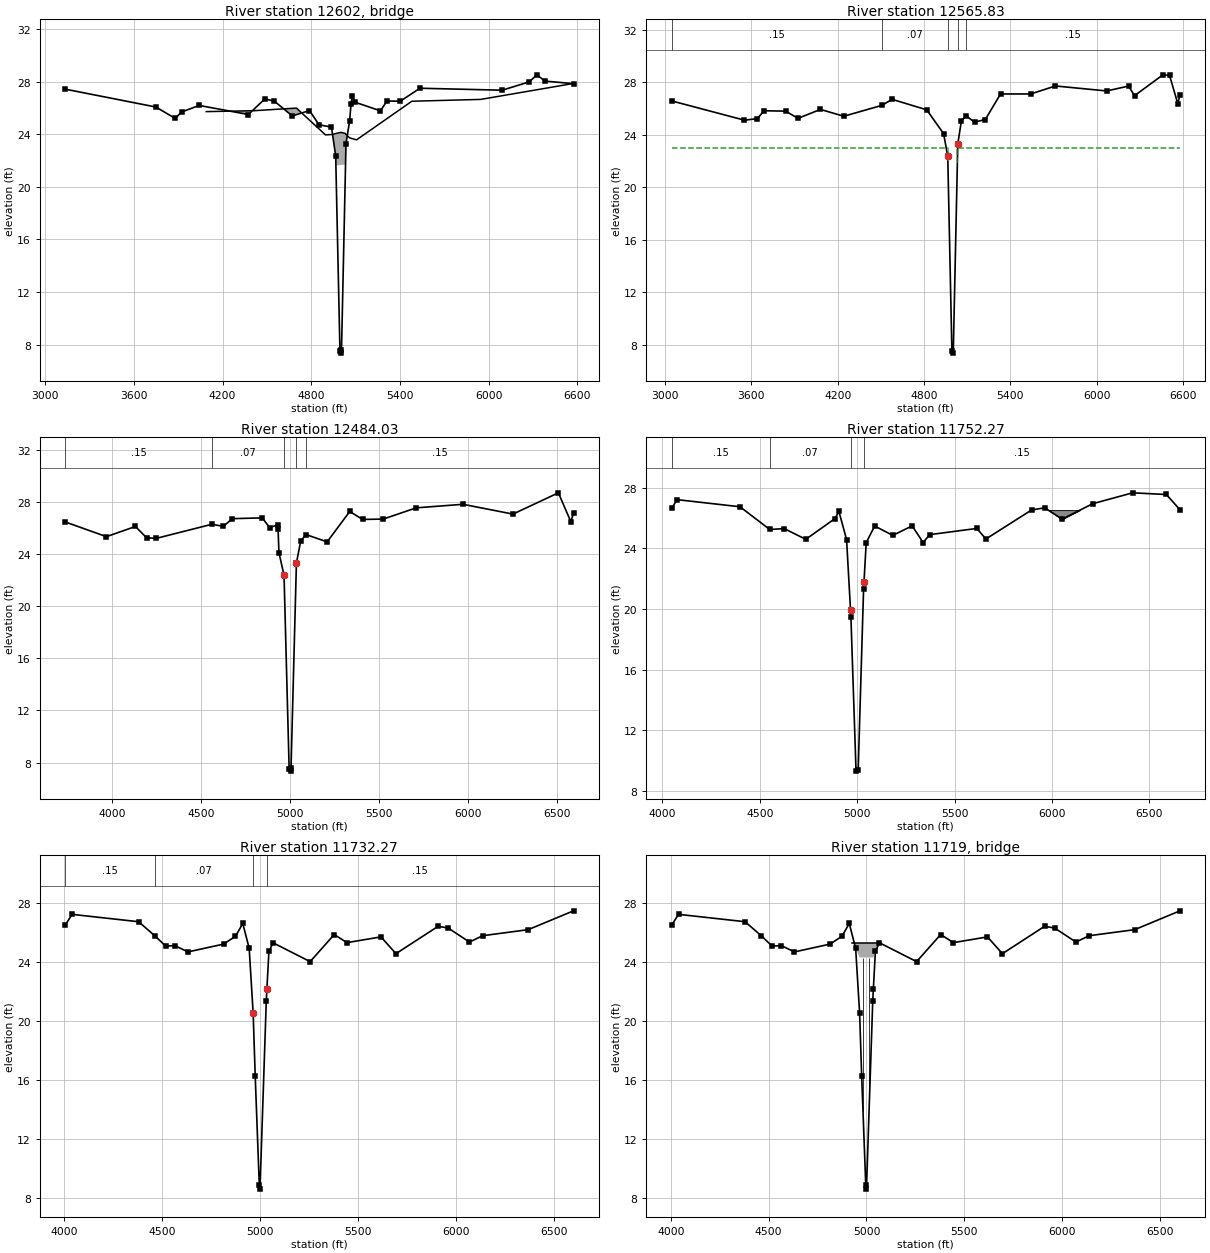
Type RM Length L Ch R = 3 ,12602   ,,,
BEGIN DESCRIPTION:
HARRIS AVE
END DESCRIPTION:
Bridge Culvert--1,0,-1,-1, 0
Deck Dist Width WeirC Skew NumUp NumDn MinLoCord MaxHiCord MaxSubmerge Is_Ogee
5,58,2.6,0, 13, 13, , , .95, 0, 0,0,,
    4090    4414    4700    4896    4944    4968    5000    5028    5058    5106
    5480    5946    6561
   25.73    25.8      26   23.96   23.99   24.07   24.15   24.08   23.74   23.58
   26.52   26.66   27.85
                                   21.63   21.63   21.67    21.7    21.7
                        
    4090    4414    4700    4896    4944    4968    5000    5028    5058    5106
    5480    5946    6561
   25.73    25.8      26   23.96   23.99   24.07   24.15   24.08   23.74   23.58
   26.52   26.66   27.85
                                   21.63   21.63   21.67    21.7    21.7
                        
BR Coef=-1 , 0 , 0 ,, 0 ,,,.8,-1,,0,
WSPro=,,,, 1 ,,,, 0 ,,,, 0 ,,,,-1 ,-1 ,-1 , 0 , 0 , 0 , 0 , 0
BC Design=,, 0 ,, 0 ,,,,,,
BC HTab HWMax=28.53

Type RM Length L Ch R = 1 ,12565.83,85.73,81.79,86
XS GIS Cut Line= 6
 3174743.5683399 13821022.251754     3176516.501    13821093.909
     3176699.221      13821215.9     3176939.315    13821330.563
     3177179.118    13821441.241     3178082.989    13821888.565
#Sta/Elev= 30
 3046.45   26.59 3552.36   25.12 3642.86   25.24 3687.26   25.84 3838.12   25.81
 3924.38   25.26 4080.25   25.94 4242.53   25.42 4507.09   26.25  4578.5   26.71
 4818.94   25.91 4936.57   24.09 4965.17   22.36 4994.02    7.49 5003.45    7.35
 5034.83    23.3 5059.34   25.02 5090.76   25.47 5151.25   24.97 5226.17   25.17
 5332.02   27.12 5541.74   27.12 5713.31   27.73 6069.79   27.35 6221.42   27.72
 6263.54   26.99 6460.47   28.58 6506.62   28.54 6563.54   26.39 6579.28   27.05
#Mann= 5 ,-1 , 0
 3046.45     .15       0 4507.09     .07       0 4965.17    .015       0
 5034.83     .07       0 5090.76     .15       0
#XS Ineff= 2 , 0
       0    4966      23    5032       0      23
Permanent Ineff=
       F       F
Bank Sta=4965.17,5034.83
XS Rating Curve= 0
Exp/Cntr=.5,.3

Type RM Length L Ch R = 1 ,12484.03,646.45,731.76,940.78
XS GIS Cut Line= 6
 3175372.4117301  13821104.75768     3176473.397    13821161.326
     3176659.665    13821285.655     3176816.723    13821357.883
     3177133.002    13821519.638     3178023.039    13821985.409
#Sta/Elev= 30
 3734.61   26.45 3966.29   25.32 4129.43    26.1 4191.79   25.24 4246.94   25.19
 4559.33   26.27 4623.95   26.11 4674.54    26.7 4842.84   26.76 4884.17   26.01
 4929.33   26.23 4931.73   25.88 4936.57   24.09 4965.17   22.36 4994.02    7.49
 5003.45    7.35 5004.41    7.57 5034.83    23.3 5059.34   25.02 5090.76   25.47
 5207.65   24.92 5334.62   27.25  5407.3   26.64 5523.61   26.67 5708.45   27.53
 5971.84    27.8 6252.39   27.05 6508.01   28.68 6577.56   26.48 6593.16   27.11
#Mann= 5 ,-1 , 0
 3734.61     .15       0 4559.33     .07       0 4965.17    .015       0
 5034.83     .07       0 5090.76     .15       0
Bank Sta=4965.17,5034.83
XS Rating Curve= 0
Exp/Cntr=.3,.1

Type RM Length L Ch R = 1 ,11752.27,20.78,20,20.49
XS GIS Cut Line= 6
      3175084.18    13821181.024     3175854.312    13821408.144
     3175947.652    13821564.471     3176054.434    13821755.891
     3176946.401    13822069.943     3177444.389    13822248.341
#Sta/Elev= 30
 4047.19   26.64 4074.97   27.22 4397.99   26.75 4550.84   25.25 4625.01   25.31
 4735.78    24.6 4885.55   25.97    4906   26.44 4945.21   24.58 4965.49   19.94
 4967.45   19.48 4993.79     9.3 5004.83    9.39 5032.52   21.32 5034.52   21.76
 5045.95   24.38 5089.45   25.48  5182.5   24.86 5282.05   25.49 5338.22   24.39
 5372.04   24.91  5614.2   25.32 5660.45   24.62 5895.28   26.54 5963.25   26.68
 6051.59   25.93 6208.47   26.95 6413.87   27.67 6586.88   27.56 6657.12   26.55
#Mann= 4 ,-1 , 0
 4047.19     .15       0 4550.84     .07       0 4965.49    .015       0
 5034.52     .15       0
#Block Obstruct= 1 ,-1
 5968.18 6157.12   26.53
Bank Sta=4965.49,5034.52
XS Rating Curve= 0
Exp/Cntr=.5,.3

Type RM Length L Ch R = 1 ,11732.27,25.98,25,25.61
XS GIS Cut Line= 6
       3175077.1    13821216.404      3175853.34     13821445.53
     3175930.304    13821574.428     3176070.376    13821825.445
     3176906.778    13822142.937      3177331.48    13822309.373
#Sta/Elev= 30
 4004.39    26.5 4039.55   27.23 4379.58   26.73 4462.74   25.77 4518.03   25.07
 4564.25   25.11 4631.91   24.68 4813.73   25.21 4874.49   25.74 4911.93   26.61
 4944.61   24.92 4964.91    20.5  4975.3   16.28 4996.14    8.88 4999.78    8.57
 5031.92   21.34  5035.1   22.17 5045.35   24.71 5066.39    25.3 5256.06   24.02
 5379.16   25.86 5444.33   25.31 5618.14    25.7  5694.6   24.56 5910.15   26.42
 5961.61    26.3 6070.27   25.35 6137.78   25.78 6370.28   26.19  6602.1   27.47
#Mann= 4 ,-1 , 0
 4004.39     .15       0 4462.74     .07       0 4964.91    .015       0
  5035.1     .15       0
#XS Ineff= 2 , 0
       0    4947    24.3    5044       0    24.3
Permanent Ineff=
       F       F
Bank Sta=4964.91,5035.1
XS Rating Curve= 0
Exp/Cntr=.5,.3

Type RM Length L Ch R = 3 ,11719   ,,,
BEGIN DESCRIPTION:
FOOT BRIDGE
END DESCRIPTION:
Bridge Culvert--1,0,-1,-1, 0
Deck Dist Width WeirC Skew NumUp NumDn MinLoCord MaxHiCord MaxSubmerge Is_Ogee
8,9,2.6,0, 2, 2, , , .95, 0, 0,0,,
    4926    5070
    25.3    25.3
    24.3    24.3
    4926    5070
    25.3    25.3
    24.3    24.3
Pier Skew, UpSta & Num, DnSta & Num=  ,4982, 2 ,4983, 2 , 0 , 0 , 0 ,,
       1       1
       8      25
       1       1
       8      25
Pier Skew, UpSta & Num, DnSta & Num=  ,5014, 2 ,5016, 2 , 0 , 0 , 0 ,,
       1       1
       8      25
       1       1
       8      25
BR Coef=-1 , 1 , 0 ,, 0 ,,,.8,-1,2,0,
WSPro=,,,, 1 ,,,, 0 ,,,, 0 ,,,,-1 ,-1 ,-1 , 0 , 0 , 0 , 0 , 0
BC Design=,, 0 ,, 0 ,,,,,,
BC HTab HWMax=27.47

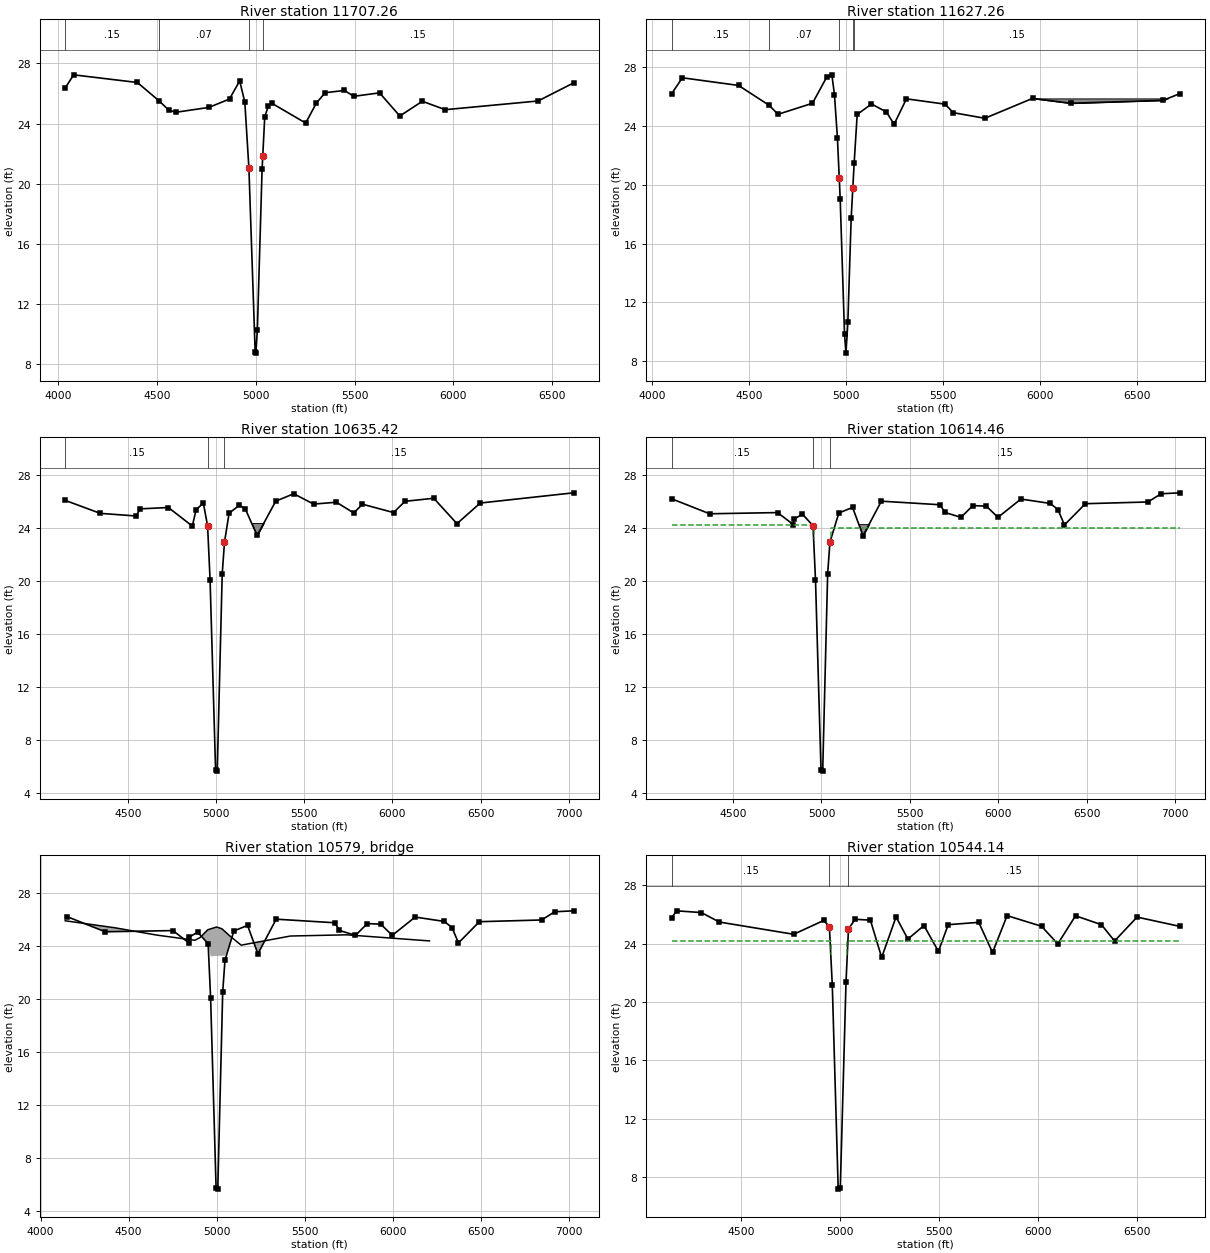
Type RM Length L Ch R = 1 ,11707.26,83.13,80,81.97
XS GIS Cut Line= 6
      3175070.03    13821255.321     3175847.146    13821483.921
     3175908.618    13821586.875     3176074.997    13821884.985
     3176874.078     13822204.78     3177288.758    13822355.147
#Sta/Elev= 30
 4035.02   26.36 4077.54   27.24 4400.31   26.73 4511.69   25.49 4560.25   24.88
 4596.13   24.75 4762.25   25.07  4866.7   25.63  4918.3   26.84 4944.29   25.41
 4964.93   21.02 4996.65    8.77 5000.18    8.72  5007.7   10.29  5031.6   20.94
 5035.07   21.85 5045.03   24.45 5063.62   25.17 5081.96   25.34 5252.31   24.03
 5306.37   25.36 5350.72   26.05 5448.76    26.2 5495.76   25.81 5626.26   26.04
 5728.67    24.5 5843.03   25.48 5958.74   24.92 6428.62    25.5 6608.17    26.7
#Mann= 4 ,-1 , 0
 4035.02     .15       0 4511.69     .07       0 4964.93    .015       0
 5035.07     .15       0
#XS Ineff= 2 , 0
       0    4949    24.3  5044.5       0    24.3
Permanent Ineff=
       F       F
Bank Sta=4964.93,5035.07
XS Rating Curve= 0
Exp/Cntr=.5,.3

Type RM Length L Ch R = 1 ,11627.26,1272.5,991.85,758.64
XS GIS Cut Line= 6
      3175059.41    13821287.163     3175795.029    13821552.686
     3175839.224    13821626.704     3176059.691    13822021.636
     3176826.996    13822269.659     3177300.964     13822419.23
#Sta/Elev= 30
 4100.07   26.17 4155.11   27.25 4445.25   26.73  4603.3   25.38 4649.09   24.77
 4826.85   25.52 4900.96   27.31 4927.02   27.45 4940.38    26.1 4955.65   23.17
    4965   20.47 4969.95   19.03 4992.32    9.83  4999.7    8.56 5009.44   10.64
 5026.57    17.7 5035.01   19.74 5042.13   21.47 5057.66   24.76 5131.57   25.47
  5208.6   24.93 5248.11   24.09 5311.94   25.82 5511.17   25.46  5554.1   24.88
 5716.72    24.5 5962.73   25.85 6160.88   25.52 6637.66   25.72 6724.05   26.18
#Mann= 5 ,-1 , 0
 4100.07     .15       0  4603.3     .07       0    4965    .015       0
 5035.01     .07       0 5042.13     .15       0
#Block Obstruct= 2 ,-1
 5965.89 6724.05   25.85    5236    5257    24.3
Bank Sta=4965,5035.01
XS Rating Curve= 0
Exp/Cntr=.3,.1

Type RM Length L Ch R = 1 ,10635.42,20.8,20.96,20.45
XS GIS Cut Line= 6
       3174255.3    13822250.655     3175227.614    13822280.728
     3175526.564    13822293.271     3176025.749    13822307.891
     3176815.562    13822338.602     3177090.405    13822504.674
#Sta/Elev= 30
 4144.61   26.11  4343.4   25.13 4548.11   24.93 4568.44   25.47  4729.7   25.57
  4865.5   24.17    4887    25.4    4928   25.91 4952.16   24.18 4966.25    20.1
 4997.44    5.74 5006.93    5.67    5035   20.54 5047.84   22.94    5074   25.14
  5132.1   25.74  5165.4   25.48 5233.11   23.46 5338.69   26.05  5440.7   26.61
 5553.64   25.83 5682.65   25.97 5781.05   25.16 5830.52   25.82 6006.96   25.19
 6071.85   26.04 6234.95   26.27 6366.41   24.35  6498.5   25.91 7027.57   26.68
#Mann= 3 ,-1 , 0
 4144.61     .15       0 4952.16    .015       0 5047.84     .15       0
#Block Obstruct= 1 ,-1
    5205    5270    24.4
Bank Sta=4952.16,5047.84
XS Rating Curve= 0
Exp/Cntr=.5,.3

Type RM Length L Ch R = 1 ,10614.46,72.78,70.32,114.04
XS GIS Cut Line= 6
      3174254.66    13822270.645     3175150.863    13822300.268
     3175227.135    13822300.725     3175525.852    13822313.259
     3176745.583    13822354.981     3177072.095    13822556.551
#Sta/Elev= 30
  4152.5   26.21  4367.3   25.08 4751.86   25.17 4841.21   24.26 4842.52   24.66
  4892.4   25.05 4952.16   24.18 4966.25    20.1 4997.44    5.74 5006.93    5.67
    5035   20.54 5047.84   22.94 5098.41   25.14 5176.14   25.56 5235.04   23.42
 5339.01   26.03 5671.72   25.76 5698.19   25.18 5789.57   24.81 5856.64    25.7
  5933.5   25.65 5998.48   24.81 6128.65   26.19 6294.28   25.86 6337.64    25.4
 6374.91   24.24 6493.38   25.84 6847.12   25.97 6921.86   26.59  7028.6   26.66
#Mann= 3 ,-1 , 0
  4152.5     .15       0 4952.16    .015       0 5047.84     .15       0
#XS Ineff= 2 , 0
       0  4955.5    24.2    5056       0      24
Permanent Ineff=
       F       F
#Block Obstruct= 1 ,-1
    5200    5270    24.3
Bank Sta=4952.16,5047.84
XS Rating Curve= 0
Exp/Cntr=.5,.3

Type RM Length L Ch R = 3 ,10579   ,,,
BEGIN DESCRIPTION:
THOMAS AVE
END DESCRIPTION:
Bridge Culvert--1,0,-1,-1, 0
Deck Dist Width WeirC Skew NumUp NumDn MinLoCord MaxHiCord MaxSubmerge Is_Ogee
3,50,2.6,0, 13, 13, , , .95, 0, 0,0,,
    4140    4423    4660    4877    4907    4950    5000    5030    5078    5140
    5420    5740    6210
   25.91   25.38   24.83   24.44   24.65   25.23   25.44   25.31   24.74   24.07
   24.76   24.85   24.39
                                           23.22   23.25   23.28   23.29
                        
    4140    4423    4660    4877    4907    4950    5000    5030    5078    5140
    5420    5740    6210
   25.91   25.38   24.83   24.44   24.65   25.23   25.44   25.31   24.74   24.07
   24.76   24.85   24.39
                                           23.22   23.25   23.28   23.29
                        
BR Coef=-1 , 0 , 0 ,, 0 ,,,.8,-1,,0,
WSPro=,,,, 1 ,,,, 0 ,,,, 0 ,,,,-1 ,-1 ,-1 , 0 , 0 , 0 , 0 , 0
BC Design=,, 0 ,, 0 ,,,,,,
BC HTab HWMax=26.66

Type RM Length L Ch R = 1 ,10544.14,83.18,80.04,76.89
XS GIS Cut Line= 6
      3174252.46     13822340.61      3175149.36     13822370.26
     3175288.363    13822411.828     3175590.028    13822442.506
      3176039.97     13822483.41 3176804.267069713822564.2552863
#Sta/Elev= 30
 4150.71   25.78 4175.51   26.26 4300.64   26.14 4391.53   25.49 4766.51   24.65
 4918.28    25.6 4946.84   25.18 4961.54   21.14 4991.35    7.16 5001.94    7.23
 5030.76   21.36 5043.16   25.01 5076.63   25.68 5153.86   25.62 5210.74   23.06
 5283.42   25.84 5343.14   24.32 5424.32   25.25 5497.15   23.48 5546.78   25.31
 5700.84   25.47 5770.49    23.4    5844   25.93 6017.86    25.2 6099.85   23.99
 6189.41   25.92 6320.14   25.31 6386.41   24.19  6499.9   25.83 6716.77   25.19
#Mann= 3 ,-1 , 0
 4150.71     .15       0 4946.84    .015       0 5043.16     .15       0
#XS Ineff= 2 , 0
       0    4954    24.2    5037       0    24.2
Permanent Ineff=
       F       F
Bank Sta=4946.84,5043.16
XS Rating Curve= 0
Exp/Cntr=.5,.3

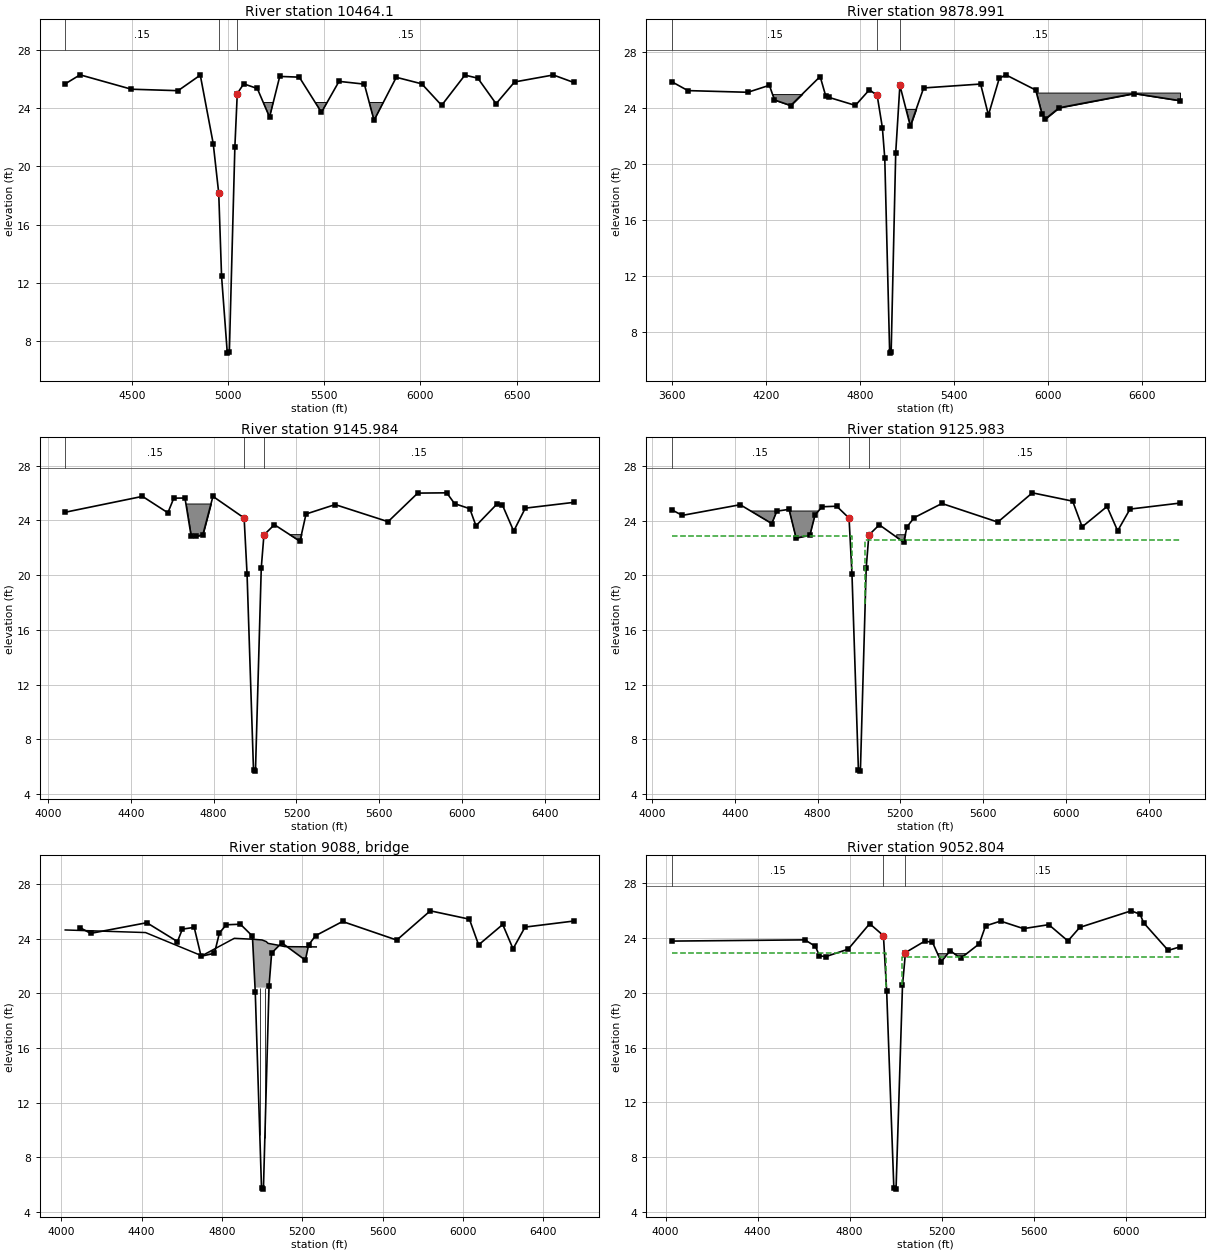
Type RM Length L Ch R = 1 ,10464.1 ,465.82,585.11,642.81
XS GIS Cut Line= 6
      3174249.93     13822420.57     3175147.642    13822450.251
     3175242.346     13822483.41     3176055.308    13822570.331
      3176303.99    13822599.587      3176875.24    13822672.019
#Sta/Elev= 30
 4153.73   25.68 4230.96    26.3 4497.86   25.31 4740.46   25.21 4855.92   26.28
 4923.28   21.56 4951.84   18.15 4966.54   12.44 4996.35    7.16 5006.94    7.23
 5035.76   21.36 5048.16   25.01 5081.63   25.68 5152.27   25.36 5216.09   23.39
 5268.94   26.19  5370.6   26.14 5485.83   23.72  5577.1   25.85 5708.76   25.66
 5759.18   23.17 5874.78   26.13 6007.24   25.68 6110.51    24.2 6231.53   26.28
 6298.63   26.07 6393.57   24.31 6489.81   25.81    6691   26.29 6796.18   25.78
#Mann= 3 ,-1 , 0
 4153.73     .15       0 4951.84    .015       0 5048.16     .15       0
#Block Obstruct= 1 ,-1
    5170    5825    24.4
Bank Sta=4951.84,5048.16
XS Rating Curve= 0
Exp/Cntr=.3,.1

Type RM Length L Ch R = 1 ,9878.991,758.76,733.01,622.16
XS GIS Cut Line= 6
      3173635.48    13822478.195     3174031.107    13822579.005
     3174790.784    13822934.534     3175047.997    13823064.768
     3175751.008    13823427.705     3176650.977    13823597.141
#Sta/Elev= 30
 3600.18   25.91 3703.66   25.27 4086.01   25.15 4223.44   25.65 4255.96    24.6
 4359.25    24.2 4547.22   26.28 4582.38    24.9 4601.72   24.79 4772.05   24.21
 4861.39   25.33    4911   24.92 4944.08   22.62 4959.35   20.43 4990.66    6.47
 5000.04    6.52 5029.22   20.82 5055.81   25.65 5122.27   22.73 5207.34   25.46
 5570.63   25.74 5620.49   23.52  5689.4   26.14 5731.35    26.4 5922.17   25.31
 5961.38   23.63 5983.39   23.24 6071.71   24.04 6550.58   25.06 6842.45   24.55
#Mann= 3 ,-1 , 0
 3600.18     .15       0    4911    .015       0 5055.81     .15       0
#Block Obstruct= 3 ,-1
 4048.32    4523   25.02 5758.35 6842.45   25.13    5090    5160   23.95
Bank Sta=4911,5055.81
XS Rating Curve= 0
Exp/Cntr=.3,.1

Type RM Length L Ch R = 1 ,9145.984,20.05,20,20.1
XS GIS Cut Line= 6
  3173602.529069 13823531.978873     3174466.506     13823566.72
     3174562.089     13823575.08     3174697.059     13823580.96
     3175636.075    13823609.393     3176057.131    13823625.775
#Sta/Elev= 30
 4082.49    24.6 4455.92   25.76 4578.67   24.56 4607.19   25.63  4661.3   25.64
 4691.32   22.84 4715.37   22.84 4747.54   22.95 4796.42   25.76 4947.16   24.18
 4961.25    20.1 4992.44    5.74 5001.93    5.67    5030   20.54 5042.84   22.94
 5093.41   23.69 5217.02   22.48 5246.26   24.47 5386.84   25.16 5642.75   23.91
  5786.2      26 5926.38   26.02 5964.11   25.23 6037.63   24.86  6067.5   23.61
 6170.82   25.23 6195.55   25.12 6249.86   23.22 6305.99    24.9 6539.05   25.32
#Mann= 3 ,-1 , 0
 4082.49     .15       0 4947.16    .015       0 5042.84     .15       0
#Block Obstruct= 2 ,-1
  4633.4 4822.48   25.24    5150    5230      23
Bank Sta=4947.16,5042.84
XS Rating Curve= 0
Exp/Cntr=.5,.3

Type RM Length L Ch R = 1 ,9125.983,73.18,73.18,73.4
XS GIS Cut Line= 6
 3173610.0514958  13823552.31385     3174388.367    13823585.168
     3174465.435    13823586.703     3174560.782    13823595.042
     3175011.642    13823612.625     3176064.207    13823639.927
#Sta/Elev= 30
 4095.24   24.79 4146.65   24.38 4426.31   25.16 4578.94   23.78 4603.33   24.69
 4662.25   24.82 4696.55   22.71 4762.99   22.92 4787.81   24.41 4822.01   25.01
  4892.4   25.05 4952.16   24.18 4966.25    20.1 4997.44    5.74 5006.93    5.67
    5035   20.54 5047.84   22.94 5098.41   23.69 5215.75   22.42 5232.17   23.54
  5266.5   24.21 5400.78   25.25 5670.89   23.89 5837.77   26.03  6032.5   25.42
 6078.34   23.54 6198.43   25.03 6249.81   23.25 6309.52   24.84    6551   25.28
#Mann= 3 ,-1 , 0
 4095.24     .15       0 4952.16    .015       0 5047.84     .15       0
#XS Ineff= 2 , 0
       0    4965    22.9    5030       0    22.6
Permanent Ineff=
       F       F
#Block Obstruct= 2 ,-1
 4425.42 4828.78    24.7    5180    5250      23
Bank Sta=4952.16,5047.84
XS Rating Curve= 0
Exp/Cntr=.5,.3

Type RM Length L Ch R = 3 ,9088    ,,,
BEGIN DESCRIPTION:
JACKSON AVE
END DESCRIPTION:
Bridge Culvert--1,0,-1,-1, 0
Deck Dist Width WeirC Skew NumUp NumDn MinLoCord MaxHiCord MaxSubmerge Is_Ogee
2,54,2.6,0, 11, 12, , , .95, 0, 0,0,,
    4020    4420    4700    4862    4956    5000    5021    5030    5075    5114
    5270
   24.63   24.44   22.74   24.02   23.95    23.9   23.78   23.65   23.53   23.41
   23.39
                                   20.41   20.41   20.41   20.41
        
    4020    4420    4700    4862    4956    5000    5021    5030    5075    5114
    5270    5325
   24.63   24.44   22.74   24.02   23.95    23.9   23.78   23.65   23.53   23.41
   23.39    23.4
                                   20.41   20.41   20.41   20.41
                
Pier Skew, UpSta & Num, DnSta & Num=  ,4989, 4 ,4984, 4 , 3 , 3 , 0 ,,
     1.2     1.2       2       2
       5    18.4   18.41      21
     1.2     1.2       2       2
       5    18.4   18.41      21
Pier Skew, UpSta & Num, DnSta & Num=  ,5014, 4 ,5009, 4 , 3 , 3 , 0 ,,
     1.2     1.2       2       2
       5    18.4   18.41      21
     1.2     1.2       2       2
       5    18.4   18.41      21
BR Coef=-1 , 1 , 0 ,, 0 ,,,.8,-1,2,0,
WSPro=,,,, 1 ,,,, 0 ,,,, 0 ,,,,-1 ,-1 ,-1 , 0 , 0 , 0 , 0 , 0
BC Design=,, 0 ,, 0 ,,,,,,
BC HTab HWMax=26.08

Type RM Length L Ch R = 1 ,9052.804,80.2,80.14,80.4
XS GIS Cut Line= 6
     3173541.334    13823622.478     3174386.101    13823658.138
     3174461.524    13823659.639     3174556.011    13823667.903
     3174693.314    13823673.885     3175748.921     13823713.78
#Sta/Elev= 30
 4026.67   23.78 4605.86   23.87 4651.72   23.39 4669.02    22.7 4696.76   22.65
 4793.82   23.19  4887.4   25.05 4947.16   24.18 4961.25    20.1 4992.44    5.74
 5001.93    5.67    5030   20.54 5042.84   22.94  5127.1   23.78  5160.4   23.69
 5198.06   22.27 5237.69   23.08 5282.59   22.52 5363.62   23.58 5391.05   24.89
 5456.34   25.24 5556.15   24.69 5665.98   24.98 5749.03   23.79 5800.56   24.78
 6024.11   25.99 6062.88   25.74 6078.06   25.12 6184.97    23.1 6236.27   23.36
#Mann= 3 ,-1 , 0
 4026.67     .15       0 4947.16    .015       0 5042.84     .15       0
#XS Ineff= 2 , 0
       0    4960    22.9    5030       0    22.6
Permanent Ineff=
       F       F
#Block Obstruct= 1 ,-1
 5150.21 5394.43   22.86
Bank Sta=4947.16,5042.84
XS Rating Curve= 0
Exp/Cntr=.5,.3