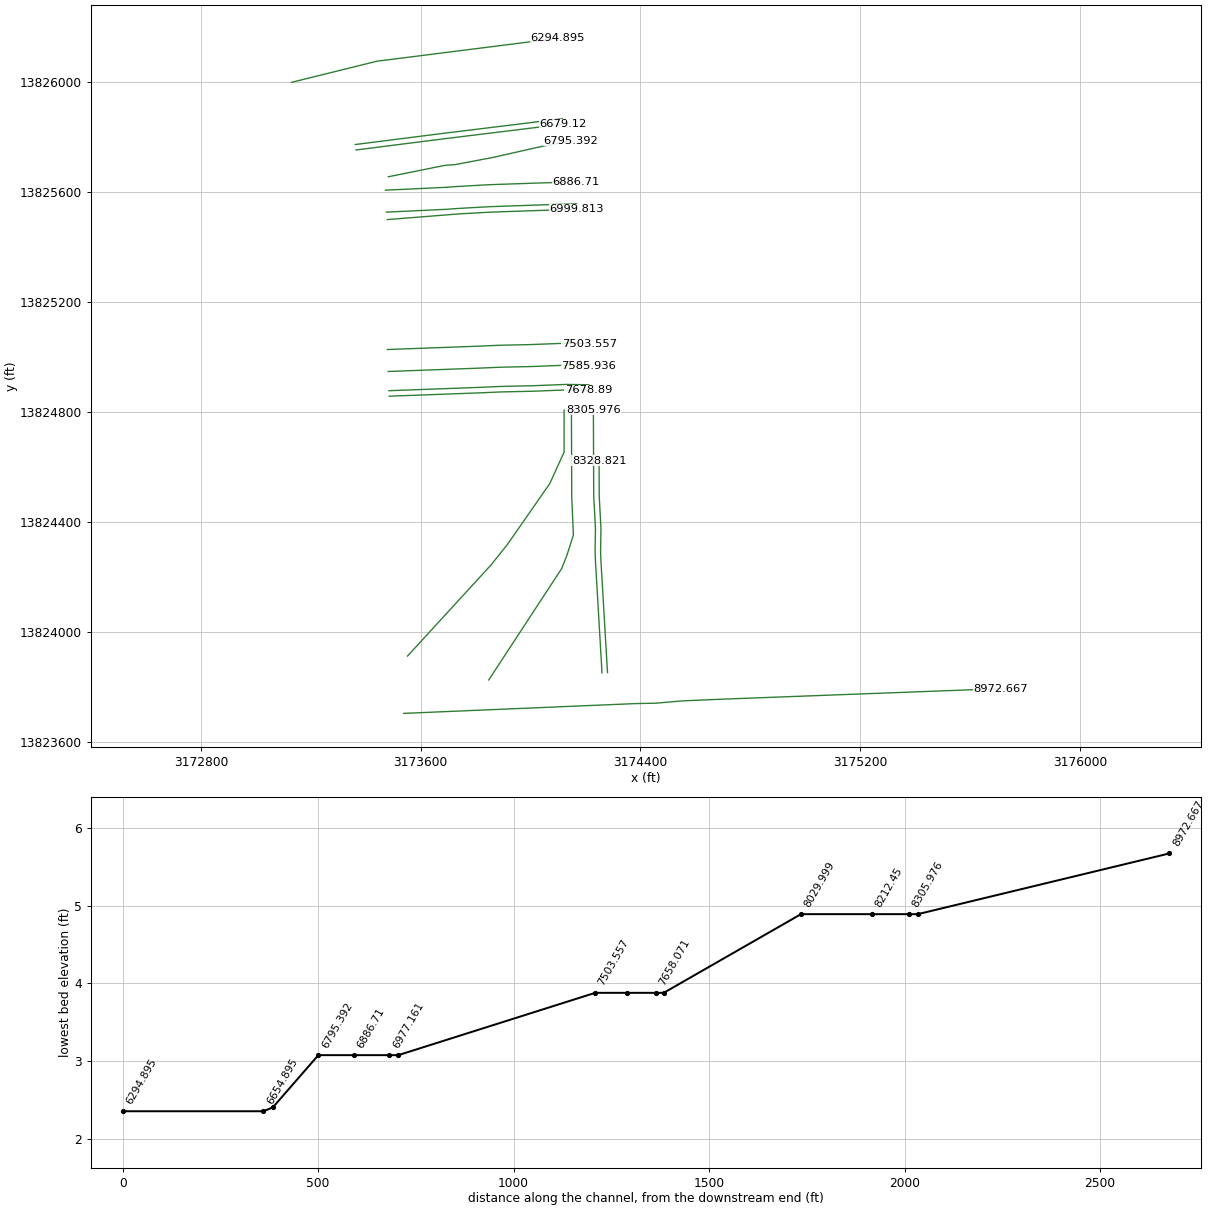
HEC-RAS study I101-00-00.prj: I101-00-00

--- I101-00-00.g03 (geometry) --- (continued)

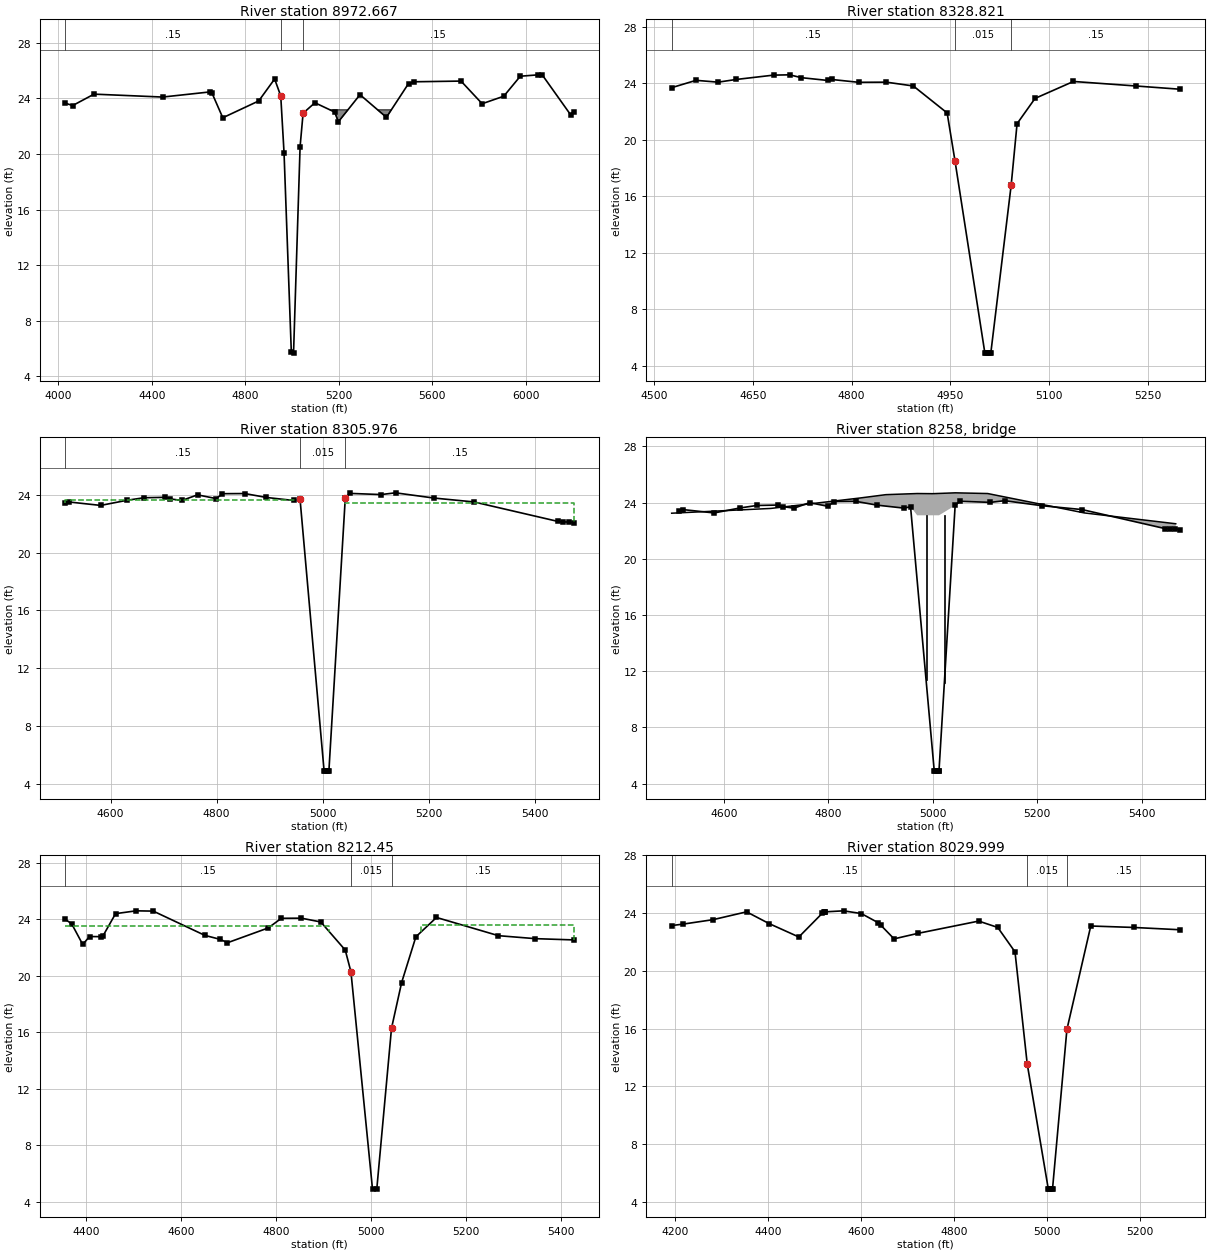
Type RM Length L Ch R = 1 ,8972.667,317.63,643.85,1030.15
XS GIS Cut Line= 6
      3173537.96    13823702.407     3174383.618    13823738.104
     3174457.238     13823739.57     3174550.782    13823747.751
     3174690.092     13823753.82     3175711.696    13823792.367
#Sta/Elev= 30
 4029.63   23.66 4061.66   23.49    4153   24.31 4446.72    24.1 4649.34   24.47
 4658.06   24.38 4704.12   22.61 4857.85   23.82    4926    25.4 4952.16   24.18
 4966.25    20.1 4997.44    5.74 5006.93    5.67    5035   20.54 5047.84   22.94
 5098.41   23.69 5183.02   23.02 5198.77   22.32 5291.38   24.27  5404.5   22.64
 5499.04   25.07 5524.49    25.2 5723.79   25.25 5814.28   23.62 5906.68   24.16
 5977.53    25.6 6055.12    25.7 6072.49   25.67 6192.65   22.83 6205.35   23.06
#Mann= 3 ,-1 , 0
 4029.63     .15       0 4952.16    .015       0 5047.84     .15       0
#Block Obstruct= 1 ,-1
 5123.95 5533.61   23.18
Bank Sta=4952.16,5047.84
XS Rating Curve= 0
Exp/Cntr=.3,.1

Type RM Length L Ch R = 1 ,8328.821,22.44,22.84,22.52
XS GIS Cut Line= 6
     3174280.306    13823850.979      3174256.31    13824259.168
     3174255.163     13824292.06     3174256.453    13824377.621
     3174250.097    13824493.522 3174249.618402813824623.0445733
#Sta/Elev= 25
 4526.44   23.69 4563.51   24.21 4597.12   24.08 4624.34   24.27 4681.58   24.58
 4705.89    24.6  4723.5    24.4  4764.1    24.2 4769.78   24.27 4810.83   24.07
 4852.96   24.08 4893.91   23.81 4945.33    21.9 4957.31   18.49  5002.7    4.89
 5004.57    4.92 5007.29    4.91  5010.9    4.92 5011.78    4.92 5042.69   16.79
 5051.66   21.14    5079   22.93 5137.37   24.13 5232.33   23.81 5299.41   23.58
#Mann= 3 ,-1 , 0
 4526.44     .15       0 4957.31    .015       0 5042.69     .15       0
Bank Sta=4957.31,5042.69
XS Rating Curve= 0
Exp/Cntr=.5,.3

Type RM Length L Ch R = 1 ,8305.976,222.52,93.53,90.08
XS GIS Cut Line= 6
     3174260.341    13823849.805      3174236.33    13824258.233
     3174235.158    13824291.862     3174236.445    13824377.224
     3174230.099    13824492.937     3174228.936    13824807.649
#Sta/Elev= 30
  4514.4   23.41  4520.8    23.5 4581.31   23.26 4630.33   23.61 4662.87   23.79
 4703.25   23.82 4712.64   23.71 4734.28    23.6 4764.01   23.99 4799.38   23.73
 4810.83   24.07 4852.96   24.08 4893.91   23.81 4945.33    23.6 4957.31    23.7
  5002.7    4.89 5004.57    4.92 5007.29    4.91  5010.9    4.92 5011.78    4.92
 5042.69   23.79 5051.66   24.09 5110.14   24.01 5137.37   24.13 5209.72   23.77
 5285.38    23.5 5444.06   22.15 5454.01   22.12 5464.39   22.11 5473.16   22.07
#Mann= 3 ,-1 , 0
  4514.4     .15       0 4957.31    .015       0 5042.69     .15       0
#XS Ineff= 2 , 0
       0  4958.2    23.6    5042       0    23.4
Permanent Ineff=
       F       F
Bank Sta=4957.31,5042.69
XS Rating Curve= 0
Exp/Cntr=.5,.3

Type RM Length L Ch R = 3 ,8258    ,,,
BEGIN DESCRIPTION:
TATAR ST
END DESCRIPTION:
Bridge Culvert--1,0,-1,-1, 0
Deck Dist Width WeirC Skew NumUp NumDn MinLoCord MaxHiCord MaxSubmerge Is_Ogee
7,75,2.6,0, 10, 10, , , .95, 0, 0,0,,
    4500    4690    4860    4910    4970    5000    5043    5105    5290    5465
   23.24   23.58   24.32   24.56   24.64   24.63   24.69   24.64   23.26   22.49
                           23.09   23.09   23.09   23.09
    4500    4690    4860    4910    4970    5000    5043    5105    5290    5465
   23.24   23.58   24.32   24.56   24.64   24.63   24.69   24.64   23.26   22.49
                           23.09   23.09   23.09   23.09   23.09
Pier Skew, UpSta & Num, DnSta & Num=  ,4987, 4 ,4987, 4 , 3 , 3 , 0 ,,
     1.2     1.2       2       2
       4   21.08   21.09      24
     1.2     1.2       2       2
       4   21.08   21.09      24
Pier Skew, UpSta & Num, DnSta & Num=  ,5022, 4 ,5025, 4 , 3 , 3 , 0 ,,
     1.2     1.2       2       2
       4   21.08   21.09      24
     1.2     1.2       2       2
       4   21.08   21.09      24
BR Coef=-1 , 1 , 0 ,, 0 ,,,.8,-1,2,0,
WSPro=,,,, 1 ,,,, 0 ,,,, 0 ,,,,-1 ,-1 ,-1 , 0 , 0 , 0 , 0 , 0
BC Design=,, 0 ,, 0 ,,,,,,
BC HTab HWMax=24.13

Type RM Length L Ch R = 1 ,8212.45 ,216.27,182.45,30.36
XS GIS Cut Line= 6
     3173847.951    13823824.001     3174113.828    13824230.261
     3174132.971    13824279.182     3174156.049    13824351.538
     3174150.107    13824490.598     3174148.936    13824807.353
#Sta/Elev= 27
 4355.86      24 4369.49   23.68 4392.69   22.22 4407.21   22.78 4430.27   22.77
 4435.81   22.85 4461.87    24.4 4505.17    24.6  4541.2   24.58 4649.93   22.86
 4682.06   22.58 4697.46   22.34 4783.32   23.39 4810.83   24.07 4852.96   24.08
 4893.91   23.81 4945.33   21.82 4957.31   20.28  5002.7    4.89 5011.78    4.92
 5042.69   16.28    5064   19.52    5094   22.76 5137.37   24.13 5267.83   22.84
 5344.97   22.63 5425.86   22.54
#Mann= 3 ,-1 , 0
 4355.86     .15       0 4957.31    .015       0 5042.69     .15       0
#XS Ineff= 2 , 0
       0    4912    23.5  5104.5       0    23.6
Permanent Ineff=
       F       F
Bank Sta=4957.31,5042.69
XS Rating Curve= 0
Exp/Cntr=.5,.3

Type RM Length L Ch R = 1 ,8029.999,610.37,351.11,194.27
XS GIS Cut Line= 6
     3173552.295    13823911.209     3173856.459    13824243.023
     3173916.015    13824317.469     3174069.929    13824538.673
     3174122.336    13824653.537     3174122.336    13824806.683
#Sta/Elev= 29
 4192.36   23.13 4216.79   23.23 4281.67   23.54 4353.53   24.08 4401.78   23.27
 4465.96   22.34 4516.04   23.97 4519.96   24.08 4521.49   24.08 4523.16   24.08
 4562.14   24.15 4600.45   23.96 4636.55   23.33 4642.49   23.15 4670.82   22.21
    4722   22.59 4852.96   23.44 4893.91      23    4931   21.31 4957.31   13.55
  5002.7    4.89 5004.57    4.92 5007.29    4.91  5010.9    4.92 5011.78    4.92
 5042.69   15.94    5094    23.1    5186      23    5286   22.84
#Mann= 3 ,-1 , 0
 4192.36     .15       0 4957.31    .015       0 5042.69     .15       0
Bank Sta=4957.31,5042.69
XS Rating Curve= 0
Exp/Cntr=.3,.1

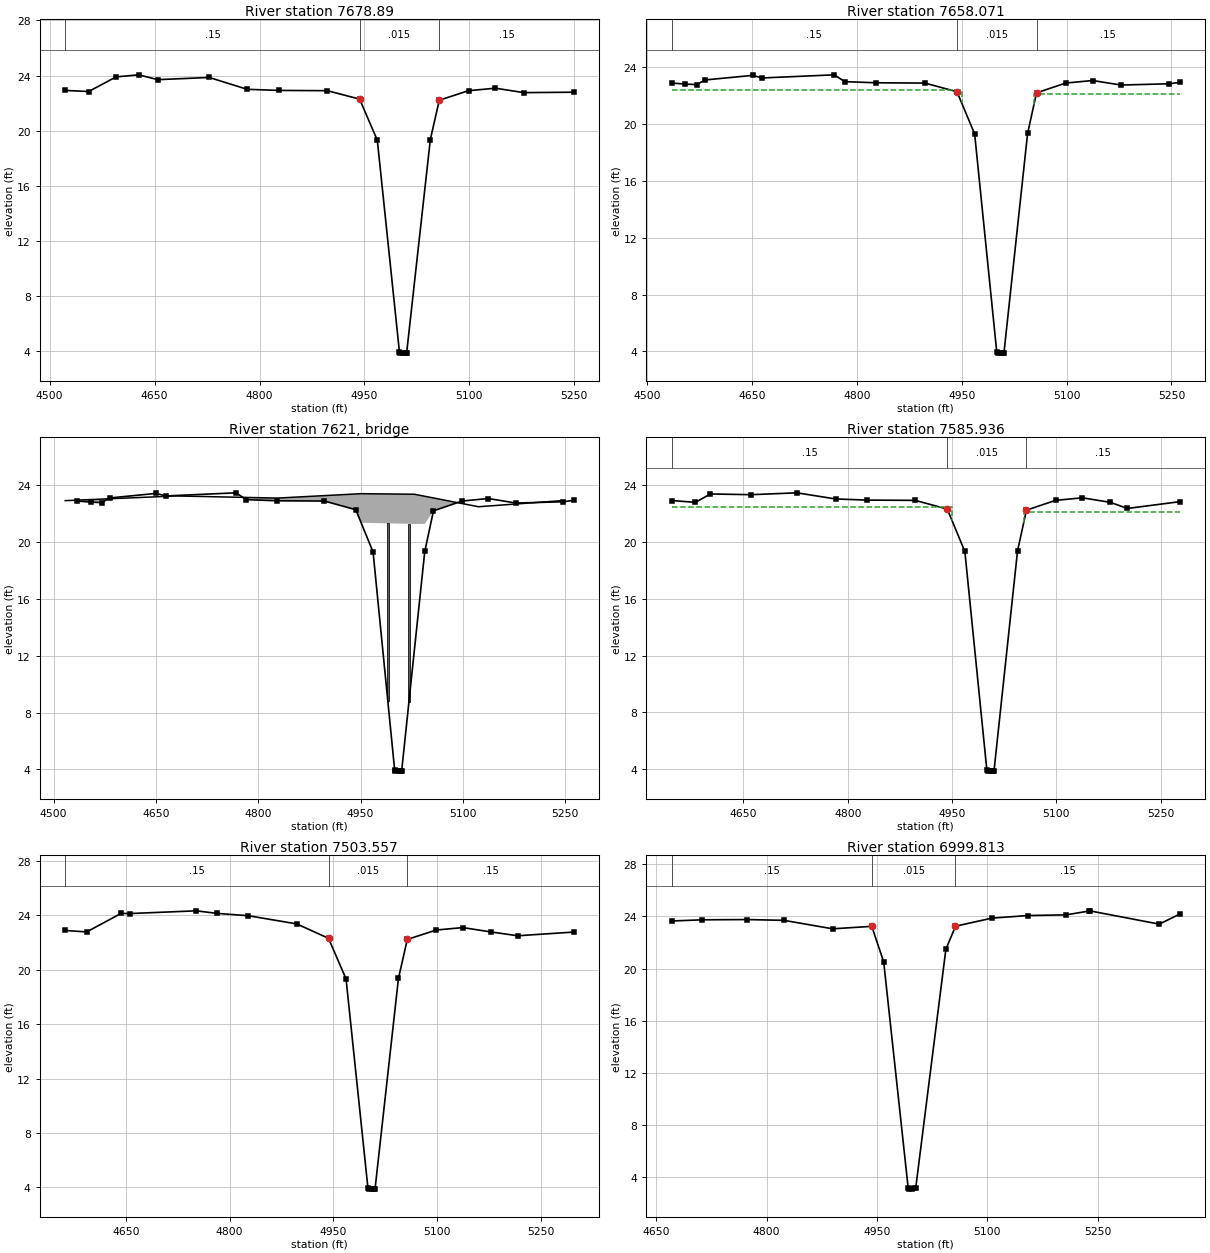
Type RM Length L Ch R = 1 ,7678.89 ,20.17,20.82,20.1
XS GIS Cut Line= 6
     3173485.269    13824857.216     3173818.127    13824869.468
     3173893.182    13824872.744     3174006.974    13824875.221
     3174127.424    13824879.949     3174211.421     13824878.89
#Sta/Elev= 22
 4522.28   22.92 4555.77   22.84 4594.97    23.9 4627.09   24.05  4654.7    23.7
 4728.09   23.86 4782.41      23 4827.19   22.92 4897.06    22.9 4943.07   22.29
 4968.39   19.31 5000.03    3.95 5001.14    3.92 5005.74    3.91 5008.74    3.88
 5010.32     3.9 5044.15   19.35 5056.93   22.21 5098.76    22.9  5137.3   23.08
 5177.82   22.76 5248.86   22.79
#Mann= 3 ,-1 , 0
 4522.28     .15       0 4943.07    .015       0 5056.93     .15       0
Bank Sta=4943.07,5056.93
XS Rating Curve= 0
Exp/Cntr=.5,.3

Type RM Length L Ch R = 1 ,7658.071,70.6,72.14,70.36
XS GIS Cut Line= 6
     3173484.534    13824877.202     3173817.323    13824889.452
     3173892.528    13824892.735     3174006.364    13824895.212
     3174127.158    13824899.954     3174211.673    13824898.888
#Sta/Elev= 24
 4534.73    22.9 4554.42   22.83 4570.39   22.79  4582.7   23.12 4650.48   23.44
 4664.56   23.26 4767.51   23.48 4782.41      23 4827.19   22.92 4897.06    22.9
 4943.07   22.29 4968.39   19.31 5000.03    3.95 5001.14    3.92 5005.74    3.91
 5008.74    3.88 5010.32     3.9 5044.15   19.35 5056.93   22.21 5098.76    22.9
  5137.3   23.08 5177.82   22.76 5246.73   22.85 5262.29   22.95
#Mann= 3 ,-1 , 0
 4534.73     .15       0 4943.07    .015       0 5056.93     .15       0
#XS Ineff= 2 , 0
       0    4950    22.4    5053       0    22.1
Permanent Ineff=
       F       F
Bank Sta=4943.07,5056.93
XS Rating Curve= 0
Exp/Cntr=.5,.3

Type RM Length L Ch R = 3 ,7621    ,,,
BEGIN DESCRIPTION:
BROADWAY ST
END DESCRIPTION:
Bridge Culvert--1,0,-1,-1, 0
Deck Dist Width WeirC Skew NumUp NumDn MinLoCord MaxHiCord MaxSubmerge Is_Ogee
9,45,2.6,0, 7, 7, , , .95, 0, 0,0,,
    4517    4680    4828    4951    5029    5123    5245
   22.93   23.26   23.11   23.42   23.38    22.5   22.93
                           21.37   21.29   21.29
    4517    4680    4828    4951    5029    5123    5295
   22.93   23.26   23.11   23.42   23.38    22.5   22.93
                           21.37   21.29   21.29
Pier Skew, UpSta & Num, DnSta & Num=  ,4990, 4 ,4990, 4 , 3 , 3 , 0 ,,
     1.2     1.2       2       2
       3   19.29    19.3    22.5
     1.2     1.2       2       2
       3   19.29    19.3    22.5
Pier Skew, UpSta & Num, DnSta & Num=  ,5021, 4 ,5021, 4 , 3 , 3 , 0 ,,
     1.2     1.2       2       2
       3   19.29    19.3    22.5
     1.2     1.2       2       2
       3   19.29    19.3    22.5
BR Coef=-1 , 1 , 0 ,, 0 ,,,.8,-1,2,0,
WSPro=,,,, 1 ,,,, 0 ,,,, 0 ,,,,-1 ,-1 ,-1 , 0 , 0 , 0 , 0 , 0
BC Design=,, 0 ,, 0 ,,,,,,
BC HTab HWMax=23.48

Type RM Length L Ch R = 1 ,7585.936,80.69,82.38,80.42
XS GIS Cut Line= 6
     3173481.959    13824947.155     3173814.509    13824959.396
      3173890.24    13824962.702      3174004.23    13824965.182
     3174126.226    13824969.971     3174212.556    13824968.883
#Sta/Elev= 22
 4546.77   22.89 4580.99   22.76 4602.45   23.35 4661.12    23.3 4726.84   23.43
 4782.41      23 4827.19   22.92 4897.06    22.9 4943.07   22.29 4968.39   19.31
 5000.03    3.95 5001.14    3.92 5005.74    3.91 5008.74    3.88 5010.32     3.9
 5044.15   19.35 5056.93   22.21 5098.76    22.9  5137.3   23.08 5177.82   22.76
 5202.05   22.33 5277.79   22.81
#Mann= 3 ,-1 , 0
 4546.77     .15       0 4943.07    .015       0 5056.93     .15       0
#XS Ineff= 2 , 0
       0    4950    22.4    5053       0    22.1
Permanent Ineff=
       F       F
Bank Sta=4943.07,5056.93
XS Rating Curve= 0
Exp/Cntr=.5,.3

Type RM Length L Ch R = 1 ,7503.557,489.06,503.74,498.91
XS GIS Cut Line= 6
     3173479.016    13825027.101     3173811.293    13825039.332
     3173887.625    13825042.664      3174001.79    13825045.148
      3174125.16    13825049.991     3174213.564    13825048.876
#Sta/Elev= 22
 4562.32   22.87 4593.34   22.76 4643.01   24.12 4655.84   24.11 4751.73   24.31
 4782.41   24.12 4827.19   23.95 4897.06   23.35 4943.07   22.29 4968.39   19.31
 5000.03    3.95 5001.14    3.92 5005.74    3.91 5008.74    3.88 5010.32     3.9
 5044.15   19.35 5056.93   22.21 5098.76    22.9  5137.3   23.08 5177.82   22.76
 5216.44   22.48 5297.29   22.75
#Mann= 3 ,-1 , 0
 4562.32     .15       0 4943.07    .015       0 5056.93     .15       0
Bank Sta=4943.07,5056.93
XS Rating Curve= 0
Exp/Cntr=.3,.1

Type RM Length L Ch R = 1 ,6999.813,23.83,22.65,22.3
XS GIS Cut Line= 5
     3173478.723    13825500.194     3173737.744    13825520.769
     3173850.989    13825527.169     3174017.653    13825532.941
     3174168.645    13825537.587
#Sta/Elev= 21
 4671.04   23.65 4711.84   23.74 4773.22   23.76  4823.7    23.7 4889.83   23.05
 4943.09   23.24 4959.29   20.51  4992.5     3.2 4993.68    3.08  4997.2    3.12
 5000.49    3.14 5002.77    3.14 5043.82   21.48 5056.91   23.25 5106.45   23.87
  5155.7   24.07 5207.26   24.12 5238.18   24.41 5239.25   24.43 5333.94   23.41
 5362.13   24.19
#Mann= 3 ,-1 , 0
 4671.04     .15       0 4943.09    .015       0 5056.91     .15       0
Bank Sta=4943.09,5056.91
XS Rating Curve= 0
Exp/Cntr=.5,.3

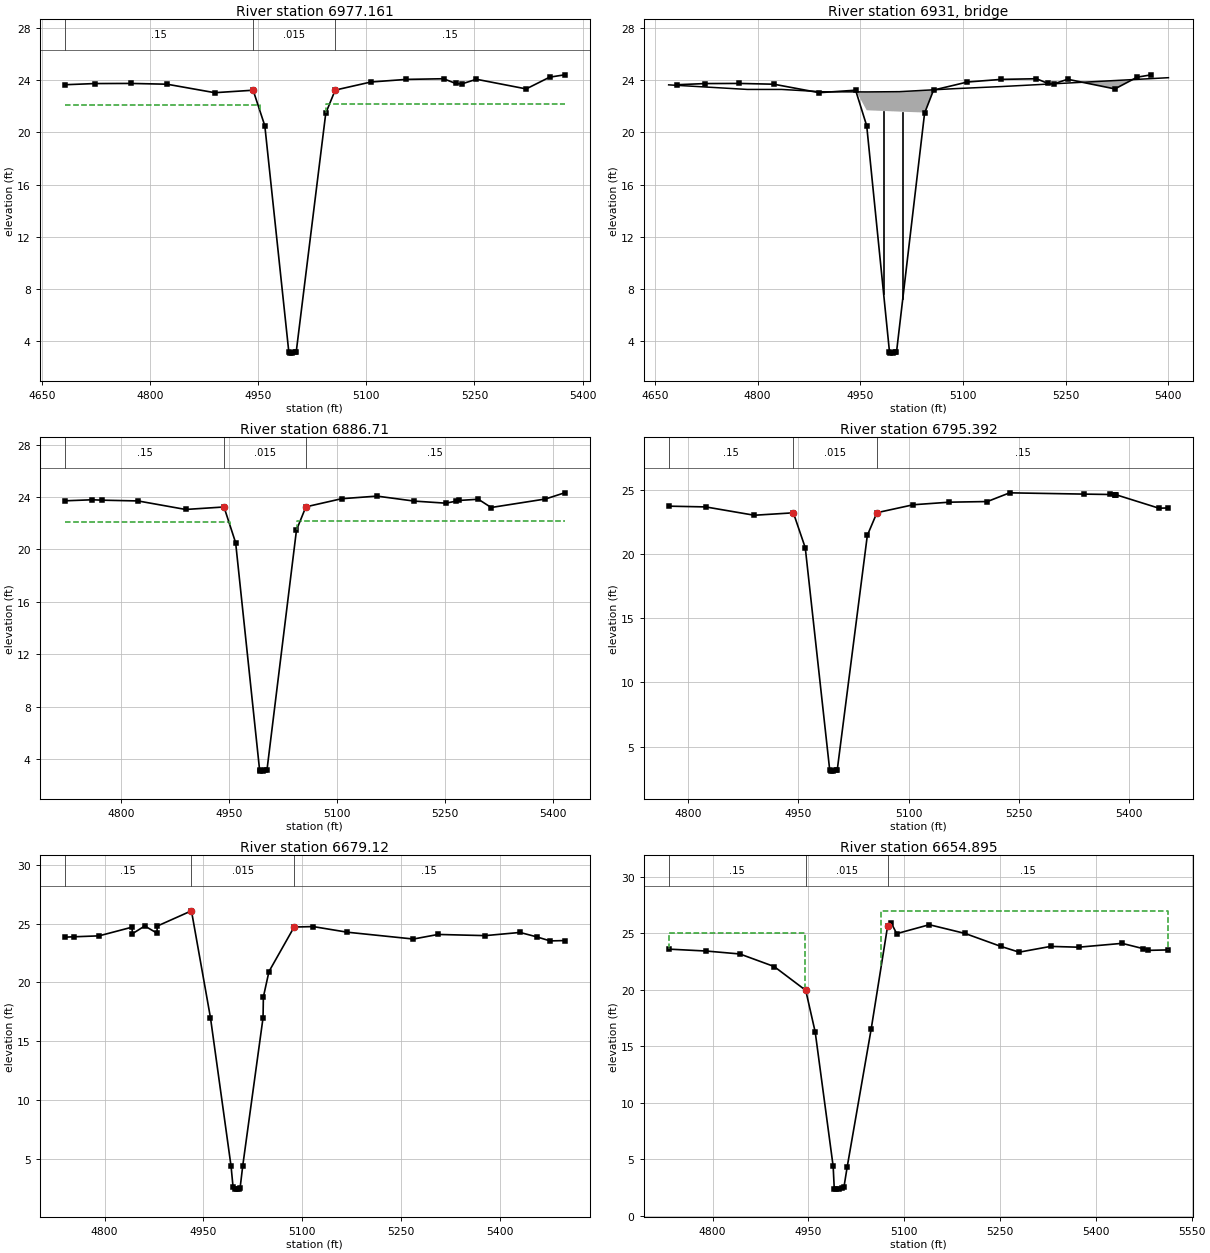
Type RM Length L Ch R = 1 ,6977.161,84.17,90.45,89.05
XS GIS Cut Line= 6
     3173475.613    13825527.371     3173697.512    13825537.827
     3173736.437    13825540.727     3173850.079    13825547.149
     3174016.999     13825552.93      3174168.03    13825557.578
#Sta/Elev= 23
 4681.86   23.66 4723.34   23.75 4773.22   23.76  4823.7    23.7 4889.83   23.05
 4943.09   23.24 4959.29   20.51  4992.5     3.2 4993.68    3.08  4997.2    3.12
 5000.49    3.14 5002.77    3.14 5043.82   21.48 5056.91   23.25 5106.45   23.87
  5155.7   24.07 5207.26   24.12 5223.88   23.76 5232.23   23.72 5252.72   24.08
 5321.77   23.34 5354.29   24.24 5374.98   24.42
#Mann= 3 ,-1 , 0
 4681.86     .15       0 4943.09    .015       0 5056.91     .15       0
#XS Ineff= 2 , 0
       0    4952    22.1    5044       0    22.2
Permanent Ineff=
       F       F
Bank Sta=4943.09,5056.91
XS Rating Curve= 0
Exp/Cntr=.5,.3

Type RM Length L Ch R = 3 ,6931    ,,,
BEGIN DESCRIPTION:
EAGLE ST
END DESCRIPTION:
Bridge Culvert--1,0,-1,-1, 0
Deck Dist Width WeirC Skew NumUp NumDn MinLoCord MaxHiCord MaxSubmerge Is_Ogee
10,63,2.6,0, 9, 9, , , .95, 0, 0,0,,
    4670    4785    4835    4895    4960    5007    5088    5156    5400
   23.65    23.3    23.3   23.12   23.11   23.13   23.36   23.52    24.2
                            21.7    21.7    21.6   21.44
    4670    4785    4835    4895    4960    5007    5088    5156    5400
   23.65    23.3    23.3   23.12   23.11   23.13   23.36   23.52    24.2
                            21.7    21.7    21.6   21.44
Pier Skew, UpSta & Num, DnSta & Num=  ,4984, 4 ,4984, 4 , 3 , 3 , 0 ,,
     1.2     1.2       2       2
       2   19.49    19.5      22
     1.2     1.2       2       2
       2   19.49    19.5      22
Pier Skew, UpSta & Num, DnSta & Num=  ,5012, 4 ,5012, 4 , 3 , 3 , 0 ,,
     1.2     1.2       2       2
       2   19.49    19.5      22
     1.2     1.2       2       2
       2   19.49    19.5      22
BR Coef=-1 , 1 , 0 ,, 0 ,,,.8,-1,2,0,
WSPro=,,,, 1 ,,,, 0 ,,,, 0 ,,,,-1 ,-1 ,-1 , 0 , 0 , 0 , 0 , 0
BC Design=,, 0 ,, 0 ,,,,,,
BC HTab HWMax=24.42

Type RM Length L Ch R = 1 ,6886.71 ,63.63,91.32,121.9
XS GIS Cut Line= 6
     3173471.847    13825607.283     3173692.656    13825617.687
     3173731.208    13825620.559     3173846.437    13825627.071
     3174014.385    13825632.888      3174165.57     13825637.54
#Sta/Elev= 24
 4721.88   23.71 4759.87   23.79 4773.22   23.76  4823.7    23.7 4889.83   23.05
 4943.09   23.24 4959.29   20.51  4992.5     3.2 4993.68    3.08  4997.2    3.12
 5000.49    3.14 5002.77    3.14 5043.82   21.48 5056.91   23.25 5106.45   23.87
  5155.7   24.07 5207.26   23.69 5251.32   23.53 5265.05   23.68  5270.3   23.74
 5296.51   23.83 5314.32    23.2 5389.81   23.85 5416.31   24.32
#Mann= 3 ,-1 , 0
 4721.88     .15       0 4943.09    .015       0 5056.91     .15       0
#XS Ineff= 2 , 0
       0    4952    22.1    5044       0    22.2
Permanent Ineff=
       F       F
Bank Sta=4943.09,5056.91
XS Rating Curve= 0
Exp/Cntr=.5,.3

Type RM Length L Ch R = 1 ,6795.392,123.17,116.27,89.24
XS GIS Cut Line= 6
      3173482.63    13825656.142     3173687.801    13825697.547
      3173725.98    13825700.391     3173864.203    13825726.685
     3174034.147    13825765.163     3174146.374    13825787.609
#Sta/Elev= 23
 4773.22   23.76  4823.7    23.7 4889.83   23.05 4943.09   23.24 4959.29   20.51
  4992.5     3.2 4993.68    3.08  4997.2    3.12 5000.49    3.14 5002.77    3.14
 5043.82   21.48 5056.91   23.25 5106.45   23.87  5155.7   24.07 5207.26   24.12
 5237.66    24.8 5339.47    24.7  5374.5   24.67 5381.14   24.66 5381.69   24.66
 5381.97   24.66 5441.01    23.6 5453.92   23.62
#Mann= 3 ,-1 , 0
 4773.22     .15       0 4943.09    .015       0 5056.91     .15       0
Bank Sta=4943.09,5056.91
XS Rating Curve= 0
Exp/Cntr=.3,.1

Type RM Length L Ch R = 1 ,6679.12 ,25.82,24.23,21.43
XS GIS Cut Line= 3
     3173364.753    13825753.637     3173679.331    13825793.649
     3174118.102    13825847.461
#Sta/Elev= 30
 4739.61   23.85 4752.91   23.88 4791.68   23.96  4841.8    24.7 4842.27   24.14
 4861.09    24.8 4879.71   24.19 4879.97   24.79 4932.02   26.09 4960.93   16.99
 4992.19    4.36 4995.21     2.6 4998.32    2.41 5001.38    2.45    5005    2.41
    5006    2.54 5009.97    4.41 5040.78   16.99 5041.28   18.76 5049.75   20.92
 5087.98   24.71 5116.86   24.75 5168.82   24.27 5269.19   23.69 5306.67   24.08
 5378.34   23.98 5431.06   24.25 5456.19   23.88 5476.91   23.53 5498.78   23.56
#Mann= 3 ,-1 , 0
 4739.61     .15       0 4932.02    .015       0 5087.98     .15       0
Bank Sta=4932.02,5087.98
XS Rating Curve= 0
Exp/Cntr=.5,.3

Type RM Length L Ch R = 1 ,6654.895,345.15,360,362.84
XS GIS Cut Line= 3
     3173362.229    13825773.477     3173676.852    13825813.495
     3174115.668    13825867.312
#Sta/Elev= 27
 4731.35   23.61 4790.22   23.44 4842.84   23.18 4896.42   22.07 4945.91   19.96
 4960.73   16.27 4988.86    4.37 4990.55    2.41 4994.01    2.36 4998.28    2.39
 5003.38    2.45 5005.67    2.52 5010.88    4.35 5048.46   16.57 5074.09   25.65
  5079.5   25.95 5088.29   24.98 5139.32   25.77 5195.12      25 5250.89   23.86
 5280.01   23.34 5329.22   23.85 5373.11   23.78 5441.09   24.12  5473.5   23.66
 5482.43    23.5 5513.64   23.54
#Mann= 3 ,-1 , 0
 4731.35     .15       0 4945.91    .015       0 5074.09     .15       0
#XS Ineff= 2 , 0
       0  4944.5      25    5064       0      27
Permanent Ineff=
       F       F
Bank Sta=4945.91,5074.09
XS Rating Curve= 0
Exp/Cntr=.5,.3

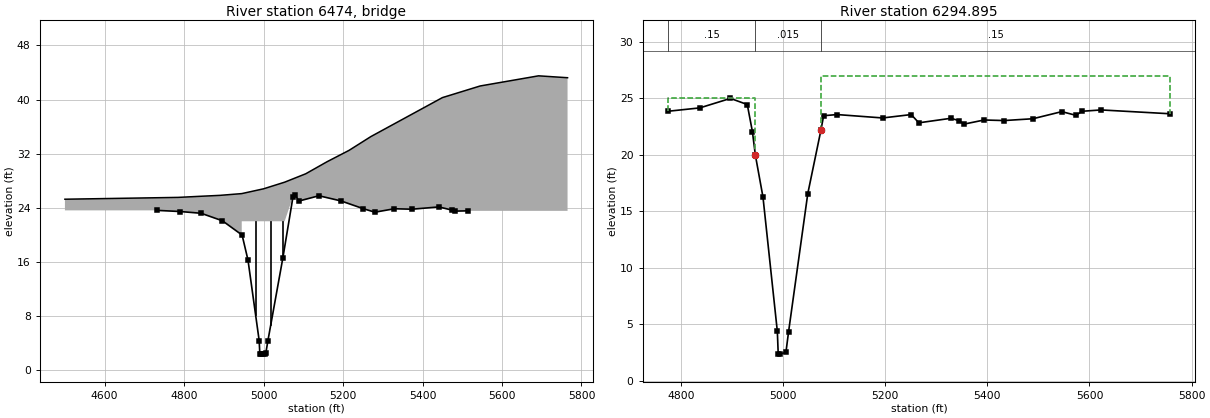
Type RM Length L Ch R = 3 ,6474    ,,,
BEGIN DESCRIPTION:
HWY 225
END DESCRIPTION:
Bridge Culvert--1,0,-1,-1, 0
Deck Dist Width WeirC Skew NumUp NumDn MinLoCord MaxHiCord MaxSubmerge Is_Ogee
16,335,2.6,0, 15, 15, , , .95, 0, 0,0,,
    4500    4785    4840    4890    4945    5000    5053    5106    5160    5215
    5270    5450    5545    5692    5765
   25.26   25.53   25.69   25.83   26.09    26.8   27.78   29.02   30.81   32.48
   34.52   40.28      42    43.5   43.22
                                      22      22      22      22
                                        
    4500    4785    4840    4890    4945    5000    5053    5106    5160    5215
    5270    5450    5545    5692    5765
   25.26   25.53   25.69   25.83   26.09    26.8   27.78   29.02   30.81   32.48
   34.52   40.28      42    43.5   43.22
                                      22      22      22      22
                                        
Pier Skew, UpSta & Num, DnSta & Num=  ,4980, 4 ,4980, 4 , 3 , 3 , 0 ,,
     1.2     1.2       2       2
       1      20      20      23
     1.2     1.2       2       2
       1      20      20      23
Pier Skew, UpSta & Num, DnSta & Num=  ,5018, 4 ,5018, 4 , 3 , 3 , 0 ,,
     1.2     1.2       2       2
       1      20      20      23
     1.2     1.2       2       2
       1      20      20      23
Pier Skew, UpSta & Num, DnSta & Num=  ,5048, 2 ,5048, 2 , 0 , 0 , 0 ,,
     1.2     1.2
      13      23
     1.2     1.2
      13      23
BR Coef=-1 , 1 , 0 ,, 0 ,,,.8,-1,2,0,
WSPro=,,,, 1 ,,,, 0 ,,,, 0 ,,,,-1 ,-1 ,-1 , 0 , 0 , 0 , 0 , 0
BC Design=,, 0 ,, 0 ,,,,,,
BC HTab HWMax=25.95

Type RM Length L Ch R = 1 ,6294.895,186.74,139.79,105.6
XS GIS Cut Line= 3
     3173129.839    13825999.844      3173440.93    13826076.831
     3174099.247    13826160.103
#Sta/Elev= 30
 4774.17   23.86    4837   24.16    4897      25    4930   24.46    4940   22.07
 4945.91   19.96 4960.73   16.27 4988.86    4.37 4990.55    2.41 4994.01    2.36
 5005.67    2.52 5010.88    4.35 5048.46   16.57 5074.09   22.17  5079.5   23.47
    5106   23.57 5195.12   23.27 5250.89   23.57  5265.9   22.84 5328.65   23.24
 5344.79   23.03 5353.88   22.72 5393.76   23.09 5432.73   23.04 5489.15    23.2
 5545.73   23.83  5573.7    23.5  5584.9   23.86 5622.88   23.98 5758.21   23.64
#Mann= 3 ,-1 , 0
 4774.17     .15       0 4945.91    .015       0 5074.09     .15       0
#XS Ineff= 2 , 0
       0  4944.5      25    5074       0      27
Permanent Ineff=
       F       F
Bank Sta=4945.91,5074.09
XS Rating Curve= 0
Exp/Cntr=.5,.3