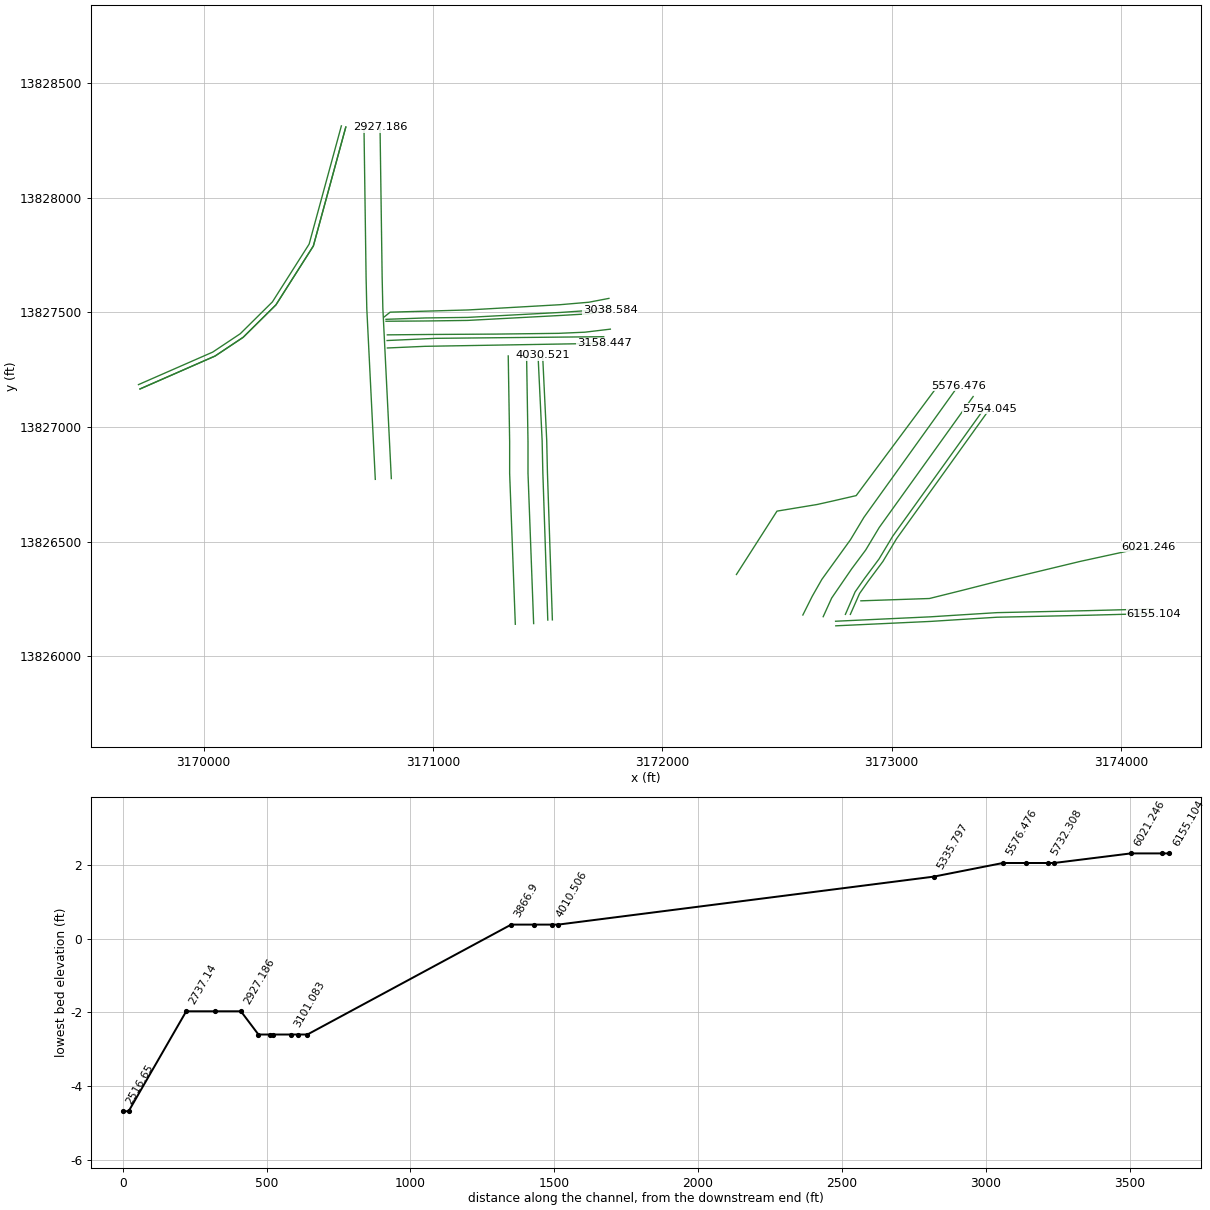
HEC-RAS study I101-00-00.prj: I101-00-00

--- I101-00-00.g03 (geometry) --- (continued)

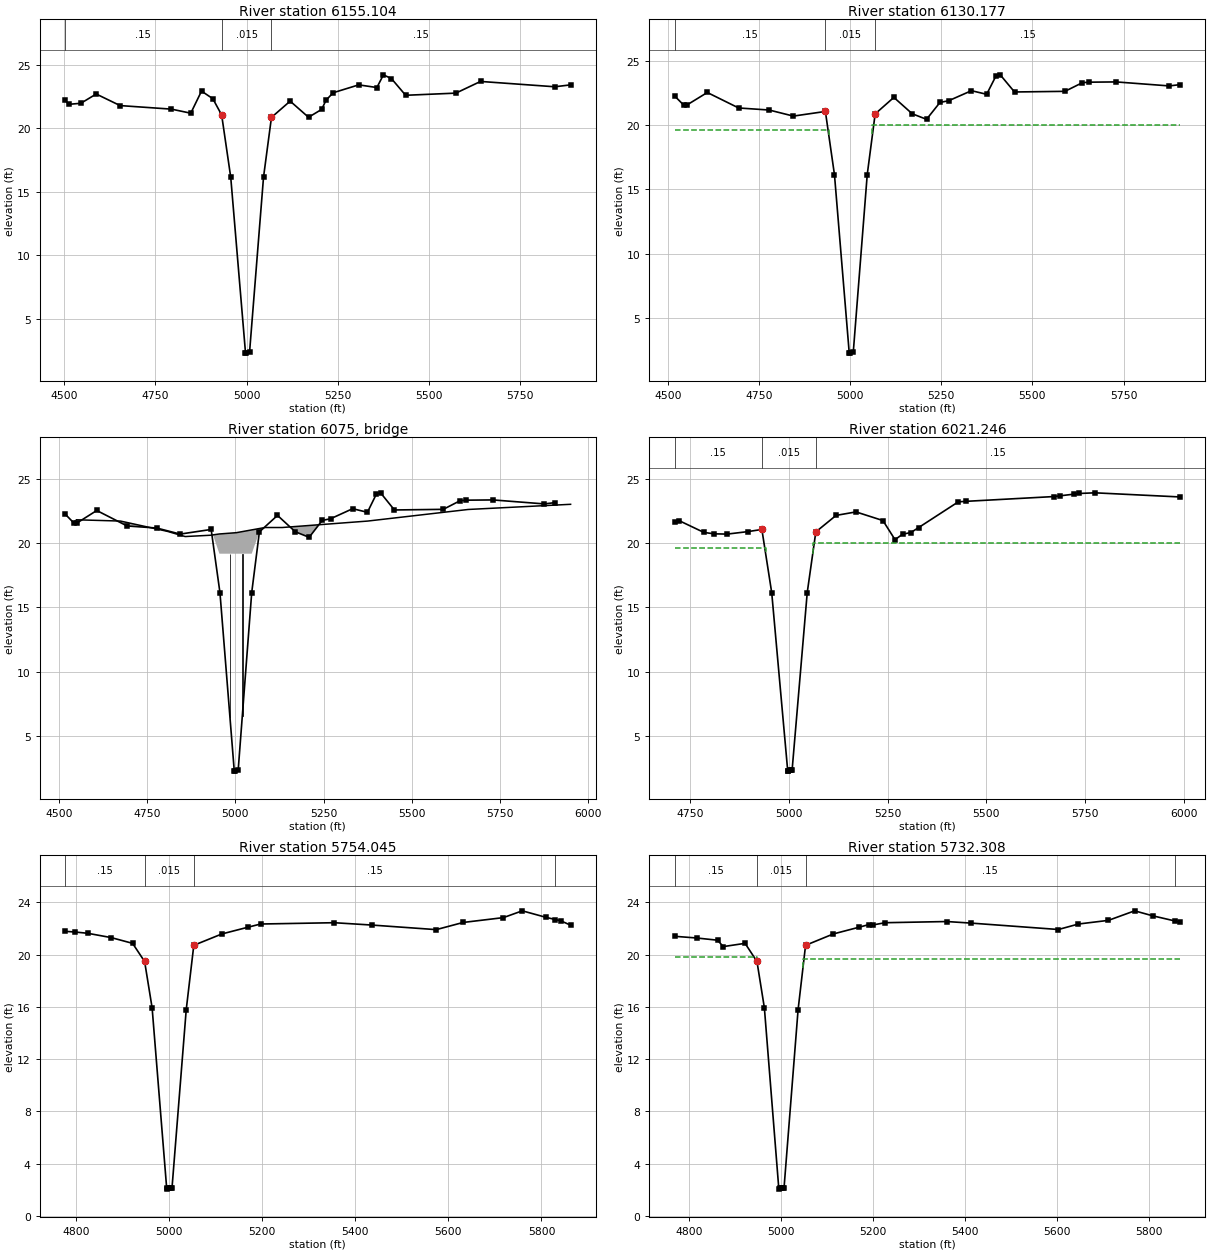
Type RM Length L Ch R = 1 ,6155.104,27.57,24.93,28.18
XS GIS Cut Line= 6
     3172756.257    13826133.514     3173169.977    13826152.771
     3173306.505    13826161.467     3173459.319    13826170.991
      3173858.22      13826179.7     3174142.281    13826187.198
#Sta/Elev= 30
 4501.98   22.19 4512.43   21.89 4545.18   21.97 4587.44    22.7 4653.03   21.79
 4793.96   21.51 4846.92   21.19  4876.4   22.93  4907.5   22.33 4931.68   21.05
 4956.63   16.14 4997.06    2.35 4998.03    2.31 5008.28     2.4 5046.57   16.16
 5068.32   20.86 5119.62   22.14 5170.05   20.87 5206.06   21.49 5218.28   22.22
 5237.63    22.8  5307.8   23.42 5357.61   23.21 5375.61   24.21 5397.63   23.91
 5436.58    22.6 5574.36   22.77 5642.08   23.69 5845.79   23.27 5889.22   23.42
#Mann= 3 ,-1 , 0
 4501.98     .15       0 4931.68    .015       0 5068.32     .15       0
Bank Sta=4931.68,5068.32
XS Rating Curve= 0
Exp/Cntr=.5,.3

Type RM Length L Ch R = 1 ,6130.177,115.99,108.93,172.09
XS GIS Cut Line= 6
     3172755.327    13826153.492     3173168.876    13826172.741
     3173305.247    13826181.427     3173458.478    13826190.977
     3173857.738    13826199.694     3174141.753    13826207.191
#Sta/Elev= 30
  4517.8   22.25 4542.97   21.54 4552.14   21.56 4607.56   22.52 4693.58   21.32
 4777.43   21.16 4843.75   20.69 4931.68   21.05 4956.63   16.14 4997.06    2.35
 4998.03    2.31 5008.28     2.4 5046.57   16.16 5068.32   20.86 5119.62   22.14
 5170.05   20.87  5209.3   20.44 5246.23   21.75 5270.01   21.88 5332.62   22.66
 5374.36   22.38 5400.03   23.81 5411.62   23.89 5450.84   22.56 5589.29   22.61
 5637.01   23.28 5654.85   23.32 5729.89   23.34  5875.5   23.03 5905.44   23.13
#Mann= 3 ,-1 , 0
  4517.8     .15       0 4931.68    .015       0 5068.32     .15       0
#XS Ineff= 2 , 0
       0    4941    19.6    5061       0      20
Permanent Ineff=
       F       F
Bank Sta=4931.68,5068.32
XS Rating Curve= 0
Exp/Cntr=.5,.3

Type RM Length L Ch R = 3 ,6075    ,,,
BEGIN DESCRIPTION:
SHAW ST
END DESCRIPTION:
Bridge Culvert--1,0,-1,-1, 0
Deck Dist Width WeirC Skew NumUp NumDn MinLoCord MaxHiCord MaxSubmerge Is_Ogee
20,60,2.6,0, 12, 12, , , .95, 0, 0,0,,
    4550    4675    4808    4858    4929    4955    5003    5084    5133    5375
    5660    5950
    21.8    21.7    20.9    20.5    20.6    20.7    20.8    21.2    21.2    21.7
    22.6      23
                                   19.17   19.17   19.17   19.17   19.17
                
    4550    4675    4808    4858    4929    4955    5003    5084    5133    5375
    5660    5950
    21.8    21.7    20.9    20.5    20.6    20.7    20.8    21.2    21.2    21.7
    22.6      23
                                   19.17   19.17   19.17   19.17   19.17
                
Pier Skew, UpSta & Num, DnSta & Num=  ,4985, 4 ,4985, 4 , 3 , 3 , 0 ,,
       1       1       2       2
       2   17.17   17.17      20
       1       1       2       2
       2   17.17   17.17      20
Pier Skew, UpSta & Num, DnSta & Num=  ,5020, 4 ,5020, 4 , 3 , 3 , 0 ,,
     1.5     1.5       2       2
       2   17.17   17.17      20
     1.5     1.5       2       2
       2   17.17   17.17      20
BR Coef=-1 , 1 , 0 ,, 0 ,,,.8,-1,2,0,
WSPro=,,,, 1 ,,,, 0 ,,,, 0 ,,,,-1 ,-1 ,-1 , 0 , 0 , 0 , 0 , 0
BC Design=,, 0 ,, 0 ,,,,,,
BC HTab HWMax=23.89

Type RM Length L Ch R = 1 ,6021.246,114.69,267.2,441.98
XS GIS Cut Line= 6
     3172865.578    13826242.496     3173164.473    13826252.623
     3173309.452      13826288.7     3173473.993    13826330.642
     3173822.434    13826414.526     3174119.254    13826479.052
#Sta/Elev= 30
 4710.63   21.64 4722.97   21.72 4784.77   20.82 4810.94   20.71 4843.75   20.69
 4895.66   20.88 4931.68   21.05 4956.63   16.14 4997.06    2.35 4998.03    2.31
 5002.57    2.37 5006.64     2.4 5008.28     2.4 5046.57   16.16 5068.32   20.86
 5119.62   22.14 5170.05   22.41 5238.26   21.74 5268.87   20.26 5288.04   20.68
 5309.15   20.81  5328.9    21.2 5429.13   23.19 5448.73   23.23 5670.75    23.6
  5687.3   23.66 5722.79   23.79 5734.49   23.84 5775.67   23.89 5991.05   23.57
#Mann= 3 ,-1 , 0
 4710.63     .15       0 4931.68    .015       0 5068.32     .15       0
#XS Ineff= 2 , 0
       0    4941    19.6  5060.5       0      20
Permanent Ineff=
       F       F
Bank Sta=4931.68,5068.32
XS Rating Curve= 0
Exp/Cntr=.5,.3

Type RM Length L Ch R = 1 ,5754.045,20.87,21.74,20.92
XS GIS Cut Line= 6
     3172819.649    13826183.399      3172859.84    13826274.378
     3172897.953    13826328.662     3172961.471    13826414.019
     3173020.896    13826512.955     3173428.223    13827080.742
#Sta/Elev= 27
 4776.21   21.79 4797.15   21.74 4824.86   21.64 4875.37   21.31 4921.29   20.87
 4947.16   19.48 4963.28   15.93 4994.72    2.05 4996.29     2.1 5000.04     2.1
 5004.69    2.13 5005.92     2.1 5036.57   15.79 5052.84   20.72 5113.22   21.59
 5168.64    22.1 5196.43   22.35  5354.6   22.45 5435.71   22.27 5573.78   21.92
 5631.73   22.47 5718.15   22.84 5758.74   23.36  5809.9   22.86    5830   22.69
 5841.32    22.6 5862.59   22.26
#Mann= 4 ,-1 , 0
 4776.21     .15       0 4947.16    .015       0 5052.84     .15       0
    5830     .07       0
Bank Sta=4947.16,5052.84
XS Rating Curve= 0
Exp/Cntr=.5,.3

Type RM Length L Ch R = 1 ,5732.308,73.06,74.86,73.22
XS GIS Cut Line= 6
     3172798.072    13826183.399      3172840.49    13826281.624
     3172881.743     13826340.38     3172944.835    13826425.165
      3173004.17    13826523.951     3173411.972      13827092.4
#Sta/Elev= 28
 4768.05   21.41 4815.98   21.28 4861.62   21.11  4873.7   20.62 4921.29   20.87
 4947.16   19.48 4963.28   15.93 4994.72    2.05 4996.29     2.1 5000.04     2.1
 5004.69    2.13 5005.92     2.1 5036.57   15.79 5052.84   20.72 5113.22   21.59
 5168.64    22.1 5190.94   22.31 5199.68   22.28  5225.7   22.45 5359.79   22.54
 5412.86   22.42  5602.6   21.93 5646.27   22.35 5711.39   22.63  5768.4   23.36
  5807.5   22.98 5856.36   22.58 5867.35   22.49
#Mann= 4 ,-1 , 0
 4768.05     .15       0 4947.16    .015       0 5052.84     .15       0
 5856.36     .07       0
#XS Ineff= 2 , 0
       0    4948    19.8    5047       0    19.7
Permanent Ineff=
       F       F
Bank Sta=4947.16,5052.84
XS Rating Curve= 0
Exp/Cntr=.5,.3

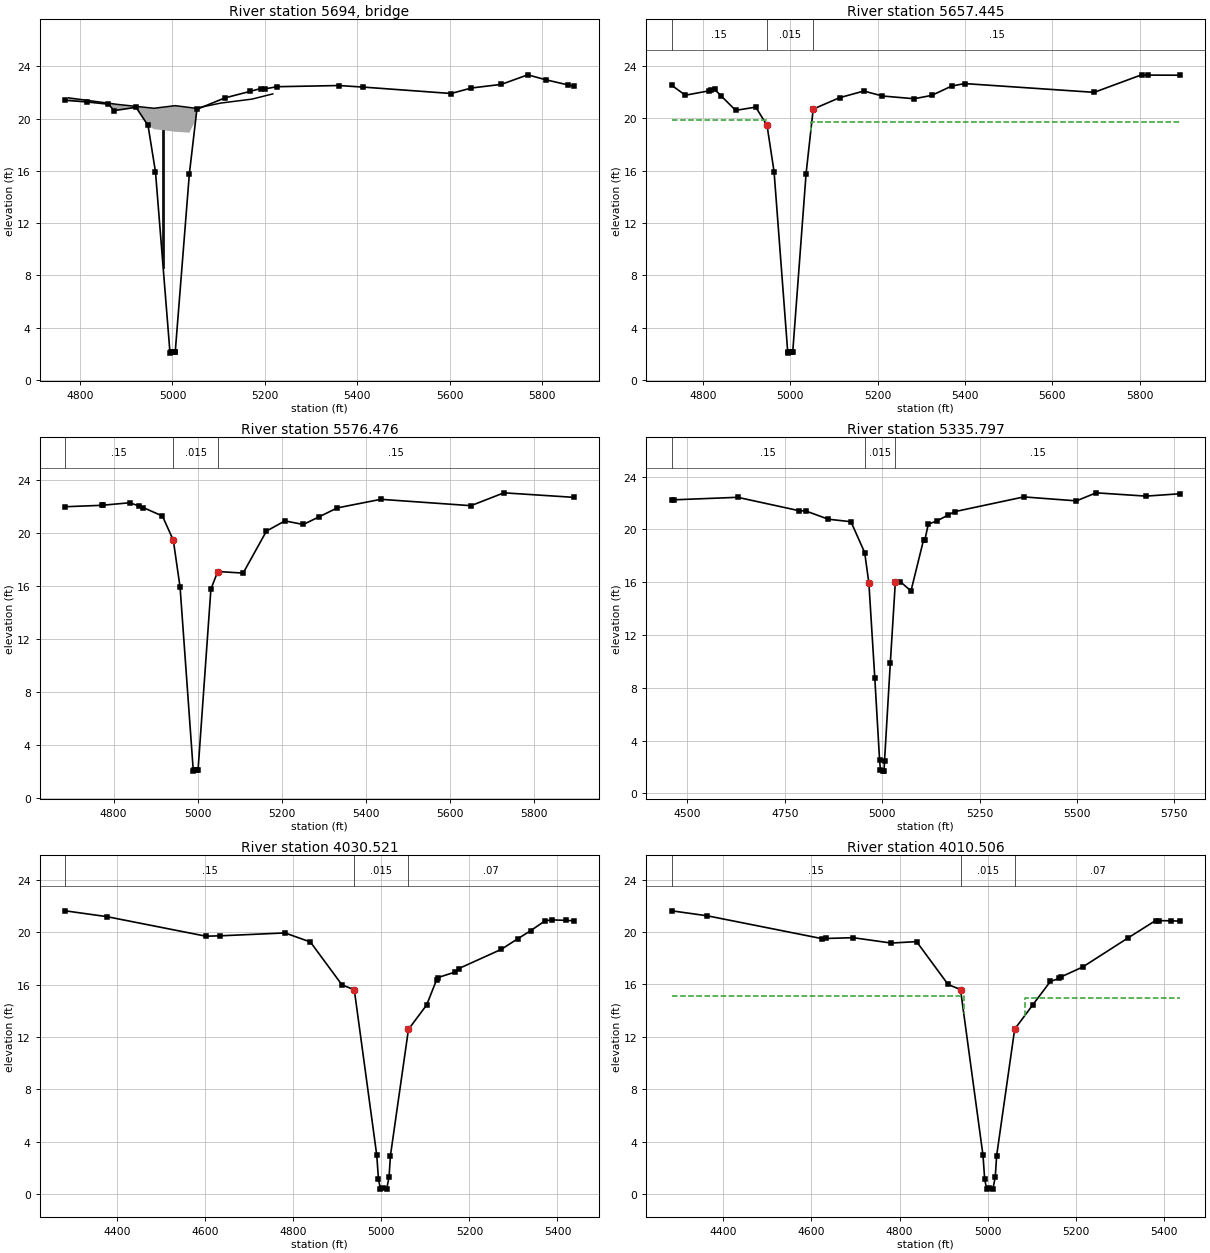
Type RM Length L Ch R = 3 ,5694    ,,,
BEGIN DESCRIPTION:
MC MASTERS AVE
END DESCRIPTION:
Bridge Culvert--1,0,-1,-1, 0
Deck Dist Width WeirC Skew NumUp NumDn MinLoCord MaxHiCord MaxSubmerge Is_Ogee
10,45,2.6,0, 8, 8, , , .95, 0, 0,0,,
    4775    4880    4960    5006    5050    5105    5172    5217
    21.6    21.1    20.8      21    20.8    21.2    21.5    21.9
            19.2    19.2      19    18.9    18.8
    4775    4880    4960    5006    5050    5105    5172    5217
    21.6    21.1    20.8      21    20.8    21.2    21.5    21.9
            19.2    19.2      19    18.9    18.8
Pier Skew, UpSta & Num, DnSta & Num=  ,4978, 4 ,4978, 4 , 3 , 3 , 0 ,,
     1.2     1.2       2       2
       3    17.2    17.2      20
     1.2     1.2       2       2
       3    17.2    17.2      20
Pier Skew, UpSta & Num, DnSta & Num=  ,4980, 4 ,4980, 4 , 3 , 3 , 0 ,,
     1.2     1.2       2       2
       3    17.2    17.2      20
     1.2     1.2       2       2
       3    17.2    17.2      20
BR Coef=-1 , 1 , 0 ,, 0 ,,,.8,-1,2,0,
WSPro=,,,, 1 ,,,, 0 ,,,, 0 ,,,,-1 ,-1 ,-1 , 0 , 0 , 0 , 0 , 0
BC Design=,, 0 ,, 0 ,,,,,,
BC HTab HWMax=23.36

Type RM Length L Ch R = 1 ,5657.445,83.5,80.97,83.68
XS GIS Cut Line= 6
     3172701.213    13826173.337     3172738.155    13826254.611
     3172825.009    13826381.394      3172886.61    13826464.176
      3172945.63    13826562.438     3173355.094    13827133.204
#Sta/Elev= 28
 4728.97   22.54 4760.32   21.78 4815.02   22.12 4818.25   22.15 4827.36   22.22
 4842.47   21.72 4875.37   20.62 4921.29   20.87 4947.16   19.48 4963.28   15.93
 4994.72    2.05 4996.29     2.1 5000.04     2.1 5004.69    2.13 5005.92     2.1
 5036.57   15.79 5052.84   20.72 5113.22   21.59 5168.64    22.1 5211.32   21.72
 5283.91   21.51  5324.4   21.77 5369.62   22.48 5399.34   22.67 5695.76      22
 5804.14   23.34 5818.01   23.32  5892.2   23.31
#Mann= 3 ,-1 , 0
 4728.97     .15       0 4947.16    .015       0 5052.84     .15       0
#XS Ineff= 2 , 0
       0    4948  19.848    5047       0    19.7
Permanent Ineff=
       F       F
Bank Sta=4947.16,5052.84
XS Rating Curve= 0
Exp/Cntr=.5,.3

Type RM Length L Ch R = 1 ,5576.476,329.21,240.68,82.85
XS GIS Cut Line= 6
      3172612.55    13826180.725     3172653.187    13826261.999
     3172695.365    13826335.968     3172820.068    13826508.761
     3172878.728    13826606.423     3173290.091    13827179.836
#Sta/Elev= 26
 4685.12   22.01 4773.62   22.12 4775.99   22.13 4838.48   22.31 4861.14   22.06
 4870.37   21.95 4916.29   21.31 4942.16   19.48 4958.28   15.93 4989.72    2.05
 4991.29     2.1 4995.04     2.1 4999.69    2.13 5000.92     2.1 5031.57   15.79
 5047.84   17.12 5108.22      17 5163.64   20.17 5207.56   20.94 5251.28   20.67
 5287.65   21.23 5331.95   21.92 5435.61   22.57 5649.97   22.09 5728.35   23.06
 5893.88   22.72
#Mann= 3 ,-1 , 0
 4685.12     .15       0 4942.16    .015       0 5047.84     .15       0
Bank Sta=4942.16,5047.84
XS Rating Curve= 0
Exp/Cntr=.3,.1

Type RM Length L Ch R = 1 ,5335.797,962.57,1305.28,1562.9
XS GIS Cut Line= 6
     3172322.947    13826357.362     3172499.751    13826633.618
      3172674.96    13826662.564     3172741.194    13826677.383
      3172845.07      13826701.3     3173218.014    13827202.703
#Sta/Elev= 30
 4459.76   22.27  4465.2   22.25 4629.18   22.44 4787.75   21.42 4803.52   21.41
 4861.82   20.78    4920   20.59 4955.23   18.25 4966.06   15.92 4981.18    8.75
 4993.49    2.52 4995.72    1.73  5001.3    1.71 5004.82    1.68 5006.16    2.44
 5021.01    9.87 5033.94   16.01 5047.14   16.03 5074.08   15.34 5106.63   19.24
 5109.79   19.22 5118.54    20.4  5139.8   20.64 5168.67   21.08 5185.84   21.35
 5363.86   22.47 5498.79   22.17 5549.34   22.78 5677.57   22.53 5764.69   22.71
#Mann= 3 ,-1 , 0
 4459.76     .15       0 4955.63    .015       0 5033.93     .15       0
Bank Sta=4966.06,5033.94
XS Rating Curve= 0
Exp/Cntr=.3,.1

Type RM Length L Ch R = 1 ,4030.521,20.01,20.01,20.6
XS GIS Cut Line= 4
     3171520.344    13826159.409     3171498.771    13826803.531
     3171495.685    13826942.387     3171477.852    13827313.367
#Sta/Elev= 28
 4281.73   21.65  4375.6   21.21 4601.38   19.71 4634.18   19.74 4781.01   19.96
 4838.67   19.27 4910.26      16 4938.48   15.61 4989.54    2.96 4993.36    1.14
 4997.67     .42 5004.17     .47 5011.87     .38 5017.39    1.29 5020.52    2.93
 5061.52   12.59 5102.72   14.45 5125.49   16.38 5127.58   16.54 5167.52   16.97
 5175.33   17.23 5272.06    18.7 5310.03   19.52 5338.96   20.13 5371.69   20.88
 5386.96   20.96 5419.37   20.92 5436.51   20.89
#Mann= 3 ,-1 , 0
 4281.73     .15       0 4938.48    .015       0 5061.52     .07       0
Bank Sta=4938.48,5061.52
XS Rating Curve= 0
Exp/Cntr=.5,.3

Type RM Length L Ch R = 1 ,4010.506,64.44,63.47,55.71
XS GIS Cut Line= 4
     3171500.356     13826158.74     3171478.778    13826802.974
     3171475.696    13826941.685     3171457.875    13827312.406
#Sta/Elev= 27
 4282.49   21.62 4363.41   21.24 4623.53    19.5 4632.76   19.51 4694.71   19.57
 4781.01   19.16 4838.67   19.27 4910.26      16 4938.48   15.61 4989.54    2.96
 4993.36    1.14 4997.67     .42 5004.17     .47 5011.87     .38 5017.39    1.29
 5020.52    2.93 5061.52   12.59 5102.72   14.45 5142.82   16.24 5163.02   16.46
 5166.97   16.58  5215.9   17.33 5318.88   19.55 5381.62   20.88  5389.8   20.87
 5417.28   20.86 5436.98   20.83
#Mann= 3 ,-1 , 0
 4282.49     .15       0 4938.48    .015       0 5061.52     .07       0
#XS Ineff= 2 , 0
       0    4946    15.1    5084       0      15
Permanent Ineff=
       F       F
Bank Sta=4938.48,5061.52
XS Rating Curve= 0
Exp/Cntr=.5,.3

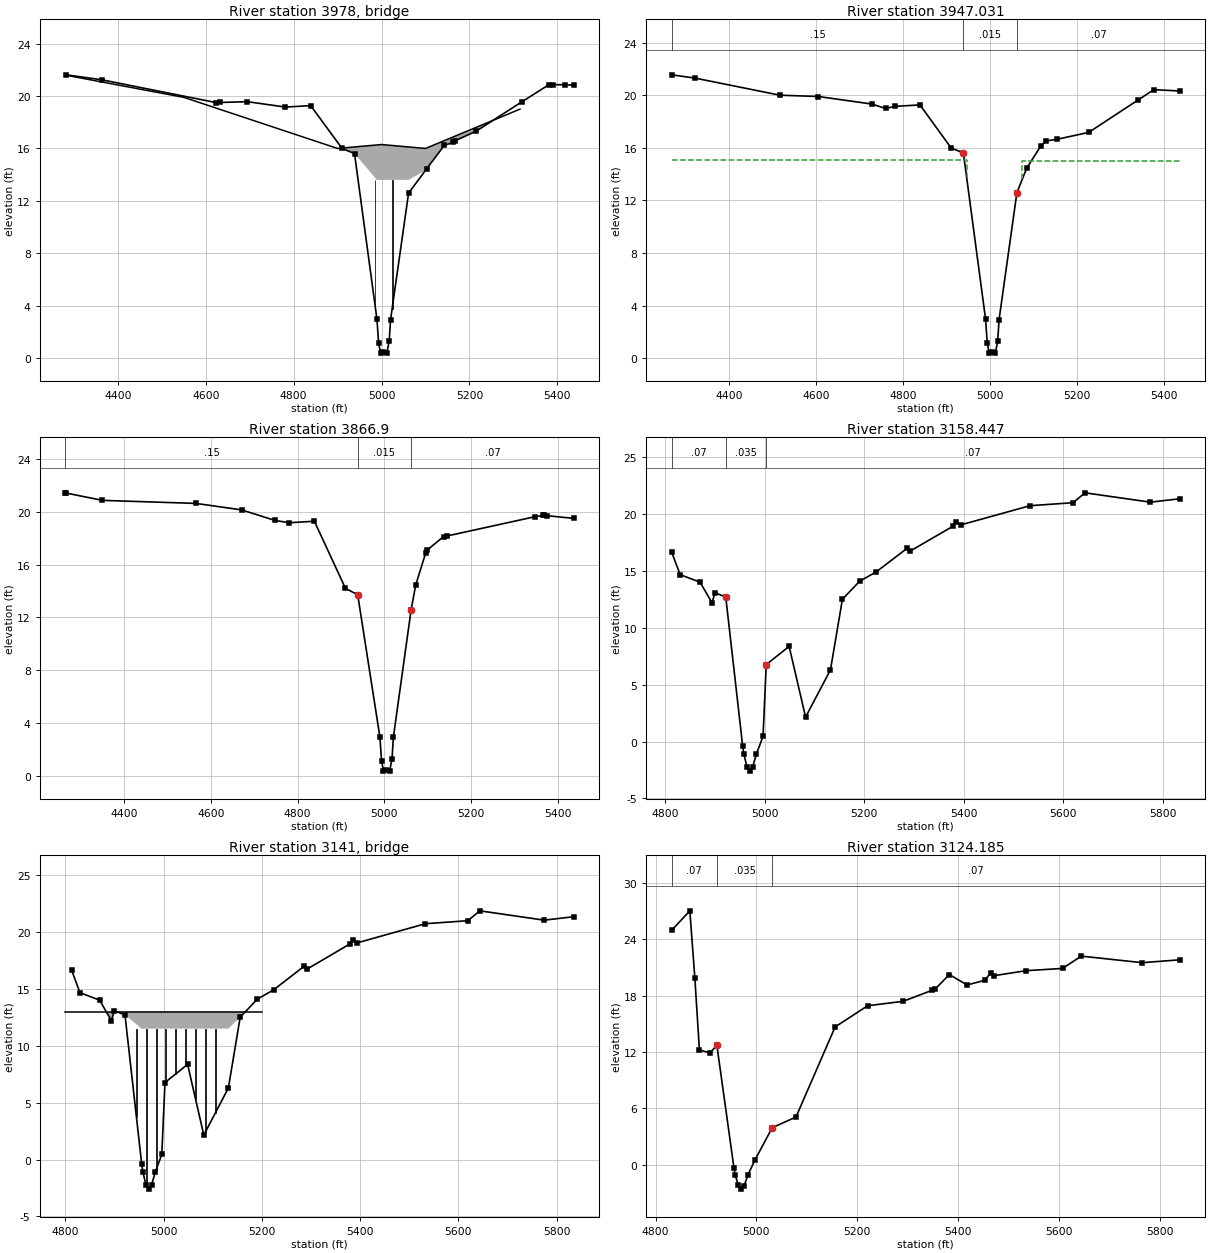
Type RM Length L Ch R = 3 ,3978    ,,,
BEGIN DESCRIPTION:
MAIN ST
END DESCRIPTION:
Bridge Culvert--1,0,-1,-1, 0
Deck Dist Width WeirC Skew NumUp NumDn MinLoCord MaxHiCord MaxSubmerge Is_Ogee
12,36,2.6,0, 6, 6, , , .95, 0, 0,0,,
    4280    4550    4900    5000    5100    5315
    21.6    19.9      16    16.3      16      19
                    13.6    13.6    13.6
    4280    4550    4900    5000    5100    5315
    21.6    19.9      16    16.3      16      19
                    13.6    13.6    13.6
Pier Skew, UpSta & Num, DnSta & Num=  ,4985, 4 ,4985, 4 , 3 , 3 , 0 ,,
     1.2     1.2       2       2
       2    11.6    11.6      14
     1.2     1.2       2       2
       2    11.6    11.6      14
Pier Skew, UpSta & Num, DnSta & Num=  ,5024, 4 ,5024, 4 , 3 , 3 , 0 ,,
     1.2     1.2       2       2
       2    11.6    11.6      14
     1.2     1.2       2       2
       2    11.6    11.6      14
BR Coef=-1 , 1 , 0 ,, 0 ,,,.8,-1,2,0,
WSPro=,,,, 1 ,,,, 0 ,,,, 0 ,,,,-1 ,-1 ,-1 , 0 , 0 , 0 , 0 , 0
BC Design=,, 0 ,, 0 ,,,,,,
BC HTab HWMax=21.62

Type RM Length L Ch R = 1 ,3947.031,80.06,80.13,81.81
XS GIS Cut Line= 4
     3171438.706    13826143.327     3171414.047    13826799.892
     3171414.047    13826938.602     3171407.882     13827311.58
#Sta/Elev= 26
 4267.77   21.56 4321.69   21.31 4516.54   20.01 4604.99   19.91 4727.46   19.34
  4759.7      19 4781.01   19.16 4838.67   19.27 4910.26      16 4938.48   15.61
 4989.54    2.96 4993.36    1.14 4997.67     .42 5004.17     .47 5011.87     .38
 5017.39    1.29 5020.52    2.93 5061.52   12.59    5084   14.45 5117.08   16.18
 5129.21   16.53 5153.37   16.65 5226.71   17.18 5339.04   19.62 5376.32   20.43
 5436.54   20.33
#Mann= 3 ,-1 , 0
 4267.77     .15       0 4938.48    .015       0 5061.52     .07       0
#XS Ineff= 2 , 0
       0    4946    15.1    5074       0      15
Permanent Ineff=
       F       F
Bank Sta=4938.48,5061.52
XS Rating Curve= 0
Exp/Cntr=.5,.3

Type RM Length L Ch R = 1 ,3866.9  ,980.79,708.45,255.95
XS GIS Cut Line= 4
     3171358.763    13826140.325     3171334.047     13826798.39
     3171334.047    13826937.941     3171327.893    13827310.258
#Sta/Elev= 28
 4264.96   21.42 4267.57    21.4 4350.53   20.85 4565.87   20.62 4671.14   20.13
 4748.33   19.33 4781.01   19.16 4838.67   19.27 4910.26    14.2 4938.48   13.71
 4989.54    2.96 4993.36    1.14 4997.67     .42 5004.17     .47 5011.87     .38
 5017.39    1.29 5020.52    2.93 5061.52   12.59    5072   14.45 5095.11   16.89
 5098.46   17.09    5136   18.11 5144.68   18.16 5345.99   19.61 5365.47   19.71
 5368.04   19.71 5374.59   19.69 5435.41   19.49
#Mann= 3 ,-1 , 0
 4264.96     .15       0 4938.48    .015       0 5061.52     .07       0
Bank Sta=4938.48,5061.52
XS Rating Curve= 0
Exp/Cntr=.3,.1

Type RM Length L Ch R = 1 ,3158.447,32.6,34.26,34.68
XS GIS Cut Line= 3
     3170800.933    13827344.994     3170964.339    13827352.203
     3171746.526     13827365.42
#Sta/Elev= 30
    4813   16.64    4830   14.66    4870      14    4894    12.2    4900   13.06
 4921.61   12.71 4955.63     -.4 4958.02   -1.09 4964.17   -2.21 4969.56    -2.6
 4975.69   -2.24 4983.32   -1.08 4996.54     .45    5003    6.76    5049    8.36
    5082    2.15    5132    6.29    5156    12.5 5190.74   14.09 5223.84    14.9
  5285.8   16.97 5292.76   16.75 5378.47   18.92 5385.11   19.29 5393.63   19.03
 5532.99   20.72 5619.13   20.98 5643.65   21.85 5774.52   21.03 5834.25   21.33
#Mann= 3 ,-1 , 0
    4813     .07       0 4921.61    .035       0    5003     .07       0
Bank Sta=4921.61,5003
XS Rating Curve= 0
Exp/Cntr=.5,.3

Type RM Length L Ch R = 3 ,3141    ,,,
BEGIN DESCRIPTION:
PIPE CROSSING
END DESCRIPTION:
Bridge Culvert--1,0,-1,-1, 0
Deck Dist Width WeirC Skew NumUp NumDn MinLoCord MaxHiCord MaxSubmerge Is_Ogee
7,22,2.6,0, 2, 2, , , .95, 0, 0,0,,
    4800    5200
      13      13
    11.5    11.5
    4800    5200
      13      13
    11.5    11.5
Pier Skew, UpSta & Num, DnSta & Num=  ,4945, 4 ,4945, 4 , 3 , 3 , 0 ,,
    1.35    1.35       2       2
      -3     9.5     9.5    12.5
    1.35    1.35       2       2
      -3     9.5     9.5    12.5
Pier Skew, UpSta & Num, DnSta & Num=  ,4965, 4 ,4965, 4 , 3 , 3 , 0 ,,
    1.35    1.35       2       2
      -3     9.5     9.5    12.5
    1.35    1.35       2       2
      -3     9.5     9.5    12.5
Pier Skew, UpSta & Num, DnSta & Num=  ,4985, 4 ,4985, 4 , 3 , 3 , 0 ,,
    1.35    1.35       2       2
      -3     9.5     9.5    12.5
    1.35    1.35       2       2
      -3     9.5     9.5    12.5
Pier Skew, UpSta & Num, DnSta & Num=  ,5005, 4 ,5005, 4 , 3 , 3 , 0 ,,
    1.35    1.35       2       2
      -3     9.5     9.5    12.5
    1.35    1.35       2       2
      -3     9.5     9.5    12.5
Pier Skew, UpSta & Num, DnSta & Num=  ,5025, 4 ,5025, 4 , 3 , 3 , 0 ,,
    1.35    1.35       2       2
      -3     9.5     9.5    12.5
    1.35    1.35       2       2
      -3     9.5     9.5    12.5
Pier Skew, UpSta & Num, DnSta & Num=  ,5045, 4 ,5045, 4 , 3 , 3 , 0 ,,
    1.35    1.35       2       2
      -3     9.5     9.5    12.5
    1.35    1.35       2       2
      -3     9.5     9.5    12.5
Pier Skew, UpSta & Num, DnSta & Num=  ,5065, 4 ,5065, 4 , 3 , 3 , 0 ,,
    1.35    1.35       2       2
      -3     9.5     9.5    12.5
    1.35    1.35       2       2
      -3     9.5     9.5    12.5
Pier Skew, UpSta & Num, DnSta & Num=  ,5085, 4 ,5085, 4 , 3 , 3 , 0 ,,
    1.35    1.35       2       2
      -3     9.5     9.5    12.5
    1.35    1.35       2       2
      -3     9.5     9.5    12.5
Pier Skew, UpSta & Num, DnSta & Num=  ,5105, 4 ,5105, 4 , 3 , 3 , 0 ,,
    1.35    1.35       2       2
      -3     9.5     9.5    12.5
    1.35    1.35       2       2
      -3     9.5     9.5    12.5
BR Coef=-1 , 1 , 1 ,1.25, 0 ,,,.8,-1,2,0,
WSPro=,,,, 1 ,,,, 0 ,,,, 0 ,,,,-1 ,-1 ,-1 , 0 , 0 , 0 , 0 , 0
BC Design=,, 0 ,, 0 ,,,,,,
BC HTab HWMax=21.85

Type RM Length L Ch R = 1 ,3124.185,24.25,23.1,17.27
XS GIS Cut Line= 3
     3170799.732    13827377.435     3171011.199    13827387.047
     3171744.123    13827394.256
#Sta/Elev= 30
    4832   24.95    4868   27.02    4878   19.83    4887    12.2    4908   11.91
 4921.61   12.71 4955.63     -.4 4958.02   -1.09 4964.17   -2.21 4969.56    -2.6
 4975.69   -2.24 4983.32   -1.08 4996.54     .45 5031.36    3.94 5078.39    5.07
 5156.05   14.66 5220.58   16.92    5291   17.39  5348.2   18.56 5354.69   18.71
 5382.46   20.24 5417.68   19.13 5452.36   19.62 5465.05   20.45 5471.48   20.12
 5534.77   20.65 5606.98   20.89 5644.08    22.2    5765    21.5 5839.79   21.81
#Mann= 3 ,-1 , 0
    4832     .07       0 4921.61    .035       0 5031.36     .07       0
Bank Sta=4921.61,5031.36
XS Rating Curve= 0
Exp/Cntr=.5,.3

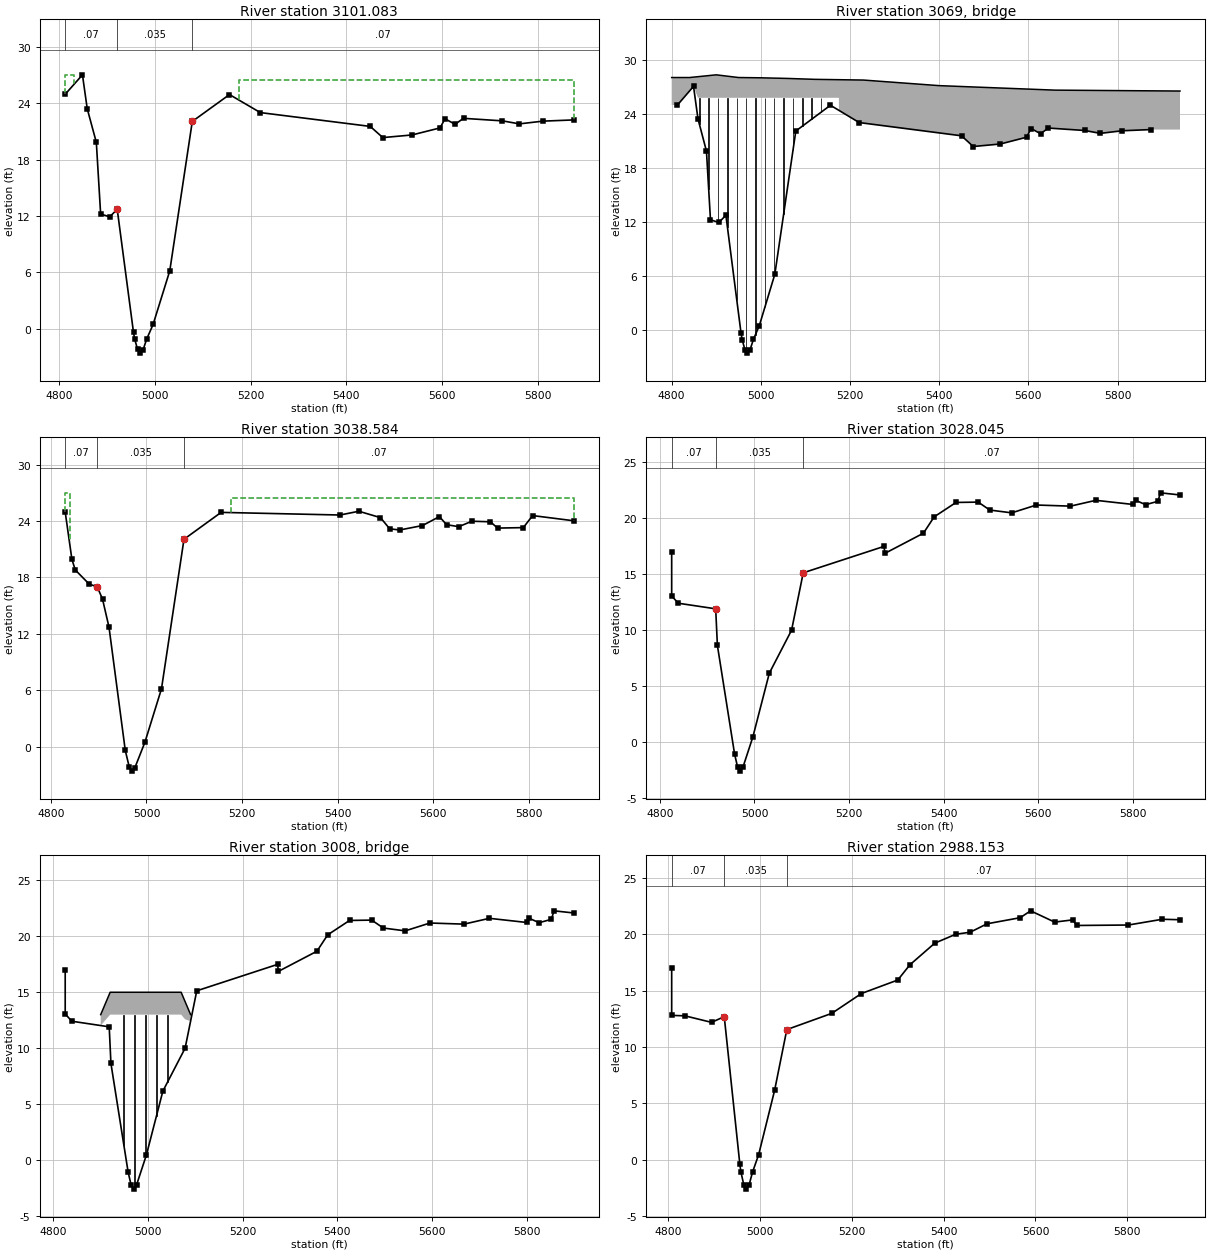
Type RM Length L Ch R = 1 ,3101.083,61.08,62.5,63.24
XS GIS Cut Line= 6
      3170800.76    13827402.206     3170983.294    13827403.866
     3171272.031    13827405.525     3171547.492    13827408.844
     3171661.991    13827413.822     3171773.171    13827427.097
#Sta/Elev= 29
    4813   24.95    4849   27.02    4859   23.41    4878   19.83    4887    12.2
    4906   11.91 4921.61   12.71 4955.63     -.4 4958.02   -1.09 4964.17   -2.21
 4969.56    -2.6 4975.69   -2.24 4983.32   -1.08 4996.54     .45 5031.36    6.16
 5078.39   22.06 5156.05   24.92 5220.58      23    5450   21.53  5476.3   20.34
 5537.25   20.62 5595.79   21.37 5606.09   22.34  5627.2   21.76 5644.78   22.39
 5726.15   22.12 5761.42    21.8 5810.49   22.09 5874.55   22.22
#Mann= 3 ,-1 , 0
    4813     .07       0 4921.61    .035       0 5078.39     .07       0
#XS Ineff= 2 , 0
       0    4832      27    5176       0    26.5
Permanent Ineff=
       F       F
Bank Sta=4921.61,5078.39
XS Rating Curve= 0
Exp/Cntr=.5,.3

Type RM Length L Ch R = 3 ,3069    ,,,
BEGIN DESCRIPTION:
RR BRIDGE
END DESCRIPTION:
Bridge Culvert--1,0,-1,-1, 0
Deck Dist Width WeirC Skew NumUp NumDn MinLoCord MaxHiCord MaxSubmerge Is_Ogee
15,40,2.6,0, 12, 12, , , .95, 0, 0,0,,
    4800    4840    4900    4950    5000    5060    5120    5175    5230    5400
    5660    5940
      28      28    28.3      28   27.97    27.9    27.8   27.76   27.72    27.1
    26.6    26.5
           25.75   25.75   25.75   25.75   25.75   25.75   25.75
                
    4800    4840    4900    4950    5000    5060    5120    5175    5230    5400
    5660    5940
      28      28    28.3      28   27.97    27.9    27.8   27.76   27.72    27.1
    26.6    26.5
           25.75   25.75   25.75   25.75   25.75   25.75   25.75
                
Pier Skew, UpSta & Num, DnSta & Num=  ,4862, 2 ,4862, 2 , 0 , 0 , 0 ,,
       1       1
      -3      26
       1       1
      -3      26
Pier Skew, UpSta & Num, DnSta & Num=  ,4883, 2 ,4883, 2 , 0 , 0 , 0 ,,
       1       1
      -3      26
       1       1
      -3      26
Pier Skew, UpSta & Num, DnSta & Num=  ,4904, 2 ,4904, 2 , 0 , 0 , 0 ,,
       1       1
      -3      26
       1       1
      -3      26
Pier Skew, UpSta & Num, DnSta & Num=  ,4925, 2 ,4925, 2 , 0 , 0 , 0 ,,
       1       1
      -3      26
       1       1
      -3      26
Pier Skew, UpSta & Num, DnSta & Num=  ,4946, 2 ,4946, 2 , 0 , 0 , 0 ,,
       1       1
      -3      26
       1       1
      -3      26
Pier Skew, UpSta & Num, DnSta & Num=  ,4967, 2 ,4967, 2 , 0 , 0 , 0 ,,
       1       1
      -3      26
       1       1
      -3      26
Pier Skew, UpSta & Num, DnSta & Num=  ,4988, 2 ,4988, 2 , 0 , 0 , 0 ,,
       1       1
      -3      26
       1       1
      -3      26
Pier Skew, UpSta & Num, DnSta & Num=  ,5009, 2 ,5009, 2 , 0 , 0 , 0 ,,
       1       1
      -3      26
       1       1
      -3      26
Pier Skew, UpSta & Num, DnSta & Num=  ,5030, 2 ,5030, 2 , 0 , 0 , 0 ,,
       1       1
      -3      26
       1       1
      -3      26
Pier Skew, UpSta & Num, DnSta & Num=  ,5051, 2 ,5051, 2 , 0 , 0 , 0 ,,
       1       1
      -3      26
       1       1
      -3      26
Pier Skew, UpSta & Num, DnSta & Num=  ,5072, 2 ,5072, 2 , 0 , 0 , 0 ,,
       1       1
      -3      26
       1       1
      -3      26
Pier Skew, UpSta & Num, DnSta & Num=  ,5093, 2 ,5093, 2 , 0 , 0 , 0 ,,
       1       1
      -3      26
       1       1
      -3      26
Pier Skew, UpSta & Num, DnSta & Num=  ,5114, 2 ,5114, 2 , 0 , 0 , 0 ,,
       1       1
      -3      26
       1       1
      -3      26
Pier Skew, UpSta & Num, DnSta & Num=  ,5135, 2 ,5135, 2 , 0 , 0 , 0 ,,
       1       1
      -3      26
       1       1
      -3      26
BR Coef=-1 , 1 , 1 ,.9, 0 ,,,.8,-1,1.2,0,
WSPro=,,,, 1 ,,,, 0 ,,,, 0 ,,,,-1 ,-1 ,-1 , 0 , 0 , 0 , 0 , 0
BC Design=,, 0 ,, 0 ,,,,,,
BC HTab HWMax=27.02

Type RM Length L Ch R = 1 ,3038.584,8.85,10.54,13.88
XS GIS Cut Line= 6
     3170794.926    13827461.541     3170969.146    13827462.742
     3171150.574    13827465.145     3171555.485    13827486.773
     3171679.241    13827493.982      3171772.96    13827510.803
#Sta/Elev= 30
    4830   24.95    4844   19.93    4851    18.8    4880    17.3    4897      17
    4908    15.7 4921.61   12.71 4955.63     -.4 4964.17   -2.21 4969.56    -2.6
 4975.69   -2.24 4996.54     .45 5031.36    6.16 5078.39   22.06 5156.05   24.92
 5404.72   24.64 5444.15   25.04 5489.37   24.36 5508.63   23.17 5529.73   23.05
 5577.15   23.52 5612.56   24.47 5627.58   23.61  5653.2    23.4 5680.36   23.98
 5719.33   23.92 5734.19   23.25 5788.01    23.3 5807.61   24.58 5893.09   24.03
#Mann= 3 ,-1 , 0
    4830     .07       0    4897    .035       0 5078.39     .07       0
#XS Ineff= 2 , 0
       0    4839      27    5176       0    26.5
Permanent Ineff=
       F       F
Bank Sta=4897,5078.39
XS Rating Curve= 0
Exp/Cntr=.5,.3

Type RM Length L Ch R = 1 ,3028.045,15.56,39.89,33.5
XS GIS Cut Line= 6
     3170794.926    13827469.951     3170966.743    13827475.959
     3171150.574    13827478.362     3171556.687    13827499.989
      3171678.04      13827508.4     3171771.758    13827526.423
#Sta/Elev= 30
    4825      17    4825   13.06    4839   12.41    4918   11.91 4921.61    8.64
 4958.02   -1.09 4964.17   -2.21 4969.56    -2.6 4975.69   -2.24 4996.54     .45
 5031.36    6.16 5078.39      10    5103   15.13 5273.65   17.49  5275.7   16.87
 5357.02   18.67 5379.65   20.13 5425.91   21.42 5472.71   21.45 5497.32   20.74
 5543.54   20.49 5595.76   21.19 5667.78   21.09 5721.37   21.61 5800.04   21.24
 5805.56   21.61 5826.55   21.22 5852.31   21.52 5858.02   22.28 5899.22   22.09
#Mann= 3 ,-1 , 0
    4825     .07       0    4918    .035       0    5103     .07       0
Bank Sta=4918,5103
XS Rating Curve= 0
Exp/Cntr=.5,.3

Type RM Length L Ch R = 3 ,3008    ,,,
BEGIN DESCRIPTION:
PIPE CROSSING
END DESCRIPTION:
Bridge Culvert--1,0,-1,-1, 0
Deck Dist Width WeirC Skew NumUp NumDn MinLoCord MaxHiCord MaxSubmerge Is_Ogee
5,20,2.6,0, 4, 4, , , .95, 0, 0,0,,
    4900    4920    5070    5090
      13      15      15      13
      12      13      13      12
    4900    4920    5070    5090
      13      15      15      13
      12      13      13      12
Pier Skew, UpSta & Num, DnSta & Num=  ,4949, 4 ,4949, 4 , 3 , 3 , 0 ,,
     1.6     1.6       2       2
      -3      11      11      14
     1.6     1.6       2       2
      -3      11      11      14
Pier Skew, UpSta & Num, DnSta & Num=  ,4972, 4 ,4972, 4 , 3 , 3 , 0 ,,
     1.6     1.6       2       2
      -3      11      11      14
     1.6     1.6       2       2
      -3      11      11      14
Pier Skew, UpSta & Num, DnSta & Num=  ,4995, 4 ,4995, 4 , 3 , 3 , 0 ,,
     1.6     1.6       2       2
      -3      11      11      14
     1.6     1.6       2       2
      -3      11      11      14
Pier Skew, UpSta & Num, DnSta & Num=  ,5018, 4 ,5018, 4 , 3 , 3 , 0 ,,
     1.6     1.6       2       2
      -3      11      11      14
     1.6     1.6       2       2
      -3      11      11      14
Pier Skew, UpSta & Num, DnSta & Num=  ,5041, 4 ,5041, 4 , 3 , 3 , 0 ,,
     1.6     1.6       2       2
      -3      11      11      14
     1.6     1.6       2       2
      -3      11      11      14
BR Coef=-1 , 1 , 1 ,1.25, 0 ,,,.8,-1,2,0,
WSPro=,,,, 1 ,,,, 0 ,,,, 0 ,,,,-1 ,-1 ,-1 , 0 , 0 , 0 , 0 , 0
BC Design=,, 0 ,, 0 ,,,,,,
BC HTab HWMax=22.28

Type RM Length L Ch R = 1 ,2988.153,10.24,60.97,557.33
XS GIS Cut Line= 6
     3170787.717    13827480.765     3170812.949    13827501.191
     3171152.977    13827510.803     3171553.082    13827533.632
     3171679.241    13827544.445     3171766.952    13827561.267
#Sta/Elev= 30
    4807      17    4807   12.82    4836   12.78    4894    12.2 4921.61   12.71
 4955.63     -.4 4958.02   -1.09 4964.17   -2.21 4969.56    -2.6 4975.69   -2.24
 4983.32   -1.08 4996.54     .45 5031.36    6.16    5058   11.56 5156.05      13
 5220.58   14.76 5299.92   15.96 5326.34   17.31  5380.5   19.23 5426.12   20.02
 5457.64    20.2 5494.48   20.95 5566.73   21.49  5589.5    22.1 5641.85    21.1
 5681.96    21.3 5689.69    20.8 5802.48   20.84  5876.4   21.35 5915.13   21.31
#Mann= 3 ,-1 , 0
    4807     .07       0 4921.61    .035       0    5058     .07       0
Bank Sta=4921.61,5058
XS Rating Curve= 0
Exp/Cntr=.5,.3

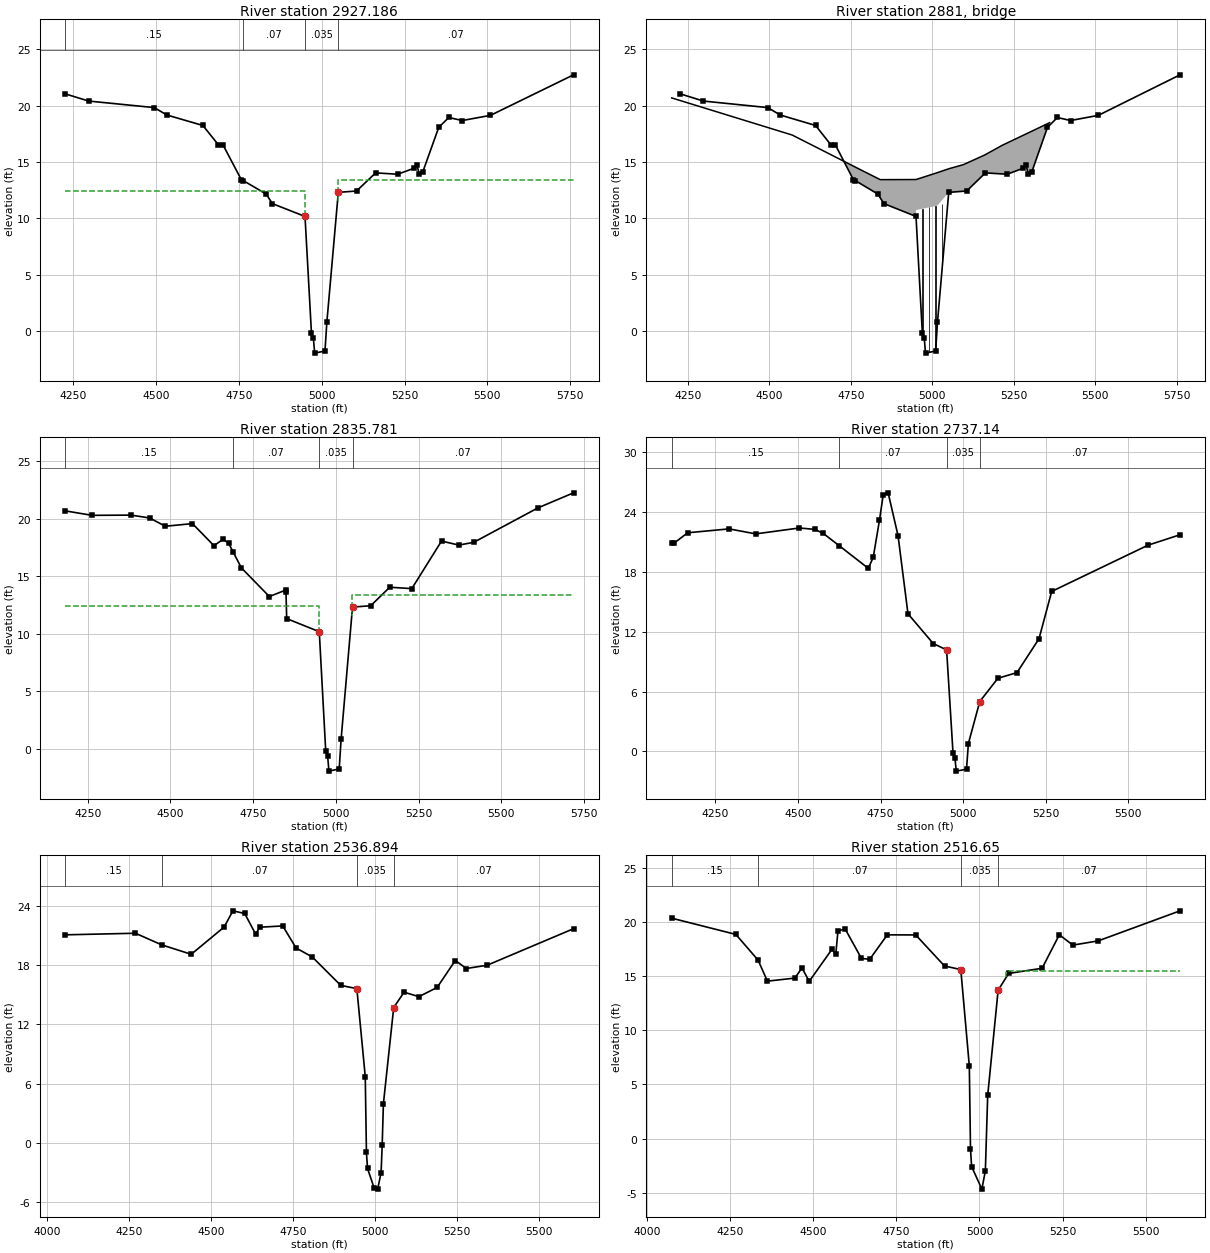
Type RM Length L Ch R = 1 ,2927.186,73.45,91.4,74.14
XS GIS Cut Line= 4
     3170818.148    13826775.631     3170781.206    13827517.559
     3170778.152    13827651.939     3170768.909    13828308.201
#Sta/Elev= 30
 4226.31   21.06 4297.21   20.42  4494.7   19.84 4533.24   19.18 4641.67   18.25
 4688.62   16.53 4702.49   16.52  4757.4   13.45 4763.07   13.36  4832.7   12.16
 4851.28   11.31 4949.79   10.17 4969.21    -.18 4975.11    -.66 4978.95   -1.97
    5010   -1.78 5015.71     .79 5050.21   12.31 5105.24   12.43 5162.79   14.04
 5229.45   13.92 5279.35   14.46 5286.98   14.78 5294.35   13.94 5304.69   14.09
 5353.17   18.08 5383.55   18.96    5424   18.69 5509.33   19.15  5759.9   22.75
#Mann= 4 ,-1 , 0
 4226.31     .15       0 4763.07     .07       0 4949.79    .035       0
 5050.21     .07       0
#XS Ineff= 2 , 0
       0 4949.79    12.4    5048       0    13.4
Permanent Ineff=
       F       F
Bank Sta=4949.79,5050.21
XS Rating Curve= 0
Exp/Cntr=.5,.3

Type RM Length L Ch R = 3 ,2881    ,,,
BEGIN DESCRIPTION:
SHAVER RD
END DESCRIPTION:
Bridge Culvert--1,0,-1,-1, 0
Deck Dist Width WeirC Skew NumUp NumDn MinLoCord MaxHiCord MaxSubmerge Is_Ogee
8,53,2.6,0, 11, 11, , , .95, 0, 0,0,,
    4200    4570    4785    4840    4950    5011    5052    5095    5160    5215
    5360
    20.7    17.4   14.24   13.44   13.45   14.02   14.42   14.77   15.62    16.5
    18.5
                                   10.74    11.1    11.5
        
    4200    4570    4785    4840    4950    5011    5052    5095    5160    5215
    5360
    20.7    17.4   14.24   13.44   13.45   14.02   14.42   14.77   15.62    16.5
    18.5
                                   10.74    11.1    11.5
        
Pier Skew, UpSta & Num, DnSta & Num=  ,4970, 4 ,4970, 4 , 3 , 3 , 0 ,,
     1.2     1.2       2       2
      -3     8.7     8.7      12
     1.2     1.2       2       2
      -3     8.7     8.7      12
Pier Skew, UpSta & Num, DnSta & Num=  ,4990, 4 ,4990, 4 , 3 , 3 , 0 ,,
     1.2     1.2       2       2
      -3     8.7     8.7      12
     1.2     1.2       2       2
      -3     8.7     8.7      12
Pier Skew, UpSta & Num, DnSta & Num=  ,5010, 4 ,5010, 4 , 3 , 3 , 0 ,,
     1.2     1.2       2       2
      -3     8.7     8.7      12
     1.2     1.2       2       2
      -3     8.7     8.7      12
Pier Skew, UpSta & Num, DnSta & Num=  ,5030, 4 ,5030, 4 , 3 , 3 , 0 ,,
     1.2     1.2       2       2
      -3     8.7     8.7      12
     1.2     1.2       2       2
      -3     8.7     8.7      12
BR Coef=-1 , 1 , 0 ,, 0 ,,,.8,-1,2,0,
WSPro=,,,, 1 ,,,, 0 ,,,, 0 ,,,,-1 ,-1 ,-1 , 0 , 0 , 0 , 0 , 0
BC Design=,, 0 ,, 0 ,,,,,,
BC HTab HWMax=22.75

Type RM Length L Ch R = 1 ,2835.781,82.46,98.64,84.73
XS GIS Cut Line= 4
     3170748.235    13826772.149     3170711.246    13827515.023
     3170708.163    13827650.651     3170698.916    13828307.215
#Sta/Elev= 30
 4182.04   20.69 4263.23    20.3    4381   20.32 4437.29   20.07 4484.54   19.35
 4566.49   19.58  4631.5   17.66 4659.52   18.22 4676.04   17.86 4688.95   17.14
 4714.29   15.73 4798.93   13.23 4848.06   13.79 4849.19   13.65 4851.28   11.31
 4949.79   10.17 4969.21    -.18 4975.11    -.66 4978.95   -1.97    5010   -1.78
 5015.71     .79 5050.21   12.31 5105.24   12.43 5162.79   14.04 5229.45   13.92
 5319.22   18.06 5371.57   17.71 5416.58   17.95 5610.65   20.95 5718.13   22.26
#Mann= 4 ,-1 , 0
 4182.04     .15       0 4688.95     .07       0 4949.79    .035       0
 5050.21     .07       0
#XS Ineff= 2 , 0
       0 4949.79    12.4    5048       0    13.4
Permanent Ineff=
       F       F
Bank Sta=4949.79,5050.21
XS Rating Curve= 0
Exp/Cntr=.5,.3

Type RM Length L Ch R = 1 ,2737.14 ,316.06,200.25,90
XS GIS Cut Line= 6
     3169722.317    13827166.357     3170049.612    13827309.851
     3170172.186    13827391.567     3170315.072    13827533.083
     3170478.204    13827789.836     3170619.614    13828308.275
#Sta/Elev= 30
 4117.42   20.87 4124.13   20.84 4165.77   21.89 4291.21   22.28 4372.16   21.78
 4503.82   22.37 4550.77   22.23 4575.81   21.84 4625.27   20.58 4712.69   18.33
  4727.7   19.44  4746.5   23.15 4757.74   25.66 4772.76   25.89  4802.8   21.59
 4832.83   13.78 4909.35    10.8 4949.79   10.17 4969.21    -.18 4975.11    -.66
 4978.95   -1.97    5010   -1.78 5015.71     .79 5050.21       5 5105.24    7.33
 5162.79    7.89 5229.45   11.28 5267.93   16.02 5559.63   20.65 5656.36   21.69
#Mann= 4 ,-1 , 0
 4117.42     .15       0 4625.27     .07       0 4949.79    .035       0
 5050.21     .07       0
Bank Sta=4949.79,5050.21
XS Rating Curve= 0
Exp/Cntr=.3,.1

Type RM Length L Ch R = 1 ,2536.894,31.37,20.24,20
XS GIS Cut Line= 6
     3169722.317    13827166.357     3170049.612    13827309.851
     3170172.186    13827391.567     3170315.072    13827533.083
     3170478.204    13827789.836     3170619.614    13828308.275
#Sta/Elev= 30
 4055.34   21.07 4269.31   21.23 4349.58   20.05 4439.29    19.1  4539.6   21.86
 4566.23    23.5 4602.18   23.23 4635.66   21.13 4647.98   21.84 4718.06   21.97
 4758.66   19.74 4808.25   18.82 4894.83   15.95 4943.84   15.62 4969.46    6.71
 4973.03    -.95 4976.34   -2.59 4996.24   -4.53 5007.23   -4.68 5017.73      -3
 5021.03    -.21 5024.75    3.98 5056.16   13.71 5087.72   15.26  5132.9   14.81
 5188.42   15.74 5243.73   18.47 5277.37   17.66 5340.71   17.99 5603.97   21.69
#Mann= 4 ,-1 , 0
 4055.34     .15       0 4349.58     .07       0 4943.84    .035       0
 5056.16     .07       0
Bank Sta=4943.84,5056.16
XS Rating Curve= 0
Exp/Cntr=.5,.3

Type RM Length L Ch R = 1 ,2516.65 ,162.83,86.1,86.52
XS GIS Cut Line= 6
     3169715.611    13827185.199     3170039.269    13827326.992
     3170159.485    13827407.136     3170299.601     13827545.91
     3170459.769    13827797.966     3170600.277     13828313.38
#Sta/Elev= 30
  4074.1   20.37 4267.14   18.87 4334.06   16.49 4362.04   14.55 4444.58   14.83
 4466.11   15.77 4487.84   14.53 4556.19   17.49 4567.71   17.02 4574.35    19.2
    4596   19.37 4644.99   16.65 4669.85   16.57 4722.85   18.83 4808.25   18.82
 4894.83   15.95 4943.84   15.62 4969.46    6.71 4973.03    -.95 4976.34   -2.59
 5007.23   -4.68 5017.73      -3 5024.75    3.98 5056.16   13.71 5087.72   15.26
 5188.42   15.74 5240.33   18.84 5280.82   17.88 5357.09   18.27 5603.26   21.05
#Mann= 4 ,-1 , 0
  4074.1     .15       0 4334.06     .07       0 4943.84    .035       0
 5056.16     .07       0
#XS Ineff= 2 , 0
       0    4945    14.8    5081       0    15.5
Permanent Ineff=
       F       F
Bank Sta=4943.84,5056.16
XS Rating Curve= 0
Exp/Cntr=.5,.3