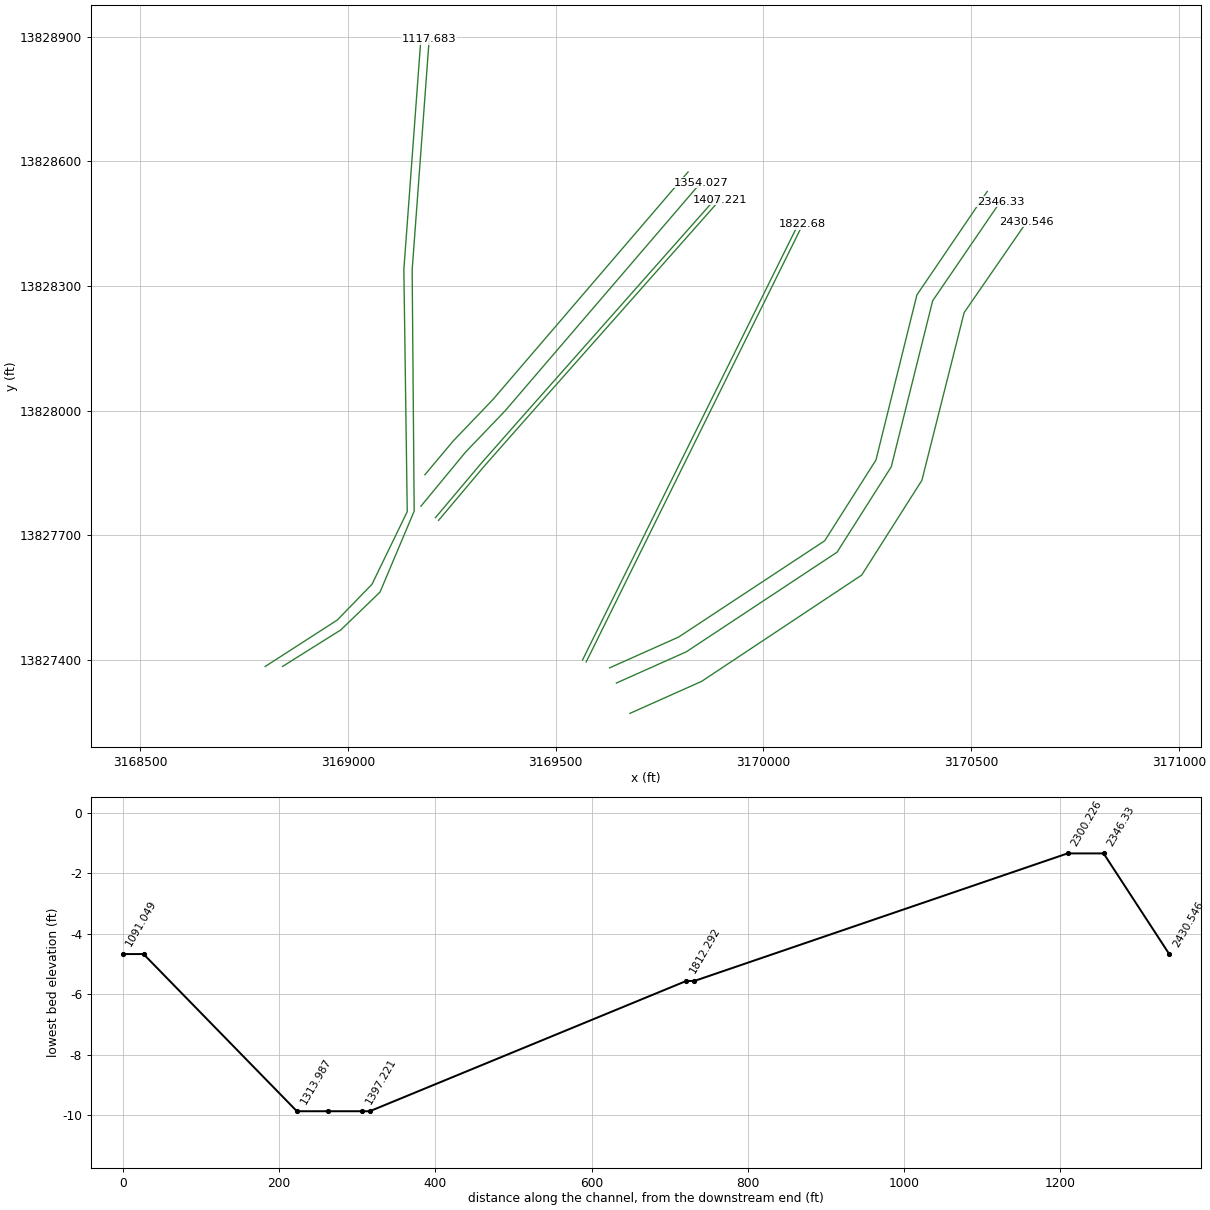
HEC-RAS study I101-00-00.prj: I101-00-00

--- I101-00-00.g03 (geometry) --- (continued)

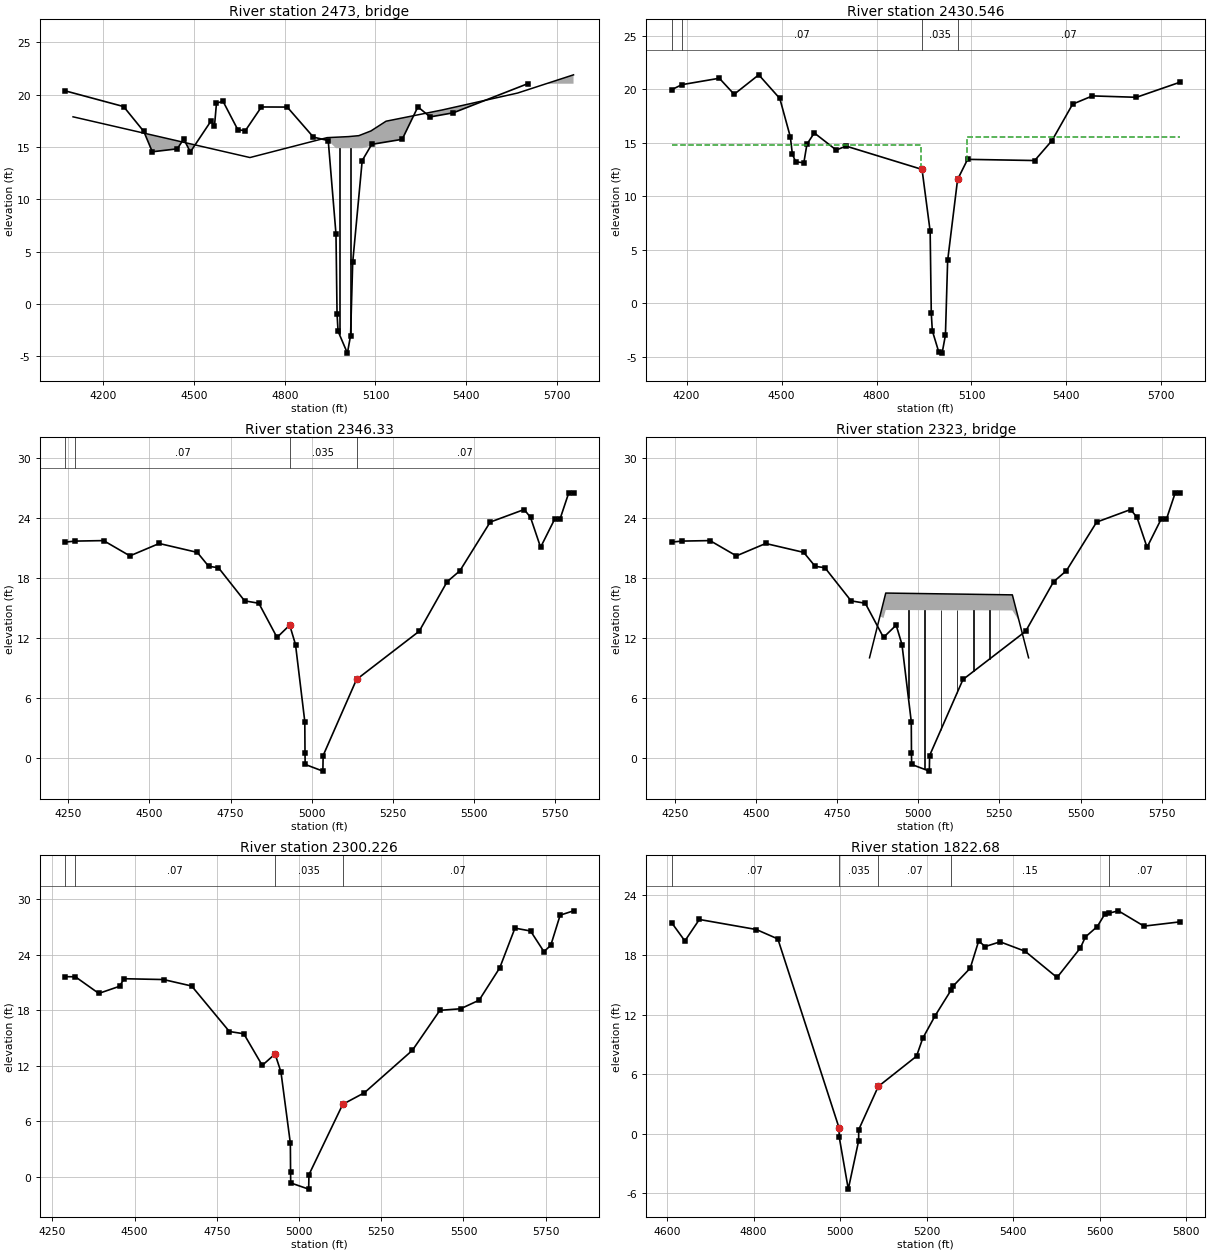
Type RM Length L Ch R = 3 ,2473    ,,,
BEGIN DESCRIPTION:
RICHEY RD
END DESCRIPTION:
Bridge Culvert--1,0,-1,-1, 0
Deck Dist Width WeirC Skew NumUp NumDn MinLoCord MaxHiCord MaxSubmerge Is_Ogee
17,58,2.6,0, 10, 10, , , .95, 0, 0,0,,
    4100    4685    4940    5011    5045    5085    5135    5320    5570    5755
   17.89      14    15.9      16   16.09   16.54   17.47   18.54   20.16    21.9
                   14.89   14.89   14.89   14.89
    4100    4685    4940    5011    5045    5085    5135    5320    5570    5755
   17.89      14    15.9      16   16.09   16.54   17.47   18.54   20.16    21.9
                   14.89   14.89   14.89   14.89
Pier Skew, UpSta & Num, DnSta & Num=  ,4980, 2 ,4980, 2 , 0 , 0 , 0 ,,
       3       3
      -5      15
       3       3
      -5      15
Pier Skew, UpSta & Num, DnSta & Num=  ,5017, 2 ,5017, 2 , 0 , 0 , 0 ,,
       3       3
      -5      15
       3       3
      -5      15
BR Coef=-1 , 1 , 0 ,, 0 ,,,.8,-1,2,0,
WSPro=,,,, 1 ,,,, 0 ,,,, 0 ,,,,-1 ,-1 ,-1 , 0 , 0 , 0 , 0 , 0
BC Design=,, 0 ,, 0 ,,,,,,
BC HTab HWMax=21.09

Type RM Length L Ch R = 1 ,2430.546,160.01,84.22,80
XS GIS Cut Line= 6
     3169678.621    13827271.508     3169851.239     13827348.57
     3170236.547    13827604.414     3170381.422    13827832.516
     3170483.143    13828236.318     3170634.184    13828455.173
#Sta/Elev= 30
 4152.88   19.94    4185   20.41 4303.44   21.01 4350.21   19.51 4427.95   21.33
 4494.48   19.12 4527.83   15.52 4534.22    13.9 4544.92    13.2 4570.38   13.11
 4580.25   14.85  4603.4    15.9  4672.7    14.3 4703.68   14.67 4943.84   12.49
 4969.46    6.71 4973.03    -.95 4976.34   -2.59 4996.24   -4.53 5007.23   -4.68
 5017.73      -3 5024.75    3.98 5056.16   11.55 5087.72   13.43 5299.69   13.32
 5354.47   15.19 5419.59   18.59 5482.19   19.36 5621.13   19.23 5758.79   20.64
#Mann= 4 ,-1 , 0
 4152.88     .15       0    4185     .07       0 4943.84    .035       0
 5056.16     .07       0
#XS Ineff= 2 , 0
       0    4939    14.8    5085       0    15.5
Permanent Ineff=
       F       F
Bank Sta=4943.84,5056.16
XS Rating Curve= 0
Exp/Cntr=.5,.3

Type RM Length L Ch R = 1 ,2346.33 ,73.23,46.1,40
XS GIS Cut Line= 6
     3169646.009    13827344.559     3169814.285    13827419.682
     3170177.201    13827659.477     3170307.684    13827865.034
     3170407.306    13828264.626     3170570.518    13828503.615
#Sta/Elev= 30
 4240.61   21.58 4271.93   21.68  4358.7   21.73 4439.88    20.2 4530.14   21.44
 4647.38   20.55 4682.61   19.15 4712.53   19.02  4793.2    15.7 4836.97   15.46
 4893.09   12.04  4932.1   13.27 4949.98   11.33  4978.6    3.62 4979.25     .46
 4979.75    -.67 5034.27   -1.34 5035.11     .22  5137.9    7.83    5331   12.66
  5416.9   17.61  5456.4   18.71  5549.6   23.58 5654.44   24.84 5673.93   24.05
 5704.89   21.06 5749.09   23.93 5764.58   23.87 5791.67   26.51 5806.38    26.5
#Mann= 4 ,-1 , 0
 4240.61     .15       0 4271.93     .07       0  4932.1    .035       0
  5137.9     .07       0
Bank Sta=4932.1,5137.9
XS Rating Curve= 0
Exp/Cntr=.5,.3

Type RM Length L Ch R = 3 ,2323    ,,,
BEGIN DESCRIPTION:
PIPE CROSSING
END DESCRIPTION:
Bridge Culvert--1,0,-1,-1, 0
Deck Dist Width WeirC Skew NumUp NumDn MinLoCord MaxHiCord MaxSubmerge Is_Ogee
5,23,2.6,0, 4, 4, , , .95, 0, 0,0,,
    4850    4900    5290    5340
      10   16.48    16.3      10
       9   14.78   14.74       9
    4850    4900    5290    5340
      10   16.48    16.3      10
       9   14.78   14.74       9
Pier Skew, UpSta & Num, DnSta & Num=  ,4970, 4 ,4970, 4 , 3 , 3 , 0 ,,
     1.2     1.2       2       2
      -2   12.74   12.74      15
     1.2     1.2       2       2
      -2   12.74   12.74      15
Pier Skew, UpSta & Num, DnSta & Num=  ,5020, 4 ,5020, 4 , 3 , 3 , 0 ,,
     1.2     1.2       2       2
      -2   12.74   12.74      15
     1.2     1.2       2       2
      -2   12.74   12.74      15
Pier Skew, UpSta & Num, DnSta & Num=  ,5070, 4 ,5070, 4 , 3 , 3 , 0 ,,
     1.2     1.2       2       2
      -2   12.74   12.74      15
     1.2     1.2       2       2
      -2   12.74   12.74      15
Pier Skew, UpSta & Num, DnSta & Num=  ,5120, 4 ,5120, 4 , 3 , 3 , 0 ,,
     1.2     1.2       2       2
      -2   12.74   12.74      15
     1.2     1.2       2       2
      -2   12.74   12.74      15
Pier Skew, UpSta & Num, DnSta & Num=  ,5170, 4 ,5170, 4 , 3 , 3 , 0 ,,
     1.2     1.2       2       2
      -2   12.74   12.74      15
     1.2     1.2       2       2
      -2   12.74   12.74      15
Pier Skew, UpSta & Num, DnSta & Num=  ,5220, 4 ,5220, 4 , 3 , 3 , 0 ,,
     1.2     1.2       2       2
      -2   12.74   12.74      15
     1.2     1.2       2       2
      -2   12.74   12.74      15
BR Coef=-1 , 1 , 1 ,1.25, 0 ,,,.8,-1,2,0,
WSPro=,,,, 1 ,,,, 0 ,,,, 0 ,,,,-1 ,-1 ,-1 , 0 , 0 , 0 , 0 , 0
BC Design=,, 0 ,, 0 ,,,,,,
BC HTab HWMax=26.51

Type RM Length L Ch R = 1 ,2300.226,249.23,477.55,428.61
XS GIS Cut Line= 6
     3169629.703    13827381.085     3169795.807    13827455.238
     3170147.529    13827687.008     3170270.814    13827881.293
     3170369.387     13828278.78     3170538.685    13828527.836
#Sta/Elev= 30
 4288.98   21.63 4319.89   21.62 4391.07   19.82  4454.1   20.59 4468.24   21.41
 4587.96   21.32 4673.52   20.62  4788.2    15.7 4831.97   15.46 4888.09   12.04
  4927.1   13.27 4944.98   11.33  4973.6    3.62 4974.25     .46 4974.75    -.67
 5029.27   -1.34 5030.11     .22  5132.9    7.83  5198.7    9.08 5344.68   13.67
 5428.27   17.99  5491.2   18.16 5547.65   19.09 5610.23   22.58 5656.55   26.88
 5703.95   26.57 5744.56   24.34 5765.39   25.01 5793.96   28.28 5834.67   28.75
#Mann= 4 ,-1 , 0
 4288.98     .15       0 4319.89     .07       0  4927.1    .035       0
  5132.9     .07       0
Bank Sta=4927.1,5132.9
XS Rating Curve= 0
Exp/Cntr=.5,.3

Type RM Length L Ch R = 1 ,1822.68 ,10.37,10.39,10.8
XS GIS Cut Line= 2
     3169573.365    13827395.361     3170094.661    13828448.587
#Sta/Elev= 30
 4610.43   21.25 4640.93   19.42 4674.41   21.58 4806.09   20.57 4855.92   19.62
 4997.12     .64  4997.9    -.35 5018.75   -5.56 5042.64     -.7 5042.86     .42
    5088    4.77 5176.51    7.82 5190.83    9.62  5219.6    11.9 5256.78    14.5
 5261.89   14.91 5300.62   16.68 5320.23   19.42 5335.03   18.85 5369.69   19.33
 5427.56   18.38 5501.35   15.74 5555.35   18.72 5566.93   19.82 5594.38   20.87
 5611.67   22.11 5621.08   22.21 5643.09   22.45 5702.25   20.91  5785.6   21.34
#Mann= 5 ,-1 , 0
 4610.43     .07       0 4997.12    .035       0    5088     .07       0
 5256.78     .15       0 5621.08     .07       0
Bank Sta=4997.12,5088
XS Rating Curve= 0
Exp/Cntr=.5,.3

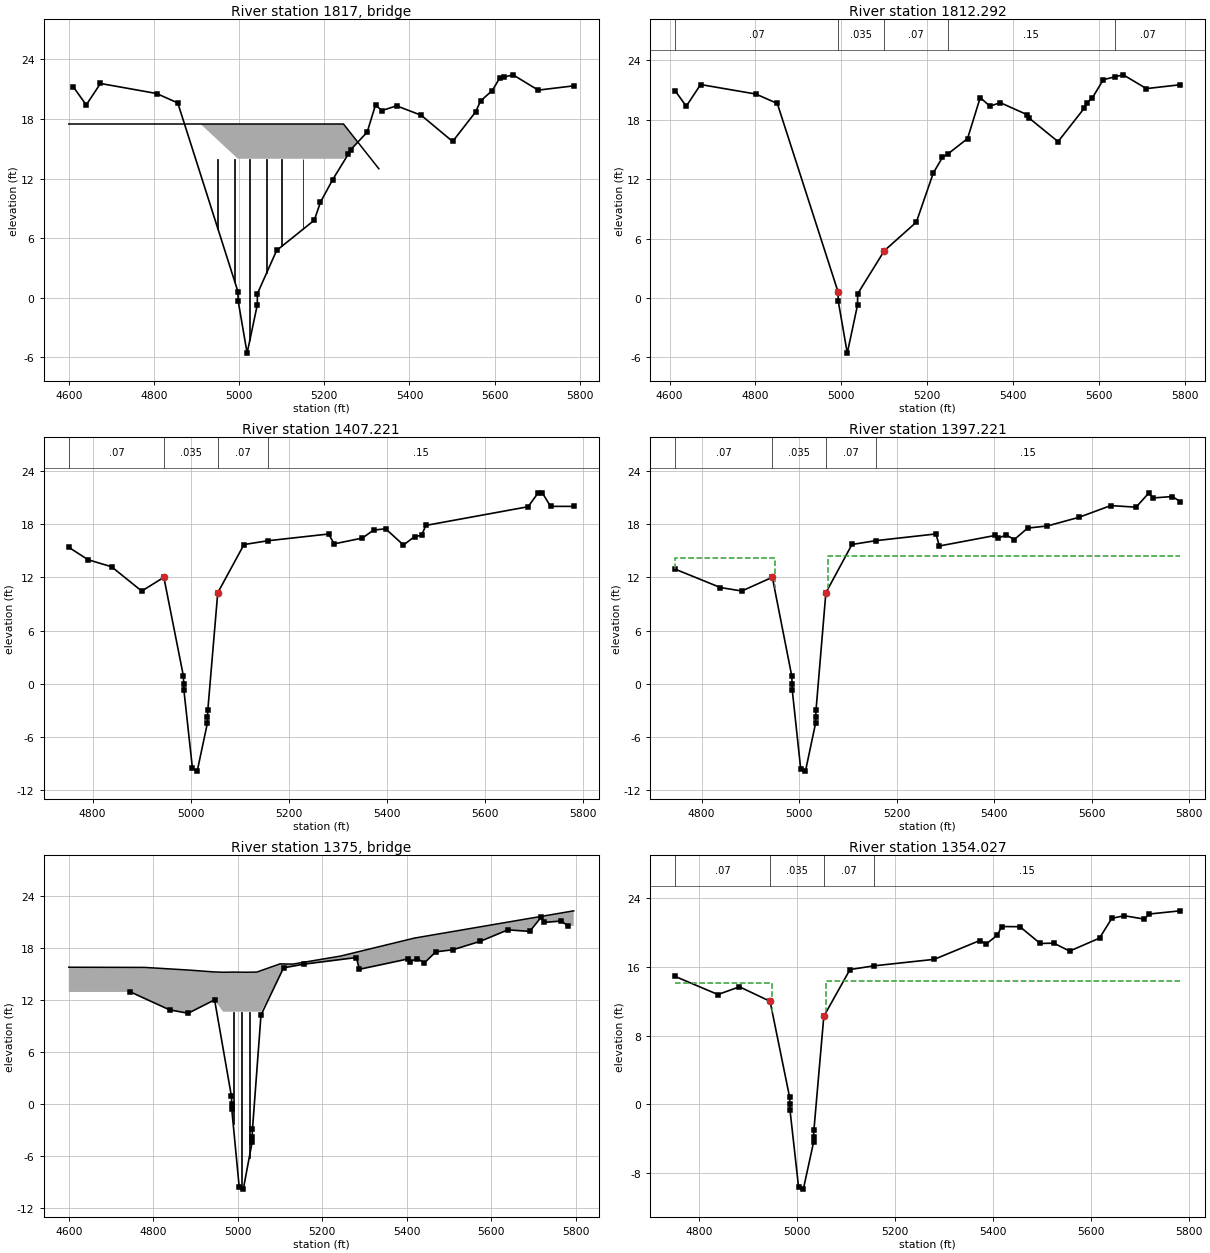
Type RM Length L Ch R = 3 ,1817    ,,,
BEGIN DESCRIPTION:
PIPE CROSSING
END DESCRIPTION:
Bridge Culvert--1,0,-1,-1, 0
Deck Dist Width WeirC Skew NumUp NumDn MinLoCord MaxHiCord MaxSubmerge Is_Ogee
3,3,2.6,0, 3, 3, , , .95, 0, 0,0,,
    4600    5245    5328
    17.5    17.5      13
      14      14      12
    4600    5245    5328
    17.5    17.5      13
      14      14      12
Pier Skew, UpSta & Num, DnSta & Num=  ,4950, 4 ,4950, 4 , 3 , 3 , 0 ,,
     1.2     1.2       2       2
      -6      12      12      16
     1.2     1.2       2       2
      -6      12      12      16
Pier Skew, UpSta & Num, DnSta & Num=  ,4990, 4 ,4990, 4 , 3 , 3 , 0 ,,
     1.2     1.2       2       2
      -6      12      12      16
     1.2     1.2       2       2
      -6      12      12      16
Pier Skew, UpSta & Num, DnSta & Num=  ,5025, 4 ,5025, 4 , 3 , 3 , 0 ,,
     1.2     1.2       2       2
      -6      12      12      16
     1.2     1.2       2       2
      -6      12      12      16
Pier Skew, UpSta & Num, DnSta & Num=  ,5065, 4 ,5065, 4 , 3 , 3 , 0 ,,
     1.2     1.2       2       2
      -6      12      12      16
     1.2     1.2       2       2
      -6      12      12      16
Pier Skew, UpSta & Num, DnSta & Num=  ,5100, 4 ,5100, 4 , 3 , 3 , 0 ,,
     1.2     1.2       2       2
      -6      12      12      16
     1.2     1.2       2       2
      -6      12      12      16
Pier Skew, UpSta & Num, DnSta & Num=  ,5150, 4 ,5150, 4 , 3 , 3 , 0 ,,
     1.2     1.2       2       2
      -6      12      12      16
     1.2     1.2       2       2
      -6      12      12      16
BR Coef=-1 , 1 , 1 ,1.25, 0 ,,,.8,-1,2,0,
WSPro=,,,, 1 ,,,, 0 ,,,, 0 ,,,,-1 ,-1 ,-1 , 0 , 0 , 0 , 0 , 0
BC Design=,, 0 ,, 0 ,,,,,,
BC HTab HWMax=22.45

Type RM Length L Ch R = 1 ,1812.292,464.21,405.07,322.72
XS GIS Cut Line= 2
     3169564.402    13827399.797     3170085.699    13828453.023
#Sta/Elev= 30
 4613.37   20.89 4638.92   19.34  4672.4   21.53 4801.09   20.57 4850.92   19.62
 4992.12     .64  4992.9    -.35 5013.75   -5.56 5037.64     -.7 5037.86     .42
    5100    4.77  5174.5    7.65 5213.98   12.61 5235.23   14.18 5247.96   14.53
 5293.65   16.08 5323.21   20.22 5345.54   19.35 5369.95    19.7 5432.36   18.49
 5435.54    18.2 5504.33   15.77 5565.02   19.13 5570.68   19.66  5584.1   20.18
 5609.66   22.02 5635.77    22.3 5656.11   22.51 5710.02   21.12 5788.54   21.51
#Mann= 5 ,-1 , 0
 4613.37     .07       0 4992.12    .035       0    5100     .07       0
 5247.96     .15       0 5635.77     .07       0
Bank Sta=4992.12,5100
XS Rating Curve= 0
Exp/Cntr=.5,.3

Type RM Length L Ch R = 1 ,1407.221,10.35,10,10.07
XS GIS Cut Line= 4
     3169217.982    13827736.017     3169325.724    13827863.961
     3169415.937    13827966.292     3169895.707    13828508.056
#Sta/Elev= 30
 4751.37    15.4 4790.58      14 4838.61    13.2    4900   10.46  4945.1   12.01
 4984.91     .87 4985.66       0 4985.82    -.66 5003.25    -9.5 5013.06   -9.87
 5034.01    -4.4 5034.03   -3.79 5034.75   -2.94  5054.9   10.26 5108.35   15.71
 5157.11   16.14 5280.68    16.9 5292.25   15.79  5349.5   16.44  5372.4   17.34
 5397.01   17.49 5433.31   15.66 5456.16   16.61 5470.44   16.75 5478.79   17.87
 5687.26   19.98 5707.52   21.52 5716.35   21.55 5733.05   20.02 5780.28   20.02
#Mann= 4 ,-1 , 0
 4751.37     .07       0  4945.1    .035       0  5054.9     .07       0
 5157.11     .15       0
Bank Sta=4945.1,5054.9
XS Rating Curve= 0
Exp/Cntr=.5,.3

Type RM Length L Ch R = 1 ,1397.221,46.81,43.19,45.03
XS GIS Cut Line= 4
     3169210.333    13827742.458     3169318.148    13827870.489
     3169408.443    13827972.914     3169888.221    13828514.685
#Sta/Elev= 30
    4746   12.92 4838.61   10.85 4882.55   10.46  4945.1   12.01 4984.91     .87
 4985.66       0 4985.82    -.66 5003.25    -9.6 5013.06   -9.87 5034.01    -4.4
 5034.03   -3.79 5034.75   -2.94  5054.9   10.26 5108.35   15.71 5157.11   16.14
 5280.68    16.9 5287.66   15.54 5402.24   16.73 5408.03   16.42 5424.86   16.78
 5441.38   16.27 5468.66   17.56 5509.19    17.8 5574.14   18.78 5639.17    20.1
 5691.04   19.92 5717.54   21.54  5725.4   20.96 5765.48   21.12 5781.49   20.56
#Mann= 4 ,-1 , 0
    4746     .07       0  4945.1    .035       0  5054.9     .07       0
 5157.11     .15       0
#XS Ineff= 2 , 0
       0    4950    14.2    5059       0    14.4
Permanent Ineff=
       F       F
Bank Sta=4945.1,5054.9
XS Rating Curve= 0
Exp/Cntr=.5,.3

Type RM Length L Ch R = 3 ,1375    ,,,
BEGIN DESCRIPTION:
UNNAMED ROAD
END DESCRIPTION:
Bridge Culvert--1,0,-1,-1, 0
Deck Dist Width WeirC Skew NumUp NumDn MinLoCord MaxHiCord MaxSubmerge Is_Ogee
8,25,2.6,0, 13, 13, , , .95, 0, 0,0,,
    4600    4780    4885    4940    4965    4990    5020    5045    5100    5130
    5243    5418    5795
   15.78   15.76   15.45   15.25    15.2   15.22    15.2   15.22   16.17   16.14
   17.07   19.15    22.3
                           10.64   10.64   10.64   10.64   10.64   10.64
                        
    4600    4780    4885    4940    4965    4990    5020    5045    5100    5130
    5243    5418    5795
   15.78   15.76   15.45   15.25    15.2   15.22    15.2   15.22   16.17   16.14
   17.07   19.15    22.3
                           10.64   10.64   10.64   10.64   10.64   10.64
                        
Pier Skew, UpSta & Num, DnSta & Num=  ,4989, 4 ,4989, 4 , 3 , 3 , 0 ,,
     1.5     1.5       2       2
     -10    8.64    8.64      12
     1.5     1.5       2       2
     -10    8.64    8.64      12
Pier Skew, UpSta & Num, DnSta & Num=  ,5008, 4 ,5008, 4 , 3 , 3 , 0 ,,
     1.5     1.5       2       2
     -10    8.64    8.64      12
     1.5     1.5       2       2
     -10    8.64    8.64      12
Pier Skew, UpSta & Num, DnSta & Num=  ,5027, 4 ,5027, 4 , 3 , 3 , 0 ,,
     1.5     1.5       2       2
     -10    8.64    8.64      12
     1.5     1.5       2       2
     -10    8.64    8.64      12
BR Coef=-1 , 1 , 0 ,, 0 ,,,.8,-1,2,0,
WSPro=,,,, 1 ,,,, 0 ,,,, 0 ,,,,-1 ,-1 ,-1 , 0 , 0 , 0 , 0 , 0
BC Design=,, 0 ,, 0 ,,,,,,
BC HTab HWMax=21.54

Type RM Length L Ch R = 1 ,1354.027,42.17,40.04,40.2
XS GIS Cut Line= 4
     3169175.536    13827770.194     3169282.974    13827900.359
     3169378.015    13827999.532     3169848.939     13828548.67
#Sta/Elev= 30
 4751.37    14.9 4838.61    12.8 4882.55    13.7  4945.1   12.01 4984.91     .87
 4985.66       0 4985.82    -.66 5003.25    -9.6 5013.06   -9.87 5034.01    -4.4
 5034.03   -3.79 5034.75   -2.94  5054.9   10.26 5108.35   15.71 5157.11   16.14
 5280.68    16.9 5373.52   19.09 5386.49   18.68 5409.52   19.72  5418.4   20.72
 5455.61    20.7 5496.98   18.75 5524.82   18.78 5557.22   17.86 5618.17   19.37
 5643.38   21.68 5668.95   21.98 5709.14   21.59  5720.2   22.18 5782.98   22.55
#Mann= 4 ,-1 , 0
 4751.37     .07       0  4945.1    .035       0  5054.9     .07       0
 5157.11     .15       0
#XS Ineff= 2 , 0
       0    4950    14.2    5059       0    14.4
Permanent Ineff=
       F       F
Bank Sta=4945.1,5054.9
XS Rating Curve= 0
Exp/Cntr=.5,.3

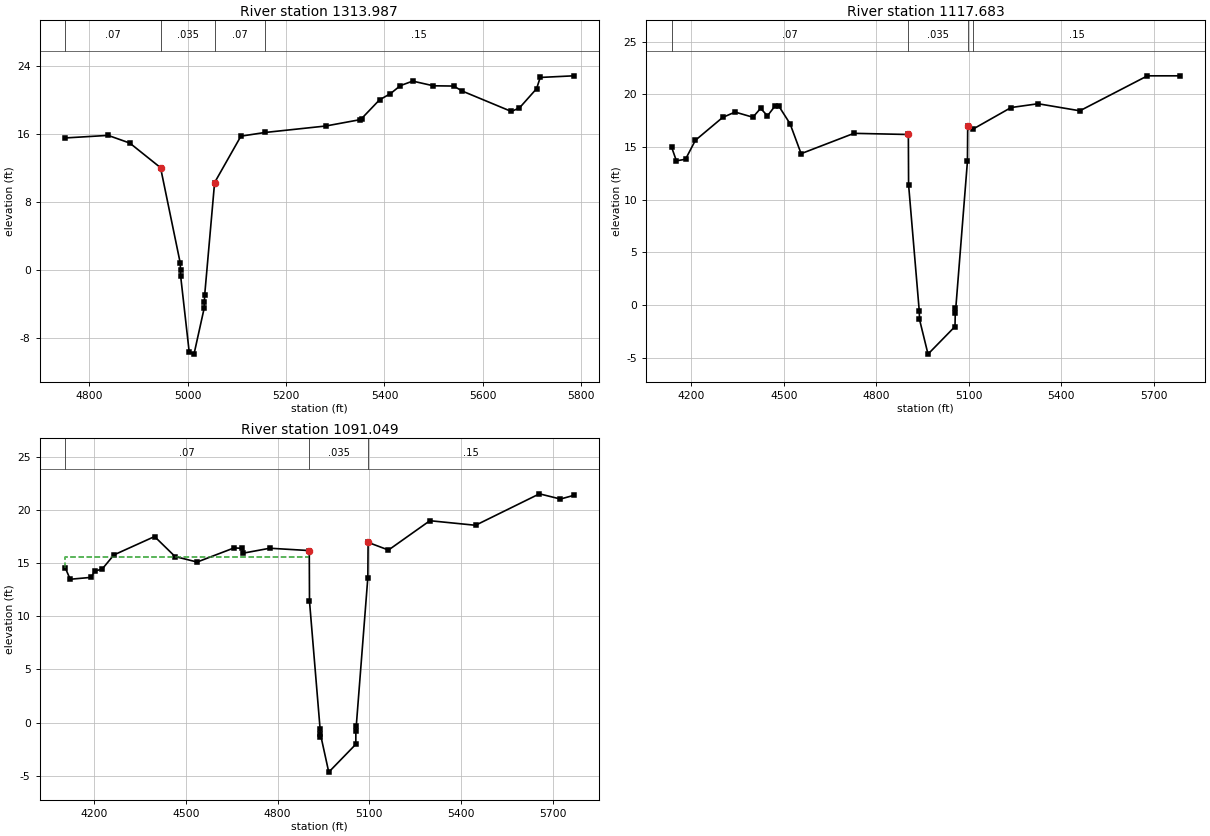
Type RM Length L Ch R = 1 ,1313.987,47.7,196.3,415.11
XS GIS Cut Line= 4
     3169185.155    13827846.002     3169253.069    13827926.964
     3169348.371     13828026.41     3169818.575    13828574.709
#Sta/Elev= 30
 4751.37    15.5 4838.61    15.8 4882.55    14.9  4945.1   12.01 4984.91     .87
 4985.66       0 4985.82    -.66 5003.25    -9.6 5013.06   -9.87 5034.01    -4.4
 5034.03   -3.79 5034.75   -2.94  5054.9   10.26 5108.35   15.71 5157.11   16.14
 5280.68    16.9 5350.01   17.64 5353.38   17.76 5389.95   19.97 5412.24    20.7
 5432.42   21.64 5457.35   22.17 5499.43   21.62 5540.79   21.59 5557.34   21.02
 5657.76   18.61 5674.24   19.02 5709.07   21.28 5716.51    22.6 5784.17   22.79
#Mann= 4 ,-1 , 0
 4751.37     .07       0  4945.1    .035       0  5054.9     .07       0
 5157.11     .15       0
Bank Sta=4945.1,5054.9
XS Rating Curve= 0
Exp/Cntr=.3,.1

Type RM Length L Ch R = 1 ,1117.683,22.08,26.63,21.87
XS GIS Cut Line= 6
     3168842.572     13827384.56     3168982.611    13827472.295
     3169077.095    13827563.404     3169159.332    13827758.405
     3169154.457    13828339.041     3169195.472    13828894.899
#Sta/Elev= 30
  4136.4   14.96 4151.73   13.68 4181.27   13.83 4213.31   15.63 4301.65    17.8
 4342.08   18.31 4399.69   17.82 4424.69   18.66 4446.97   17.95 4472.35   18.92
 4483.67   18.88 4520.27    17.2 4556.05   14.36 4727.29   16.29 4903.78   16.18
 4904.53   11.41 4939.22    -.61 4939.88   -1.37 4967.52   -4.67    5055   -2.05
 5056.23    -.31 5056.26    -.79 5095.35   13.64 5096.22   16.95 5112.66   16.68
  5236.9   18.74 5324.37    19.1 5459.78   18.43  5678.9   21.75 5784.51   21.75
#Mann= 4 ,-1 , 0
  4136.4     .07       0 4903.78    .035       0 5096.22     .07       0
 5112.66     .15       0
Bank Sta=4903.78,5096.22
XS Rating Curve= 0
Exp/Cntr=.5,.3

Type RM Length L Ch R = 1 ,1091.049,53.88,51.33,43.74
XS GIS Cut Line= 6
     3168800.687    13827384.335     3168974.225     13827496.17
      3169057.78    13827582.296     3169142.621    13827757.119
     3169134.461    13828339.825     3169175.526    13828896.371
#Sta/Elev= 30
 4105.43   14.57 4121.69   13.48 4190.88   13.66 4201.32   14.25 4226.04   14.43
 4264.67   15.77 4397.72    17.5 4464.73   15.62 4536.91    15.1 4657.75   16.43
 4684.95   16.39 4686.53   15.93 4774.76    16.4 4903.78   16.18 4904.53   11.41
 4939.22    -.61 4939.88   -1.37 4940.08   -1.06 4967.52   -4.67    5056   -2.05
 5056.23    -.31 5056.26    -.79 5095.35   13.64 5096.22   16.95 5162.89   16.23
 5298.31   18.99 5447.64   18.56 5656.71   21.52 5725.46   21.03 5768.21   21.37
#Mann= 3 ,-1 , 0
 4105.43     .07       0 4903.78    .035       0 5096.22     .15       0
#XS Ineff= 2 , 0
       0 4903.78    15.6 5096.22       0      16
Permanent Ineff=
       F       F
Bank Sta=4903.78,5096.22
XS Rating Curve= 0
Exp/Cntr=.5,.3