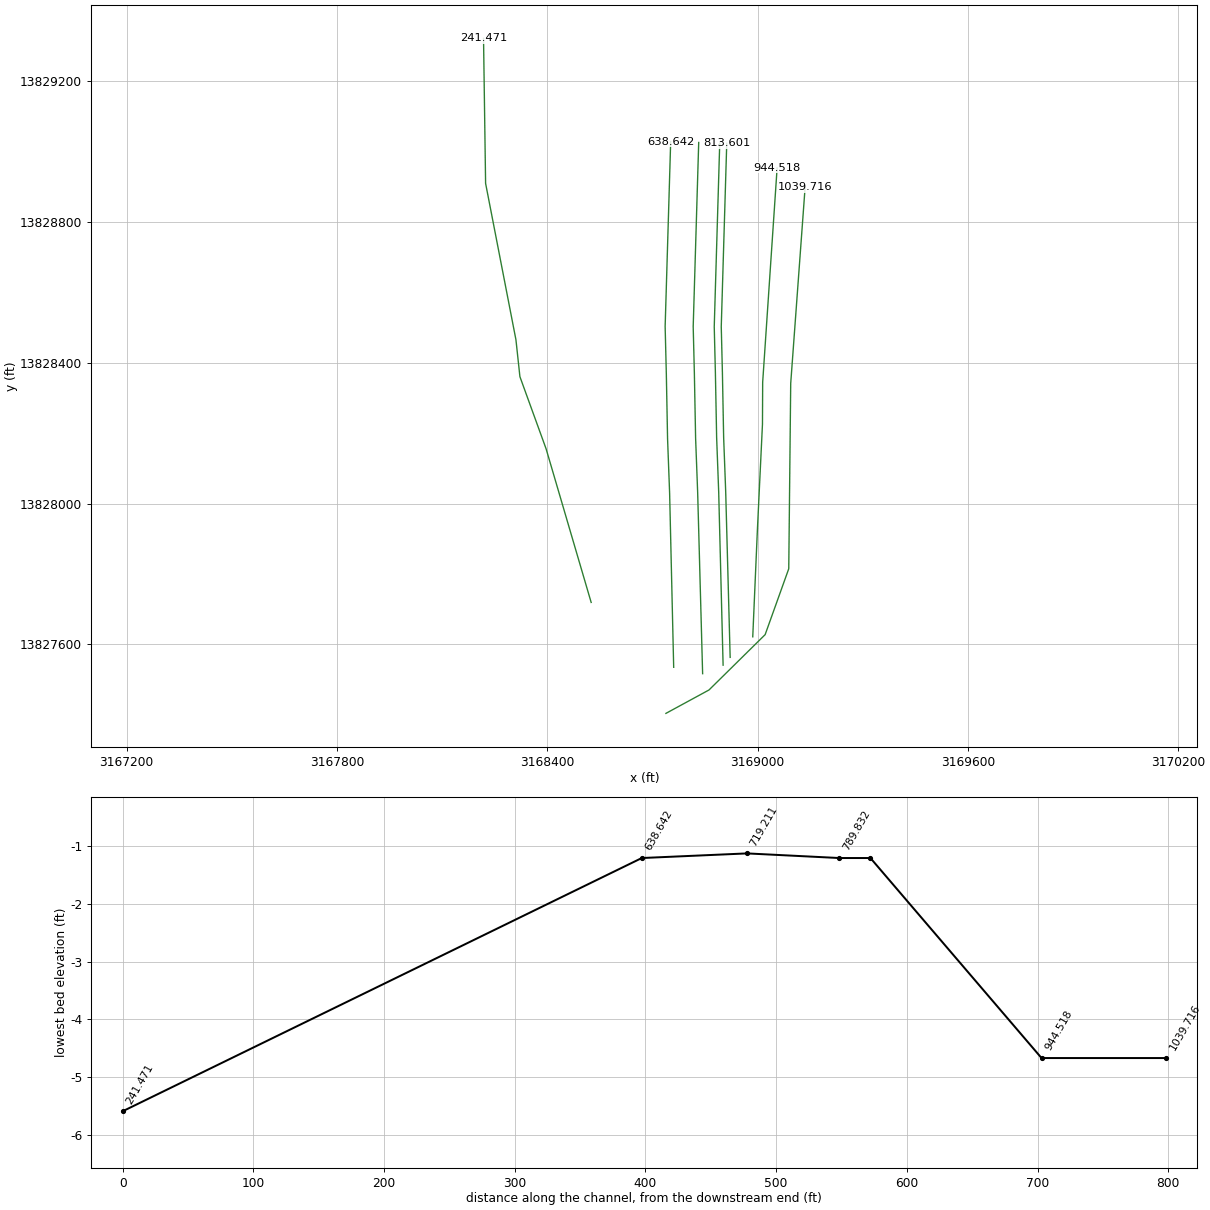
HEC-RAS study I101-00-00.prj: I101-00-00

--- I101-00-00.g03 (geometry) --- (continued)

Type RM Length L Ch R = 3 ,1065    ,,,
BEGIN DESCRIPTION:
RR BRIDGE
END DESCRIPTION:
Bridge Culvert--1,0,-1,-1, 0
Deck Dist Width WeirC Skew NumUp NumDn MinLoCord MaxHiCord MaxSubmerge Is_Ogee
8,25,2.6,0, 13, 13, , , .95, 0, 0,0,,
    4000    4400    4600    4900    4915    4930    4985    5040    5080    5100
    5360    5585    5770
   16.06   16.98   17.15   16.51   17.09   17.07   17.12   17.14   17.01   17.07
   18.64   20.62   21.32
                            14.5    14.5    14.5    14.5    14.5    14.5    14.5
                        
    4000    4400    4600    4900    4915    4930    4985    5040    5080    5100
    5360    5585    5770
   16.06   16.98   17.15   16.51   17.09   17.07   17.12   17.14   17.01   17.07
   18.64   20.62   21.32
                            14.5    14.5    14.5    14.5    14.5    14.5    14.5
                        
Pier Skew, UpSta & Num, DnSta & Num=  ,4915, 2 ,4915, 2 , 0 , 0 , 0 ,,
       1       1
      -5      15
       1       1
      -5      15
Pier Skew, UpSta & Num, DnSta & Num=  ,4930, 2 ,4930, 2 , 0 , 0 , 0 ,,
       1       1
      -5      15
       1       1
      -5      15
Pier Skew, UpSta & Num, DnSta & Num=  ,4945, 2 ,4945, 2 , 0 , 0 , 0 ,,
       1       1
      -5      15
       1       1
      -5      15
Pier Skew, UpSta & Num, DnSta & Num=  ,4960, 2 ,4960, 2 , 0 , 0 , 0 ,,
       1       1
      -5      15
       1       1
      -5      15
Pier Skew, UpSta & Num, DnSta & Num=  ,4975, 2 ,4975, 2 , 0 , 0 , 0 ,,
       1       1
      -5      15
       1       1
      -5      15
Pier Skew, UpSta & Num, DnSta & Num=  ,4990, 2 ,4990, 2 , 0 , 0 , 0 ,,
       1       1
      -5      15
       1       1
      -5      15
Pier Skew, UpSta & Num, DnSta & Num=  ,5005, 2 ,5005, 2 , 0 , 0 , 0 ,,
       1       1
      -5      15
       1       1
      -5      15
Pier Skew, UpSta & Num, DnSta & Num=  ,5020, 2 ,5020, 2 , 0 , 0 , 0 ,,
       1       1
      -5      15
       1       1
      -5      15
Pier Skew, UpSta & Num, DnSta & Num=  ,5035, 2 ,5035, 2 , 0 , 0 , 0 ,,
       1       1
      -5      15
       1       1
      -5      15
Pier Skew, UpSta & Num, DnSta & Num=  ,5050, 2 ,5050, 2 , 0 , 0 , 0 ,,
       1       1
      -5      15
       1       1
      -5      15
Pier Skew, UpSta & Num, DnSta & Num=  ,5063, 2 ,5063, 2 , 0 , 0 , 0 ,,
       1       1
      -5      15
       1       1
      -5      15
Pier Skew, UpSta & Num, DnSta & Num=  ,5072, 2 ,5072, 2 , 0 , 0 , 0 ,,
       1       1
      -5      15
       1       1
      -5      15
Pier Skew, UpSta & Num, DnSta & Num=  ,5085, 2 ,5085, 2 , 0 , 0 , 0 ,,
       1       1
      -5      15
       1       1
      -5      15
BR Coef=-1 , 1 , 1 ,1.25, 0 ,,,.8,-1,2,0,
WSPro=,,,, 1 ,,,, 0 ,,,, 0 ,,,,-1 ,-1 ,-1 , 0 , 0 , 0 , 0 , 0
BC Design=,, 0 ,, 0 ,,,,,,
BC HTab HWMax=21.65

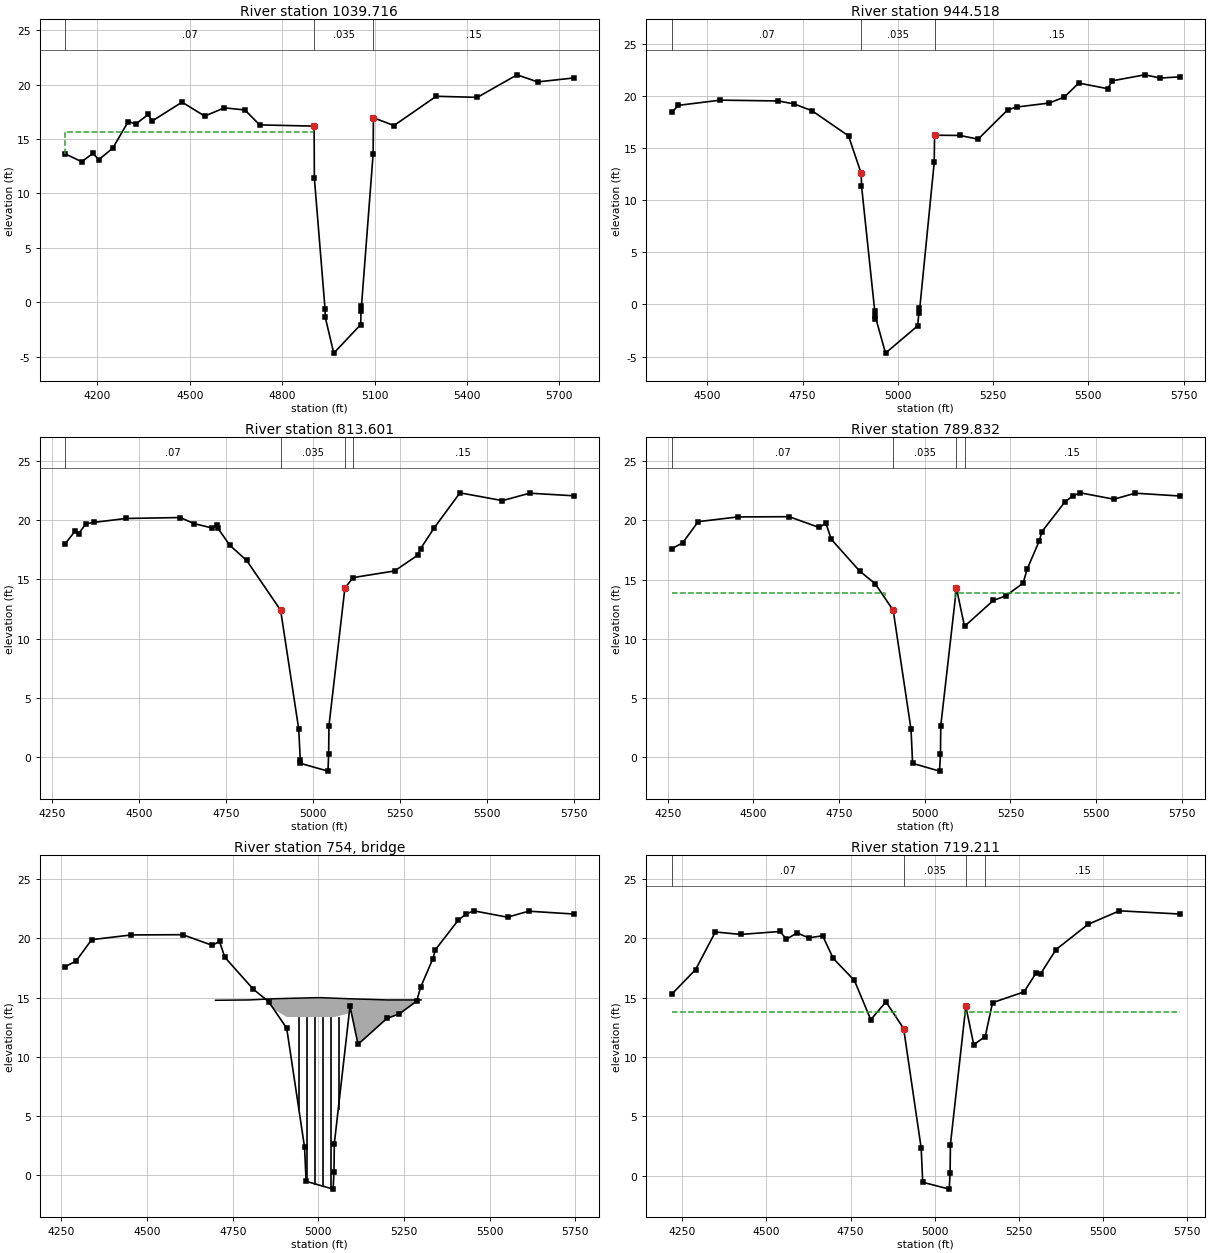
Type RM Length L Ch R = 1 ,1039.716,96.07,95.2,88.55
XS GIS Cut Line= 6
     3168738.501    13827404.128     3168861.343    13827470.584
     3169021.549    13827627.815     3169088.903    13827814.945
     3169094.468    13828341.393     3169135.635    13828899.314
#Sta/Elev= 30
 4095.85   13.63 4149.31   12.91 4185.93   13.68 4204.78    13.1 4250.34   14.16
 4300.42    16.6 4324.66   16.37 4366.02   17.26 4377.07   16.63 4475.07   18.38
 4548.72    17.1 4612.61   17.86 4679.03   17.66 4727.29   16.29 4903.78   16.18
 4904.53   11.41 4939.22    -.61 4939.88   -1.37 4967.52   -4.67    5055   -2.05
 5056.23    -.31 5056.26    -.79 5095.35   13.64 5096.22   16.95 5162.89   16.23
 5300.09   18.92 5433.51   18.82 5562.44   20.89 5629.26   20.24 5745.78    20.6
#Mann= 3 ,-1 , 0
 4095.85     .07       0 4903.78    .035       0 5096.22     .15       0
#XS Ineff= 2 , 0
       0 4903.78    15.6 5096.22       0      16
Permanent Ineff=
       F       F
Bank Sta=4903.78,5096.22
XS Rating Curve= 0
Exp/Cntr=.5,.3

Type RM Length L Ch R = 1 ,944.518 ,93.18,130.92,137.35
XS GIS Cut Line= 5
     3168986.199    13827621.619      3168999.48    13827926.255
      3169013.92    13828225.776     3169014.482     13828344.53
     3169055.714    13828953.473
#Sta/Elev= 30
 4406.42   18.44 4424.05   19.12 4534.32   19.62 4686.53   19.54 4727.29   19.26
 4774.76    18.6 4870.43   16.19 4903.78   12.58 4904.53   11.41 4939.22    -.61
 4939.88   -1.37 4940.08   -1.06 4967.52   -4.67    5052   -2.05 5056.23    -.31
 5056.26    -.79 5095.35   13.64 5096.22   16.25 5162.89   16.23 5210.42   15.87
  5288.5    18.7 5312.58   18.96 5396.84   19.34  5437.1   19.92 5474.57   21.26
 5550.27   20.72 5563.09   21.48 5647.92   22.05  5688.9   21.74 5740.31   21.86
#Mann= 3 ,-1 , 0
 4406.42     .07       0 4903.78    .035       0 5096.22     .15       0
Bank Sta=4903.78,5096.22
XS Rating Curve= 0
Exp/Cntr=.3,.1

Type RM Length L Ch R = 1 ,813.601 ,21.01,23.77,20.28
XS GIS Cut Line= 6
     3168921.757    13827563.219     3168909.011    13828034.027
     3168903.176    13828187.594     3168899.628    13828372.098
     3168896.351    13828502.365     3168912.002    13829023.313
#Sta/Elev= 30
 4288.65   18.03 4316.23   19.06 4327.24   18.88 4347.98   19.71 4371.21   19.83
 4463.44   20.16 4619.24   20.24 4658.27   19.73 4710.42   19.36 4725.67    19.6
 4726.97   19.35 4761.51    17.9 4810.05   16.61 4907.67    12.4 4959.75    2.33
 4964.15    -.27 4964.29    -.55  5043.7   -1.21 5045.66     .23 5046.54    2.63
 5092.33   14.27  5115.8   15.16 5234.92   15.72  5302.4   17.07 5309.61    17.6
 5348.54   19.35 5423.03   22.33 5545.14   21.67 5623.14    22.3 5749.34   22.08
#Mann= 4 ,-1 , 0
 4288.65     .07       0 4907.67    .035       0 5092.33     .07       0
  5115.8     .15       0
Bank Sta=4907.67,5092.33
XS Rating Curve= 0
Exp/Cntr=.5,.3

Type RM Length L Ch R = 1 ,789.832 ,62.66,70.62,60.85
XS GIS Cut Line= 6
     3168901.619    13827541.067      3168889.02      13828033.4
     3168883.183    13828187.022     3168879.633    13828371.654
     3168876.344    13828502.414     3168892.011    13829023.914
#Sta/Elev= 30
 4261.25   17.62  4292.9   18.09  4338.5    19.9 4454.12    20.3 4604.01   20.32
 4690.38   19.42  4711.6   19.75 4726.97   18.41 4810.05   15.71 4855.12   14.65
 4907.67    12.4 4959.75    2.33 4964.29    -.55    5043   -1.21 5045.66     .23
 5046.54    2.63 5092.33   14.27  5115.8   11.04 5199.73   13.23 5236.26   13.62
 5286.98    14.7 5298.26   15.86 5334.06   18.28 5341.81   19.06 5408.86   21.57
 5431.34   22.07 5453.46   22.34 5551.98    21.8 5613.86   22.31 5744.68   22.07
#Mann= 4 ,-1 , 0
 4261.25     .07       0 4907.67    .035       0 5092.33     .07       0
  5115.8     .15       0
#XS Ineff= 2 , 0
       0    4885    13.9    5089       0    13.9
Permanent Ineff=
       F       F
Bank Sta=4907.67,5092.33
XS Rating Curve= 0
Exp/Cntr=.5,.3

Type RM Length L Ch R = 3 ,754     ,,,
BEGIN DESCRIPTION:
UNNAMED ROAD
END DESCRIPTION:
Bridge Culvert--1,0,-1,-1, 0
Deck Dist Width WeirC Skew NumUp NumDn MinLoCord MaxHiCord MaxSubmerge Is_Ogee
8,43,2.6,0, 8, 8, , , .95, 0, 0,0,,
    4700    4800    4870    4990    5010    5090    5200    5300
   14.77    14.8    14.9   14.99   14.99    14.9    14.8    14.8
                   13.35   13.35   13.35   13.35
    4700    4800    4870    4990    5010    5090    5200    5300
   14.77    14.8    14.9   14.99   14.99    14.9    14.8    14.8
                   13.35   13.35   13.35   13.35
Pier Skew, UpSta & Num, DnSta & Num=  ,4943, 4 ,4943, 4 , 3 , 3 , 0 ,,
     1.5     1.5       2       2
      -2   11.35   11.35      14
     1.5     1.5       2       2
      -2   11.35   11.35      14
Pier Skew, UpSta & Num, DnSta & Num=  ,4966, 4 ,4966, 4 , 3 , 3 , 0 ,,
     1.5     1.5       2       2
      -2   11.35   11.35      14
     1.5     1.5       2       2
      -2   11.35   11.35      14
Pier Skew, UpSta & Num, DnSta & Num=  ,4989, 4 ,4989, 4 , 3 , 3 , 0 ,,
     1.5     1.5       2       2
      -2   11.35   11.35      14
     1.5     1.5       2       2
      -2   11.35   11.35      14
Pier Skew, UpSta & Num, DnSta & Num=  ,5012, 4 ,5012, 4 , 3 , 3 , 0 ,,
     1.5     1.5       2       2
      -2   11.35   11.35      14
     1.5     1.5       2       2
      -2   11.35   11.35      14
Pier Skew, UpSta & Num, DnSta & Num=  ,5035, 4 ,5035, 4 , 3 , 3 , 0 ,,
     1.5     1.5       2       2
      -2   11.35   11.35      14
     1.5     1.5       2       2
      -2   11.35   11.35      14
Pier Skew, UpSta & Num, DnSta & Num=  ,5058, 4 ,5058, 4 , 3 , 3 , 0 ,,
     1.5     1.5       2       2
      -2   11.35   11.35      14
     1.5     1.5       2       2
      -2   11.35   11.35      14
BR Coef=-1 , 1 , 1 ,1.25, 0 ,,,.8,-1,2,0,
WSPro=,,,, 1 ,,,, 0 ,,,, 0 ,,,,-1 ,-1 ,-1 , 0 , 0 , 0 , 0 , 0
BC Design=,, 0 ,, 0 ,,,,,,
BC HTab HWMax=22.34

Type RM Length L Ch R = 1 ,719.211 ,83.75,80.57,81.13
XS GIS Cut Line= 6
     3168843.219    13827516.901     3168829.048     13828031.52
     3168823.205    13828185.306     3168819.648    13828370.323
     3168816.321     13828502.56     3168832.038    13829025.715
#Sta/Elev= 30
 4218.87   15.29 4289.91   17.37 4348.54   20.54 4423.66   20.33 4540.41   20.58
  4559.8   19.93 4591.24   20.46 4626.01   20.04 4667.08   20.22 4698.69   18.31
 4761.51   16.45 4810.05   13.15 4855.12   14.65 4907.67    12.4 4959.75    2.33
 4964.29    -.55    5043   -1.13 5045.66     .23 5046.54    2.63 5092.33   14.27
  5115.8   11.04    5150   11.73  5171.6   14.58 5265.08   15.49 5300.12   17.04
 5314.25   17.01  5360.2   19.06 5455.16   21.18 5548.58   22.32  5728.3   22.05
#Mann= 4 ,-1 , 0
 4218.87     .07       0 4907.67    .035       0 5092.33     .07       0
    5150     .15       0
#XS Ineff= 2 , 0
       0    4885    13.8    5089       0    13.8
Permanent Ineff=
       F       F
Bank Sta=4907.67,5092.33
XS Rating Curve= 0
Exp/Cntr=.5,.3

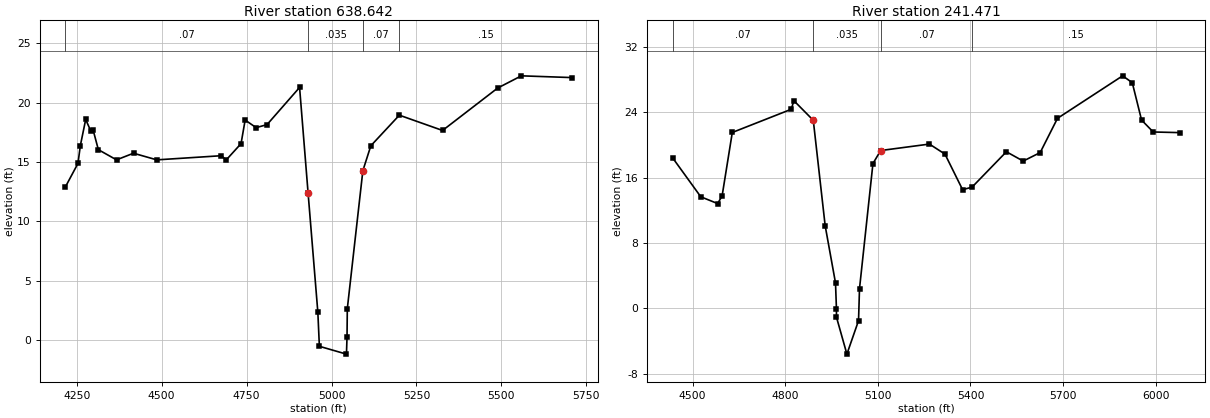
Type RM Length L Ch R = 1 ,638.642 ,312.64,397.17,454.66
XS GIS Cut Line= 6
     3168760.653    13827535.026     3168749.086    13828029.012
     3168743.234    13828183.018     3168739.667    13828368.548
     3168736.291    13828502.756     3168752.074    13829028.118
#Sta/Elev= 30
 4215.84   12.86 4253.52   14.88  4260.6   16.39 4276.33   18.59 4290.84   17.64
 4298.54   17.66 4313.57   16.04 4367.05   15.18 4417.06   15.74 4485.61   15.18
 4675.63   15.53 4689.91   15.17 4733.67   16.55 4745.74   18.54    4778    17.9
 4810.05   18.15    4906   21.29    4931    12.4 4959.75    2.33 4964.29    -.55
    5044   -1.21 5045.66     .23 5046.54    2.63 5092.33   14.27  5115.8   16.37
 5199.73   18.95 5326.95   17.66 5489.23   21.24 5559.01   22.27 5709.49   22.12
#Mann= 4 ,-1 , 0
 4215.84     .07       0    4931    .035       0 5092.33     .07       0
 5199.73     .15       0
Bank Sta=4931,5092.33
XS Rating Curve= 0
Exp/Cntr=.3,.1

Type RM Length L Ch R = 1 ,241.471 ,288.95,241.47,250.03
XS GIS Cut Line= 6
     3168525.269    13827719.244     3168396.761    13828155.369
     3168322.014    13828360.446     3168310.682    13828465.276
     3168224.126    13828909.554     3168218.241    13829321.482
#Sta/Elev= 30
 4435.64   18.41 4526.57   13.66 4581.13   12.83 4595.62   13.77  4628.6   21.53
  4819.6   24.37    4828   25.42 4890.86   23.02 4929.36   10.12 4962.84    3.12
 4965.93     -.1 4965.95   -1.06 4999.74   -5.59 5037.43   -1.49 5040.55    2.42
 5084.09   17.73 5109.14   19.32 5266.99   20.11 5317.37   18.88  5374.4   14.53
    5405   14.84 5516.19   19.17 5570.69   18.03 5625.69   19.07 5681.71   23.26
 5892.67   28.46  5923.9   27.62 5953.99   23.05 5991.66   21.59 6078.62   21.51
#Mann= 4 ,-1 , 0
 4435.64     .07       0 4890.86    .035       0 5109.14     .07       0
    5405     .15       0
Bank Sta=4890.86,5109.14
XS Rating Curve= 0
Exp/Cntr=.3,.1

Chan Stop Cuts=-1

--- I101-00-00.g02 (geometry) ---

Geom Title=I101-00-00 June 2007
Version=Version 3.0.1  Mar 2001

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
River Reach=I101-00-00    ,I101-00-00_0002
Reach XY= 30
      3186685.25       13812034.      3183902.75       13812904.
       3183552.5       13812866.        3182773.       13813292.
       3182347.5       13813930.      3181844.75       13814251.
      3180778.25       13815555.      3179622.75       13815957.
      3178030.75       13817358.        3177596.       13817933.
       3177238.5       13818979.       3176961.5       13820754.
      3176582.75       13821275.      3175315.25       13821988.
       3175117.5       13822276.      3174919.75       13823018.
      3174622.25       13823261.        3174330.       13824233.
      3174098.25       13824444.       3173857.5       13825451.
      3173158.75       13826261.      3172784.75       13826431.
      3172606.25       13826816.      3171195.75       13826883.
        3170848.       13827484.       3170582.5       13827681.
     3170251.274    13827796.295     3169659.889    13827758.316
     3168824.353    13828322.573        3168134.       13828178.

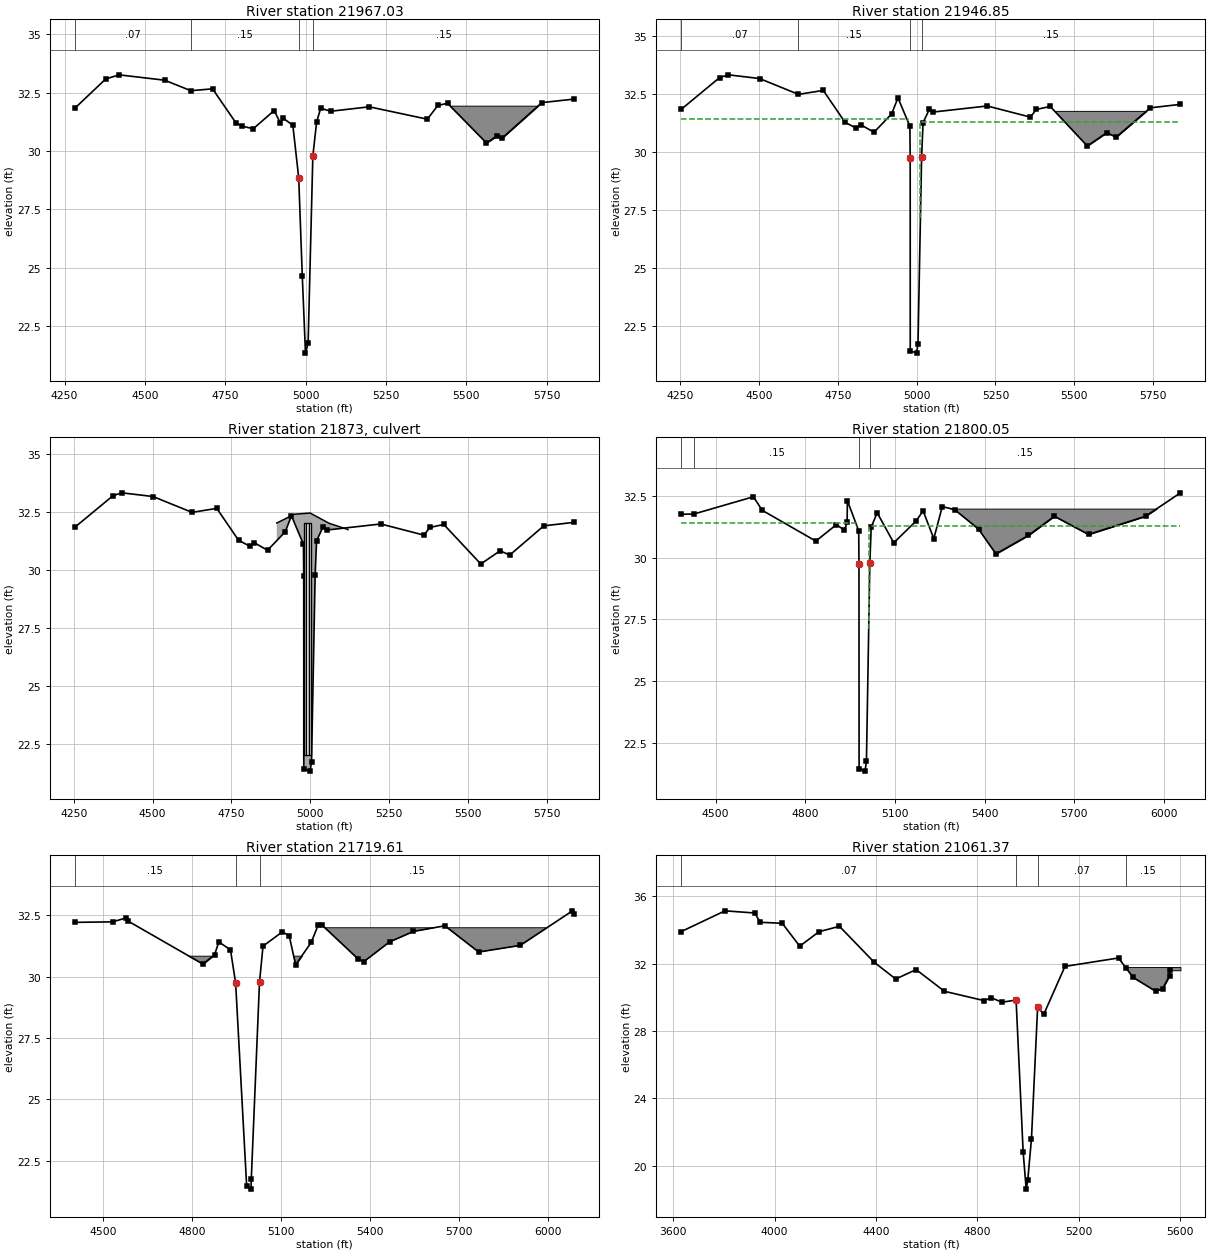
Type RM Length L Ch R = 1 ,21967.03,19.7,20.18,20.88
XS GIS Cut Line= 6
 3181516.644222813813598.3519885     3181942.375    13814124.843
     3181955.685    13814145.423     3181977.392    13814168.336
     3182102.002    13814335.577     3182528.158    13814774.051
#Sta/Elev= 30
 4282.15   31.83 4377.92   33.08 4419.49   33.26 4561.52   33.03 4643.09   32.58
 4710.57   32.66 4783.47    31.2 4803.59   31.06 4837.22   30.95 4902.41   31.73
 4921.76   31.19  4928.5   31.42  4960.5    31.1  4978.8   28.84  4989.8   24.66
 4999.81   21.34    5008   21.76  5022.7   29.78  5034.6   31.25  5047.3   31.83
 5078.61    31.7 5198.25   31.89 5379.06   31.36 5411.89   31.95 5441.81   32.04
  5563.1   30.34 5595.21   30.64 5610.86   30.54  5735.4   32.07 5835.43   32.22
#Mann= 4 ,-1 , 0
 4282.15     .07       0 4643.09     .15       0  4978.8    .015       0
  5022.7     .15       0
#Block Obstruct= 1 ,-1
 5440.34 5767.44   31.94
Bank Sta=4978.8,5022.7
XS Rating Curve= 0
Exp/Cntr=.5,.3

Type RM Length L Ch R = 1 ,21946.85,178.35,146.8,116.35
XS GIS Cut Line= 6
  3181480.309553 13813591.842254     3181922.152    13814129.119
     3181930.153    13814145.121     3181962.086    13814181.261
     3182086.741    13814348.571     3182513.816     13814787.99
#Sta/Elev= 30
 4253.64   31.83 4374.87   33.19  4403.1   33.31 4501.66   33.15 4625.21   32.47
 4703.81   32.64 4772.82   31.27 4807.59   31.02 4823.34   31.16 4864.77   30.84
  4920.7   31.63 4940.73   32.32 4978.57    31.1 4979.56   29.75 4979.75   21.44
 4999.81   21.34 5004.28   21.75 5015.77   29.78 5020.37   31.25  5040.4   31.83
 5052.97   31.71 5224.08   31.97 5361.04   31.49 5379.44   31.82 5423.79   31.95
  5541.2   30.25 5602.82   30.82 5632.86   30.63 5741.05   31.89 5836.84   32.04
#Mann= 4 ,-1 , 0
 4253.64     .07       0 4625.21     .15       0 4979.56    .015       0
 5015.77     .15       0
#XS Ineff= 2 , 0
       0    4972    31.4    5012       0    31.3
Permanent Ineff=
       F       F
#Block Obstruct= 1 ,-1
 5423.32  5795.8   31.76
Bank Sta=4979.56,5015.77
XS Rating Curve= 0
Exp/Cntr=.5,.3

Type RM Length L Ch R = 2 ,21873   ,,,
BEGIN DESCRIPTION:
WICHITA ST
END DESCRIPTION:
Bridge Culvert--1,0,-1,-1, 0
Deck Dist Width WeirC Skew NumUp NumDn MinLoCord MaxHiCord MaxSubmerge Is_Ogee
1,133,2.6,0, 5, 5, , , .95, 0, 0,0,,
    4894    4950    5000    5060    5120
   32.01   32.39   32.44      32   31.73
                                        
    4894    4950    5000    5060    5120
   32.01   32.39   32.44      32   31.73
                                        
BR Coef=-1 , 0 , 0 ,, 0 ,,,.8,-1,,0,
WSPro=,,,, 1 ,,,, 0 ,,,, 0 ,,,,-1 ,-1 ,-1 , 0 , 0 , 0 , 0 , 0
Multiple Barrel Culv=2,10,8,133,.012,.7,1,8,3,22.028,21.821, 3,Culvert #1  , 0 ,1
  4983.9  4983.9    4992    4992  5000.1  5000.1
Culvert Bottom n=.012
BC Design=,, 0 ,, 0 ,,,,,,
BC HTab HWMax=33.31

Type RM Length L Ch R = 1 ,21800.05,85.68,80.43,74.04
XS GIS Cut Line= 5
      3181388.16    13813859.564      3181830.04    13814255.428
     3181860.872    13814283.296     3181871.545    13814294.562
     3182740.003     13815122.58
#Sta/Elev= 30
 4385.32   31.77 4427.37   31.78 4626.39   32.48 4655.84   31.93 4835.19   30.68
 4904.09   31.35 4930.71   31.12 4939.78   31.44 4940.73   32.32 4978.57    31.1
 4979.45   29.75 4979.81   21.44 4999.81   21.34 5004.43   21.74 5015.77   29.78
 5020.37   31.25  5040.4   31.83 5095.71   30.61 5170.89    31.5 5193.85   31.91
 5229.73   30.78 5258.05   32.08 5299.17   31.96 5379.24   31.17 5437.43   30.16
 5546.18   30.91 5632.97   31.69 5747.35   30.95  5938.1   31.69 6054.73   32.64
#Mann= 4 ,-1 , 0
 4385.32     .07       0 4427.37     .15       0 4979.45    .015       0
 5015.77     .15       0
#XS Ineff= 2 , 0
       0    4972    31.4    5012       0    31.3
Permanent Ineff=
       F       F
#Block Obstruct= 1 ,-1
 5263.03 6031.93      32
Bank Sta=4979.45,5015.77
XS Rating Curve= 0
Exp/Cntr=.5,.3

Type RM Length L Ch R = 1 ,21719.61,671.7,658.25,624.65
XS GIS Cut Line= 4
      3181341.47    13813947.966     3181777.096     13814315.41
     3181790.038    13814327.108     3182672.404     13815125.18
#Sta/Elev= 29
 4405.48   32.22 4532.89   32.24 4577.66    32.4 4585.16   32.27 4837.18   30.52
  4876.7    30.9    4891   31.42  4930.3    31.1  4947.7   29.75 4984.91   21.46
 4999.81   21.34 5000.53   21.76  5028.2   29.78    5040   31.25  5104.9   31.83
 5128.25   31.68 5149.93   30.49  5202.6    31.4 5226.14   32.11 5238.13   32.12
 5359.62   30.74 5379.31   30.61 5466.68   31.42 5547.48   31.85 5653.45   32.08
  5767.5   31.01 5907.85   31.28 6083.63   32.69 6088.92   32.56
#Mann= 3 ,-1 , 0
 4405.48     .15       0  4947.7    .015       0  5028.2     .15       0
#Block Obstruct= 3 ,-1
 5241.39 6162.19      32    4765    4880   30.86    5135    5180   30.86
Bank Sta=4947.7,5028.2
XS Rating Curve= 0
Exp/Cntr=.3,.1

Type RM Length L Ch R = 1 ,21061.37,553.6,562.34,583.88
XS GIS Cut Line= 6
     3180290.147    13814069.531     3181268.091    13814754.644
     3181360.753    13814830.864     3181431.077    13814878.448
     3181529.152    13814936.973     3181859.277    13815185.602
#Sta/Elev= 30
 3632.24    33.9 3804.51   35.13 3922.13      35 3943.02   34.45 4030.22   34.39
 4099.25   33.03 4175.25   33.89 4255.89   34.21 4393.19   32.07 4477.77   31.08
 4558.25   31.64 4669.98   30.35 4825.55    29.8  4855.1   29.97 4895.94    29.7
 4952.54   29.83 4980.43    20.8 4992.37    18.6  4998.5   19.12 5013.23    21.6
 5037.46    29.4 5061.87   28.99 5145.39   31.83 5356.62   32.33 5385.29   31.75
 5413.88   31.18 5502.46   30.36 5530.39   30.51 5557.79   31.27 5558.67    31.6
#Mann= 4 ,-1 , 0
 3632.24     .07       0 4952.54    .035       0 5037.46     .07       0
 5385.29     .15       0
#Block Obstruct= 1 ,-1
 5356.62 5600.84   31.79
Bank Sta=4952.54,5037.46
XS Rating Curve= 0
Exp/Cntr=.3,.1

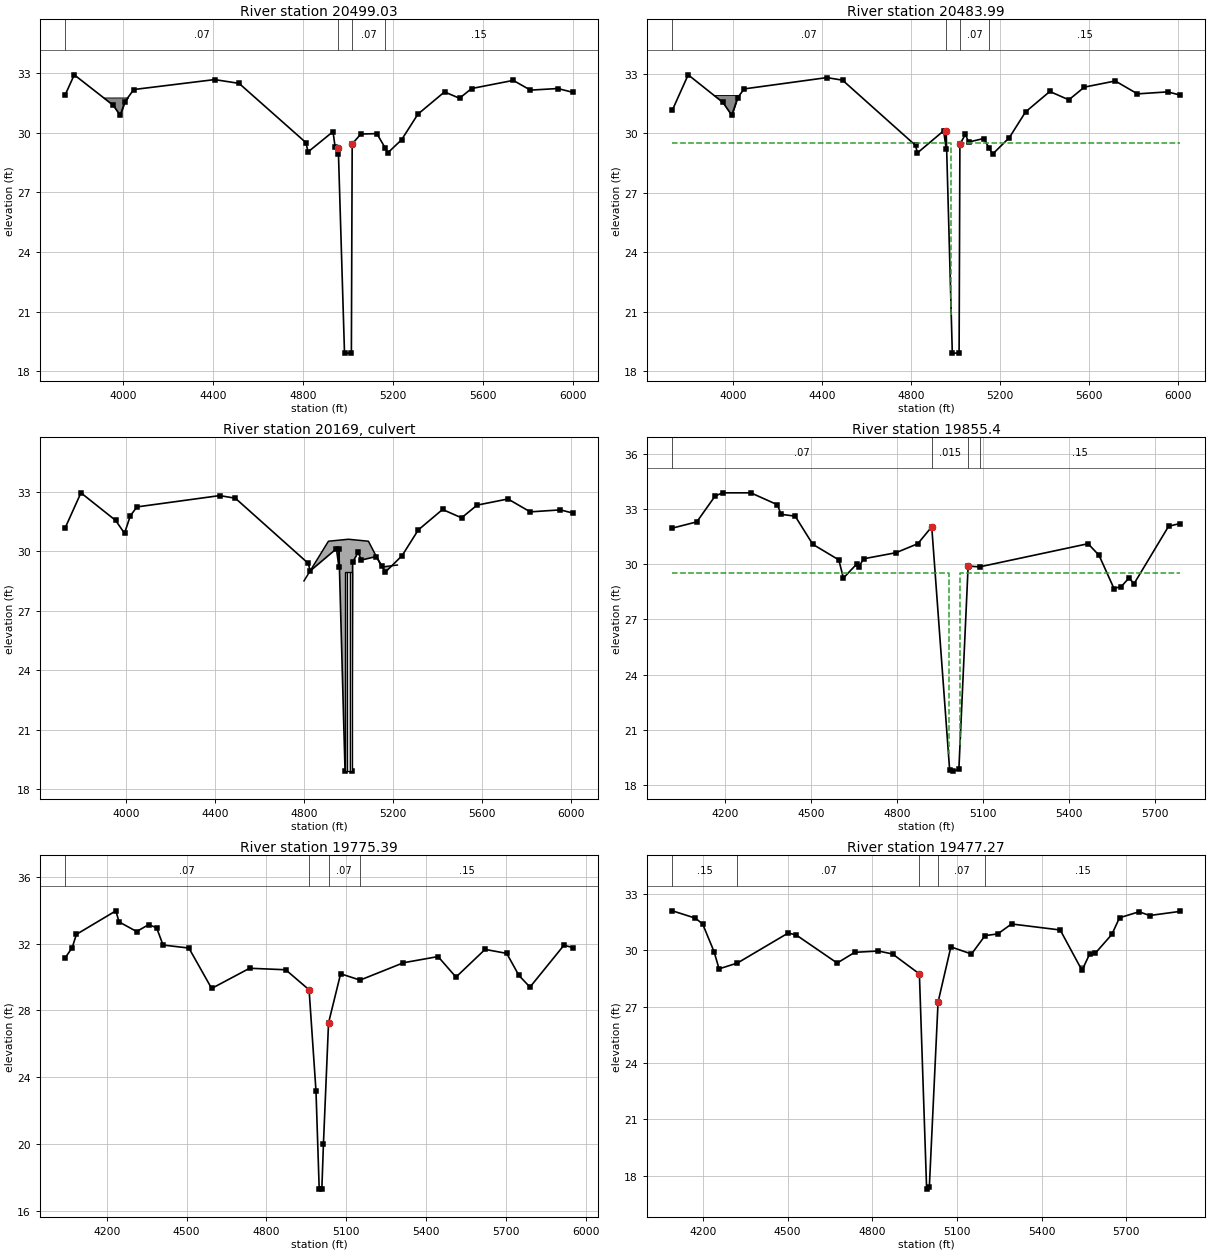
Type RM Length L Ch R = 1 ,20499.03,15.13,15.04,15.82
XS GIS Cut Line= 6
 3180045.584526713814461.7884609     3180960.471    13815221.701
     3180979.705    13815234.629     3181049.842    13815285.716
     3181075.952    13815307.872     3181768.033    13815918.805
#Sta/Elev= 30
 3742.98   31.91 3783.36   32.92 3956.31   31.39 3987.68   30.88 4008.05   31.56
 4048.07   32.18 4407.34   32.68 4516.02   32.49 4813.05   29.51 4822.84   29.04
 4933.72   30.06 4943.02   29.29 4956.04   28.93 4957.17   29.23 4984.81   18.91
 5015.34   18.91 5018.95   29.44  5057.4   29.94 5128.71   29.96 5166.61   29.22
    5178      29 5238.47   29.65  5311.1   30.94 5429.47   32.06 5496.06   31.74
 5549.83   32.23 5734.94   32.64 5811.52   32.15  5933.1   32.23 5999.64   32.04
#Mann= 4 ,-1 , 0
 3742.98     .07       0 4957.17    .015       0 5018.95     .07       0
 5166.61     .15       0
#Block Obstruct= 1 ,-1
 3788.87 4061.97   31.78
Bank Sta=4957.17,5018.95
XS Rating Curve= 0
Exp/Cntr=.5,.3

Type RM Length L Ch R = 1 ,20483.99,500.6,628.59,728.41
XS GIS Cut Line= 6
 3180022.107617213814461.7878942     3180951.472    13815233.726
     3180971.102     13815246.92     3181040.561    13815297.513
     3181071.546    13815323.806     3181762.113    13815939.733
#Sta/Elev= 30
 3725.63   31.17 3796.53   32.94 3952.55   31.55 3992.62    30.9 4018.64   31.78
 4048.54   32.23 4420.51    32.8 4491.01   32.67  4819.6   29.38 4827.56      29
 4946.03   30.12 4957.03   29.21 4957.17   30.09 4984.81   18.91 5015.34   18.91
 5018.95   29.44  5043.7   29.94 5057.89   29.55 5126.13   29.73 5149.83   29.26
 5165.85   28.94 5241.14   29.77 5314.33   31.07 5423.47    32.1 5509.01   31.68
 5578.82   32.32 5717.84   32.63 5817.92   31.98 5953.52   32.08 6009.33   31.92
#Mann= 4 ,-1 , 0
 3725.63     .07       0 4957.17    .015       0 5018.95     .07       0
 5149.83     .15       0
#XS Ineff= 2 , 0
       0    4980    29.5    5020       0    29.5
Permanent Ineff=
       F       F
#Block Obstruct= 1 ,-1
 3834.03 4073.53   31.92
Bank Sta=4957.17,5018.95
XS Rating Curve= 0
Exp/Cntr=.5,.3

Type RM Length L Ch R = 2 ,20169   ,,,
BEGIN DESCRIPTION:
PASADENA BLVD
END DESCRIPTION:
Bridge Culvert--1,0,-1,-1, 0
Deck Dist Width WeirC Skew NumUp NumDn MinLoCord MaxHiCord MaxSubmerge Is_Ogee
5,605,2.6,0, 6, 6, , , .95, 0, 0,0,,
    4800    4910    5000    5090    5150    5220
    28.5    30.5    30.6    30.5    29.2    29.3
                                                
    4800    4910    5000    5090    5150    5220
    28.5    30.5    30.6    30.5    29.2    29.3
                                                
BR Coef=-1 , 0 , 0 ,, 0 ,,,.8,-1,,0,
WSPro=,,,, 1 ,,,, 0 ,,,, 0 ,,,,-1 ,-1 ,-1 , 0 , 0 , 0 , 0 , 0
Multiple Barrel Culv=2,10,10,605,.012,.7,1,8,3,18.94,18.83, 3,Culvert #1  , 0 ,5
  4989.9  4989.9    5000    5000  5010.1  5010.1
Culvert Bottom n=.012
BC Design=,, 0 ,, 0 ,,,,,,
BC HTab HWMax=32.94

Type RM Length L Ch R = 1 ,19855.4 ,80.09,80.01,80.24
XS GIS Cut Line= 6
      3180021.82    13814737.863     3180248.825    13814970.939
      3180408.88    13815360.675     3180557.748    13815707.388
      3180678.85    13815972.938     3180856.545    13816411.541
#Sta/Elev= 30
 4017.48   31.97 4102.58   32.31 4165.99   33.71 4192.07   33.89 4290.77   33.89
 4383.68   33.24 4395.93   32.72 4445.46   32.62 4506.59   31.09 4597.57   30.24
 4613.59   29.25 4660.33   30.02 4666.72   29.84  4684.2    30.3 4796.88   30.63
 4872.95   31.12 4921.57   32.04 4983.97   18.81 4996.11   18.74 5016.16   18.83
 5048.43    29.9 5088.52   29.86 5466.58   31.12  5504.8   30.49 5556.97   28.68
 5582.57   28.79 5609.54   29.26 5626.81   28.94 5747.38   32.07 5787.24   32.22
#Mann= 4 ,-1 , 0
 4017.48     .07       0 4921.57    .015       0 5048.43     .07       0
 5088.52     .15       0
#XS Ineff= 2 , 0
       0    4980    29.5    5020       0    29.5
Permanent Ineff=
       F       F
Bank Sta=4921.57,5048.43
XS Rating Curve= 0
Exp/Cntr=.5,.3

Type RM Length L Ch R = 1 ,19775.39,384.04,298.11,238.94
XS GIS Cut Line= 6
 3180003.639680513814887.4523628     3180224.297    13815136.245
      3180484.37     13815739.29     3180605.367    13816004.609
     3180704.535    13816248.623     3180840.233    13816595.472
#Sta/Elev= 30
 4043.78   31.14 4070.23   31.76 4085.98   32.55 4234.28   33.96 4245.96    33.3
 4312.04   32.72 4357.25   33.13 4387.11   32.95 4411.45   31.91 4508.53   31.73
 4593.98   29.31 4736.56   30.52 4872.07   30.43    4960   29.23  4985.9   23.17
    4998    17.3  5007.9   17.29  5013.9      20 5033.07   27.25 5078.48   30.19
 5151.52   29.81 5314.58   30.85 5444.47   31.22 5511.76   29.99  5621.1   31.65
 5702.41   31.41 5748.15   30.09 5789.71   29.39 5917.39    31.9 5950.51   31.76
#Mann= 4 ,-1 , 0
 4043.78     .07       0    4960    .015       0 5033.07     .07       0
 5151.52     .15       0
Bank Sta=4960,5033.07
XS Rating Curve= 0
Exp/Cntr=.3,.1

Type RM Length L Ch R = 1 ,19477.27,24.2,20.93,20.97
XS GIS Cut Line= 6
      3179635.76    13815124.069     3180059.778    13815662.679
     3180181.107    13815801.504     3180295.335    13815946.238
     3180620.497    13816400.022 3180727.086896113816552.3150462
#Sta/Elev= 30
 4091.97   32.11 4173.12   31.72    4199   31.41 4239.36   29.94 4257.21   29.02
 4322.19   29.33 4502.37   30.93  4530.9   30.82 4675.56   29.33 4738.02    29.9
 4821.49   29.97 4872.07   29.81 4966.93   28.75 4992.57   17.29 5002.16   17.41
 5033.07   27.25 5078.48   30.19 5151.52   29.81 5199.62   30.79 5244.49   30.88
 5293.43   31.41 5465.79   31.09 5542.97   28.94 5570.34   29.82 5589.92   29.85
 5648.55   30.85 5675.93   31.74 5745.37   32.06 5782.43   31.86 5890.32   32.08
#Mann= 5 ,-1 , 0
 4091.97     .15       0 4322.19     .07       0 4966.93    .015       0
 5033.07     .07       0 5199.62     .15       0
#Block Obstruct= 1 ,-1
    5524    5560    29.2
Bank Sta=4966.93,5033.07
XS Rating Curve= 0
Exp/Cntr=.5,.3

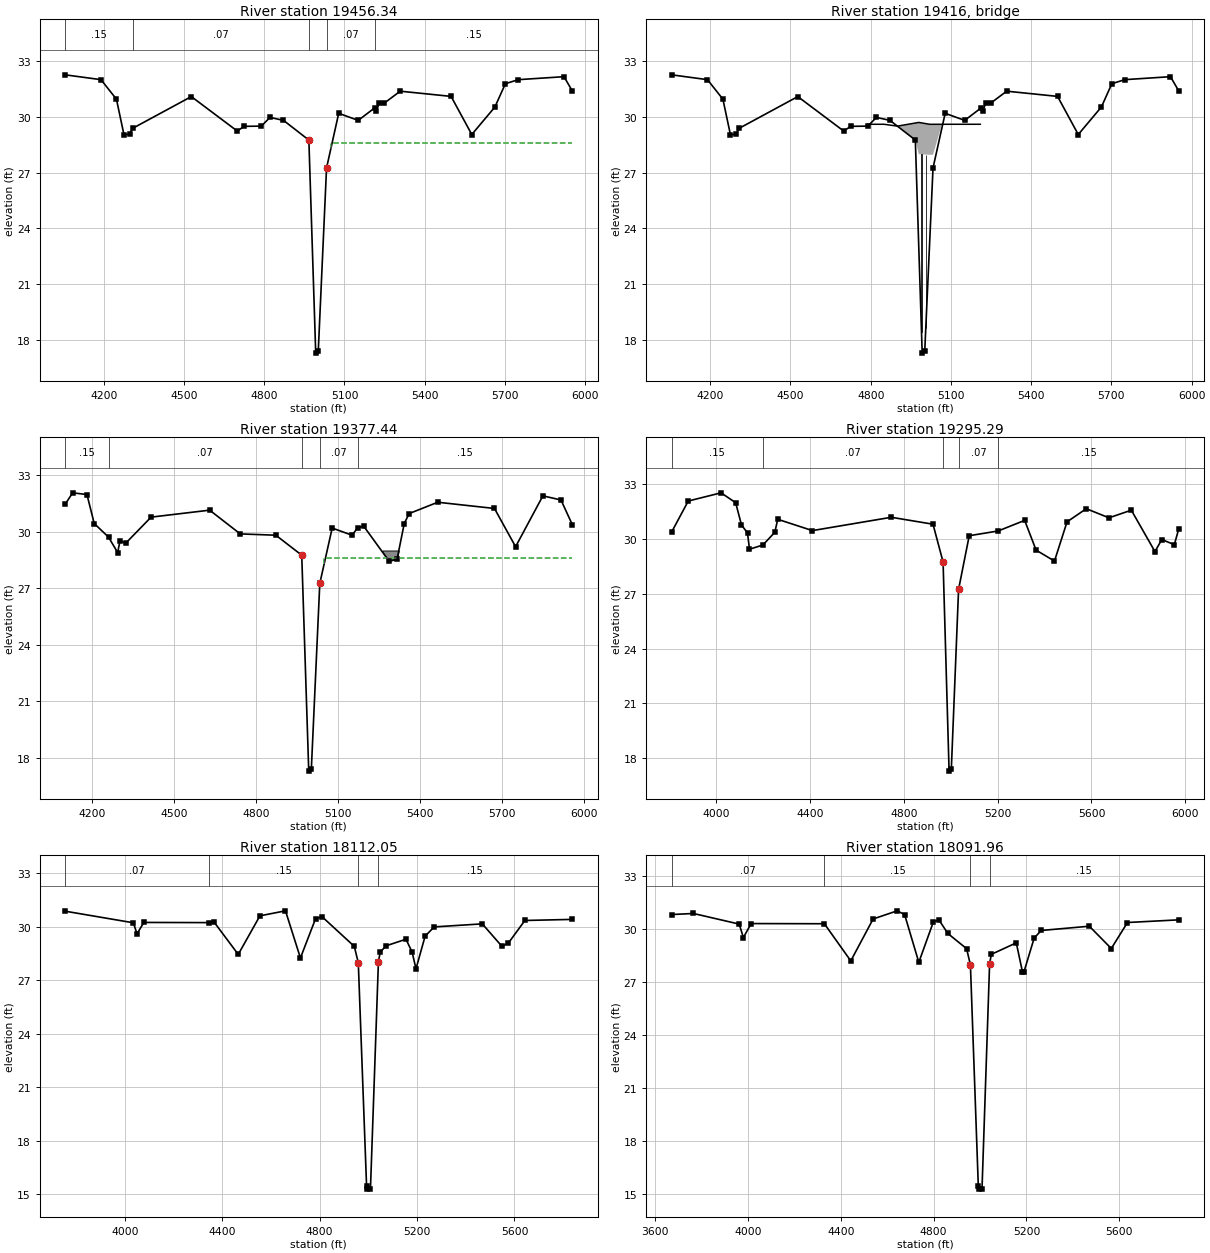
Type RM Length L Ch R = 1 ,19456.34,79.61,78.9,87.93
XS GIS Cut Line= 6
      3179571.97    13815121.169     3179788.122    13815368.755
     3180165.312    13815813.864      3180279.36    13815958.281
     3180516.246    13816288.413 3180741.384893513816611.7225468
#Sta/Elev= 30
  4055.6   32.26 4189.64      32 4247.39   30.95 4275.51   29.04 4296.28   29.06
 4307.77   29.38 4527.46   31.09 4698.75   29.24 4725.81   29.49 4789.16    29.5
 4821.49   29.97 4872.07   29.81 4966.93   28.75 4992.57   17.29 5002.16   17.41
 5033.07   27.25 5078.48   30.19 5151.52   29.81 5213.82   30.49 5219.76   30.32
 5230.53   30.77 5248.12   30.73  5308.6   31.38 5498.72    31.1 5576.19   29.05
 5662.67   30.53  5701.7   31.78 5749.74      32 5921.04   32.16 5952.04   31.39
#Mann= 5 ,-1 , 0
  4055.6     .15       0 4307.77     .07       0 4966.93    .015       0
 5033.07     .07       0 5213.82     .15       0
#XS Ineff= 2 , 0
       0    4963    28.6    5049       0    28.6
Permanent Ineff=
       F       F
Bank Sta=4966.93,5033.07
XS Rating Curve= 0
Exp/Cntr=.5,.3

Type RM Length L Ch R = 3 ,19416   ,,,
BEGIN DESCRIPTION:
BURKE ST
END DESCRIPTION:
Bridge Culvert--1,0,-1,-1, 0
Deck Dist Width WeirC Skew NumUp NumDn MinLoCord MaxHiCord MaxSubmerge Is_Ogee
5,59,2.6,0, 6, 6, , , .95, 0, 0,0,,
    4790    4850    4900    4980    5020    5210
    29.6    29.6    29.5    29.7    29.6    29.6
   27.99   27.99   27.99   27.99   27.96   27.96
    4790    4850    4900    4980    5020    5210
    29.6    29.6    29.5    29.7    29.6    29.6
   27.99   27.99   27.99   27.99   27.96   27.96
Pier Skew, UpSta & Num, DnSta & Num=  ,4990, 4 ,4990, 4 , 3 , 3 , 0 ,,
     1.2     1.2       2       2
      17   25.96   25.97    28.5
     1.2     1.2       2       2
      17   25.96   25.97    28.5
Pier Skew, UpSta & Num, DnSta & Num=  ,5006, 4 ,5006, 4 , 3 , 3 , 0 ,,
     1.2     1.2       2       2
      17   25.96   25.97    28.5
     1.2     1.2       2       2
      17   25.96   25.97    28.5
BR Coef=-1 , 1 , 0 ,, 0 ,,,.8,-1,2,0,
WSPro=,,,, 1 ,,,, 0 ,,,, 0 ,,,,-1 ,-1 ,-1 , 0 , 0 , 0 , 0 , 0
BC Design=,, 0 ,, 0 ,,,,,,
BC HTab HWMax=32.26

Type RM Length L Ch R = 1 ,19377.44,98.87,82.15,78.2
XS GIS Cut Line= 6
      3179528.47    13815184.963     3179677.462    13815360.881
     3179977.615     13815703.16     3180147.633    13815913.373
     3180244.268    13816051.674 3180628.521920513816676.6354733
#Sta/Elev= 30
 4099.94   31.45 4127.35   32.06 4179.82   31.97 4206.53   30.43 4258.89   29.71
 4292.34   28.89 4301.01   29.51 4321.47   29.38 4414.89   30.77 4629.54   31.14
 4741.53   29.88 4872.07   29.81 4966.93   28.75 4992.57   17.29 5002.16   17.41
 5033.07   27.25 5078.48   30.19 5151.52   29.81 5171.34    30.2 5194.02   30.29
 5286.59   28.44 5316.26   28.54 5342.62   30.43 5360.64   30.96 5465.33   31.56
  5673.2   31.23  5750.6    29.2 5850.64    31.9 5916.96   31.68 5958.44   30.37
#Mann= 5 ,-1 , 0
 4099.94     .15       0 4258.89     .07       0 4966.93    .015       0
 5033.07     .07       0 5171.34     .15       0
#XS Ineff= 2 , 0
       0    4963    28.6    5049       0    28.6
Permanent Ineff=
       F       F
#Block Obstruct= 1 ,-1
    5263    5327      29
Bank Sta=4966.93,5033.07
XS Rating Curve= 0
Exp/Cntr=.5,.3

Type RM Length L Ch R = 1 ,19295.29,1164.82,1183.23,1088.46
XS GIS Cut Line= 6
      3179220.71    13815031.229     3179478.231    13815281.327
     3179551.228    13815359.349      3180046.85    13815906.562
     3180163.824    13816066.211      3180564.95     13816713.45
#Sta/Elev= 30
 3808.91   30.39 3879.79   32.09 4019.74   32.54 4082.04      32 4106.98   30.78
 4132.67   30.34  4141.1   29.45 4198.34   29.68 4249.22   30.38 4261.57   31.09
 4409.52   30.47 4746.06    31.2    4924   30.82 4966.93   28.75 4992.57   17.29
 5002.16   17.41 5033.07   27.25 5078.48   30.19 5201.96   30.45    5315   31.03
 5363.76    29.4 5442.14    28.8 5495.78   30.95 5577.86   31.67 5674.64   31.17
 5769.95   31.59 5870.75   29.32    5900   29.98 5953.48    29.7 5972.41   30.57
#Mann= 5 ,-1 , 0
 3808.91     .15       0 4198.34     .07       0 4966.93    .015       0
 5033.07     .07       0 5201.96     .15       0
Bank Sta=4966.93,5033.07
XS Rating Curve= 0
Exp/Cntr=.3,.1

Type RM Length L Ch R = 1 ,18112.05,20.13,20.09,20.24
XS GIS Cut Line= 6
      3177988.73    13815477.833     3178389.001    13815843.345
     3178936.542    13816344.376     3179073.278    13816455.465
     3179156.518    13816527.336 3179657.665475813816996.2716544
#Sta/Elev= 30
 3754.92   30.86 4035.13   30.21 4050.01   29.59 4077.97   30.23 4345.38   30.22
 4364.83   30.28 4465.69   28.44 4554.77    30.6 4659.64   30.88 4721.03   28.24
 4783.17   30.44  4809.9   30.55 4942.24   28.89 4958.68   27.97 4992.58   15.49
 4993.85    15.3 5008.63   15.32 5041.32   28.04 5048.75   28.57 5072.52   28.92
 5154.47   29.29 5179.63   28.57 5195.58   27.63 5232.99   29.46 5270.23   29.98
 5467.88   30.15 5548.61   28.89  5574.7   29.07 5642.66   30.34 5837.45    30.4
#Mann= 4 ,-1 , 0
 3754.92     .07       0 4345.38     .15       0 4958.68    .015       0
 5041.32     .15       0
Bank Sta=4958.68,5041.32
XS Rating Curve= 0
Exp/Cntr=.5,.3

Type RM Length L Ch R = 1 ,18091.96,55.37,55.01,55.67
XS GIS Cut Line= 6
      3177982.93     13815509.73     3178420.031    13815898.848
     3178923.475    13816359.528     3179060.433    13816470.798
     3179143.143    13816542.211      3179699.56    13817066.876
#Sta/Elev= 30
 3671.24   30.82 3765.13   30.88 3962.51   30.28 3980.44   29.52 4013.95   30.31
 4329.42    30.3 4443.21    28.2  4539.5   30.57 4643.19   31.03 4675.07   30.82
 4736.31   28.12 4799.45   30.42 4822.94   30.52 4861.29   29.75 4942.24   28.89
 4958.68   27.97 4992.58   15.49 4993.85    15.3 5008.63   15.32 5041.32   28.04
 5048.75   28.57 5156.28   29.22    5183   27.57  5189.5   27.59  5233.3   29.49
 5263.68   29.92 5471.11   30.16 5565.55    28.9 5635.37   30.37 5856.36   30.52
#Mann= 4 ,-1 , 0
 3671.24     .07       0 4329.42     .15       0 4958.68    .015       0
 5041.32     .15       0
#XS Ineff= 2 , 0
       0    4958    26.8    5042       0    26.9
Permanent Ineff=
       F       F
Bank Sta=4958.68,5041.32
XS Rating Curve= 0
Exp/Cntr=.5,.3