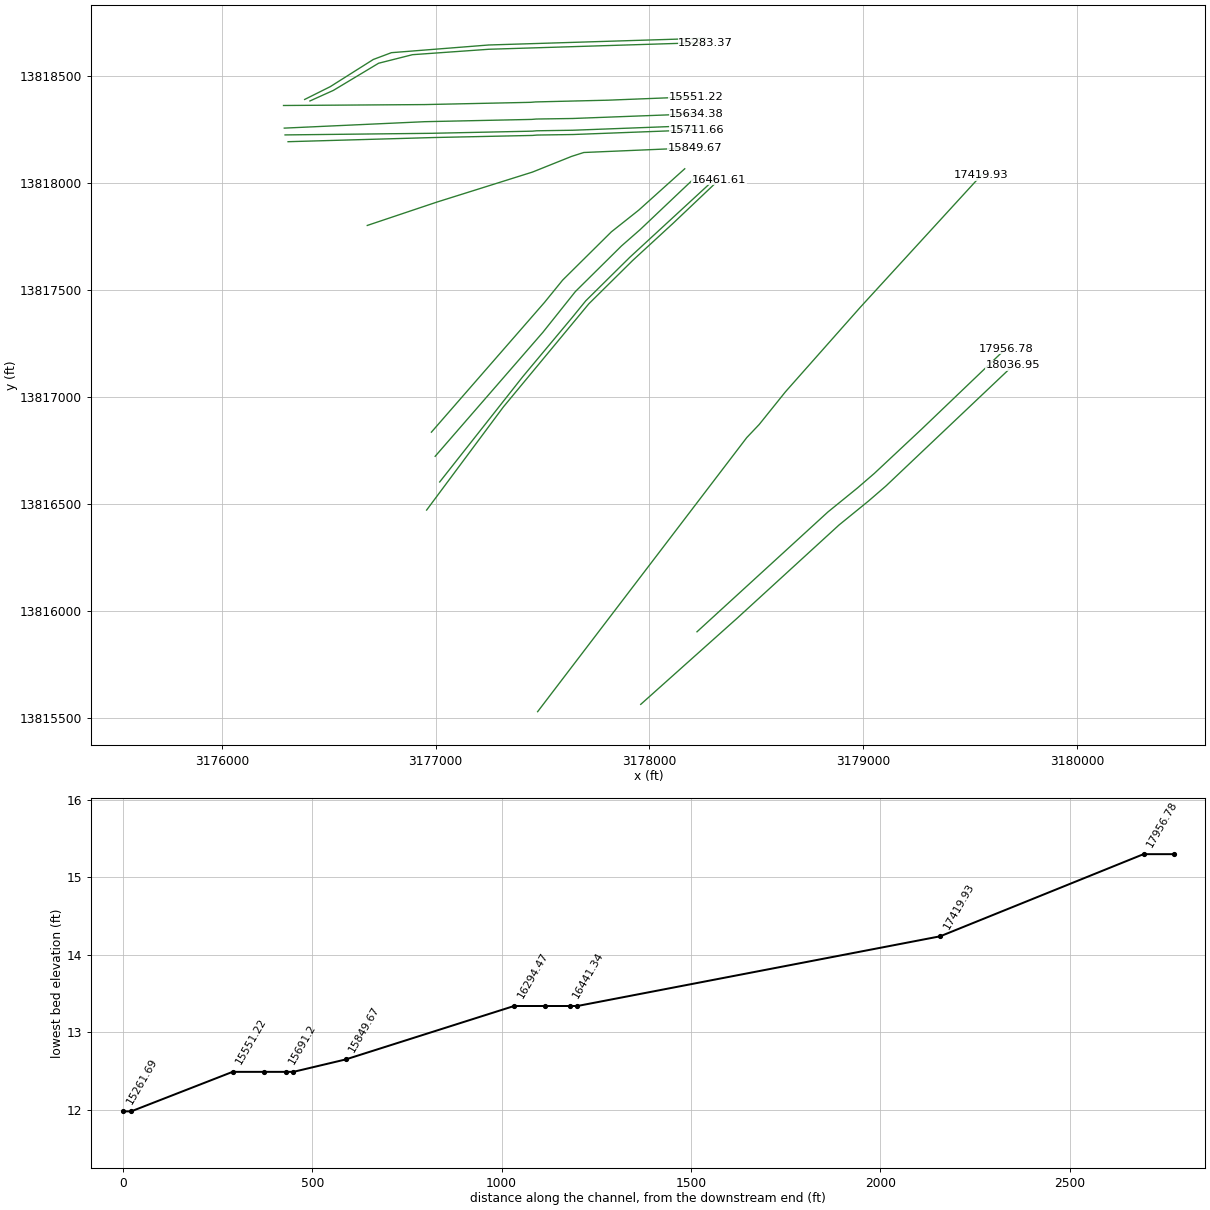
HEC-RAS study I101-00-00.prj: I101-00-00

--- I101-00-00.g02 (geometry) --- (continued)

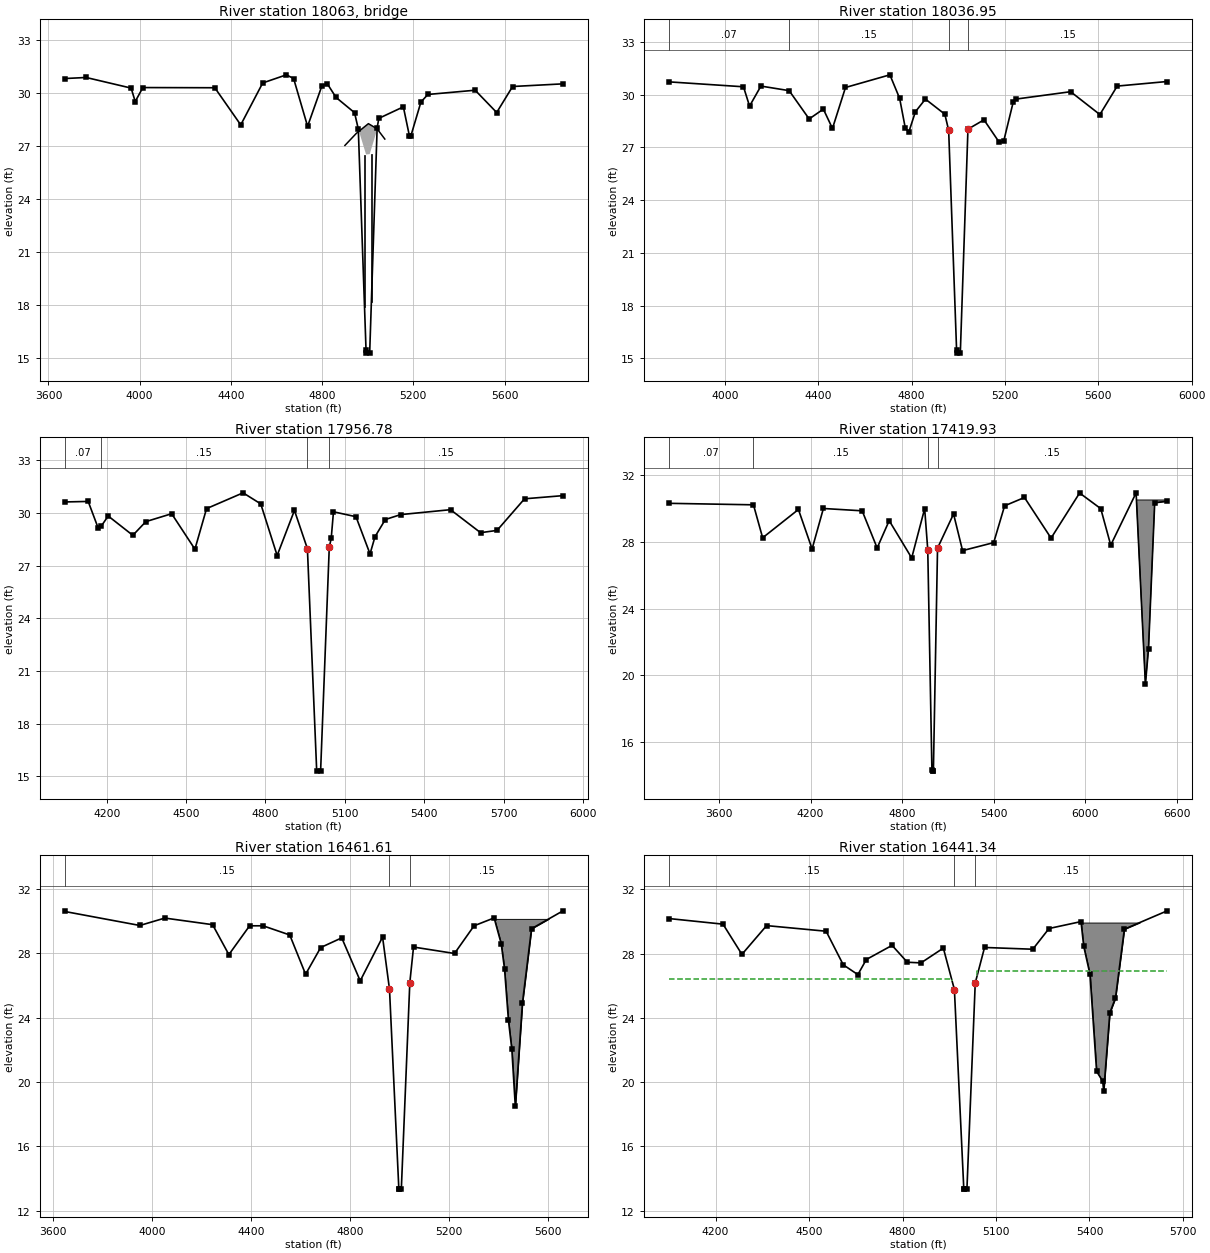
Type RM Length L Ch R = 3 ,18063   ,,,
BEGIN DESCRIPTION:
BEUSCH DR
END DESCRIPTION:
Bridge Culvert--1,0,-1,-1, 0
Deck Dist Width WeirC Skew NumUp NumDn MinLoCord MaxHiCord MaxSubmerge Is_Ogee
5,42,2.6,0, 5, 5, , , .95, 0, 0,0,,
    4900    4950    5003    5041    5075
   27.04   27.72   28.27   27.98    27.4
           26.49   26.54    26.6
    4900    4950    5003    5041    5075
   27.04   27.72   28.27   27.98    27.4
           26.49   26.54    26.6
Pier Skew, UpSta & Num, DnSta & Num=  ,4986, 4 ,4986, 4 , 3 , 3 , 0 ,,
     1.2     1.2       2       2
      15   24.49    24.5      27
     1.2     1.2       2       2
      15   24.49    24.5      27
Pier Skew, UpSta & Num, DnSta & Num=  ,5016, 4 ,5016, 4 , 3 , 3 , 0 ,,
     1.2     1.2       2       2
      15   24.49    24.5      27
     1.2     1.2       2       2
      15   24.49    24.5      27
BR Coef=-1 , 1 , 0 ,, 0 ,,,.8,-1,2,0,
WSPro=,,,, 1 ,,,, 0 ,,,, 0 ,,,,-1 ,-1 ,-1 , 0 , 0 , 0 , 0 , 0
BC Design=,, 0 ,, 0 ,,,,,,
BC HTab HWMax=31.05

Type RM Length L Ch R = 1 ,18036.95,80.54,80.17,80.97
XS GIS Cut Line= 6
      3177959.73    13815561.925     3178411.517    13815965.609
     3178887.541    13816401.198      3179025.11    13816512.964
     3179106.361    13816583.117     3179702.459    13817148.067
#Sta/Elev= 30
 3759.68   30.73 4079.43   30.45 4105.42   29.35 4154.04   30.49  4275.1   30.23
 4360.84   28.62 4421.67   29.18 4460.71   28.08 4516.51   30.41  4706.8   31.13
 4748.61   29.79 4772.85    28.1 4788.23   27.89 4816.15   29.03    4859   29.75
 4942.24   28.89 4958.68   27.97 4992.58   15.49 4993.85    15.3 5008.63   15.32
 5041.32   28.04    5110   28.57 5175.51   27.29 5194.52   27.36 5235.49   29.59
 5246.99   29.75 5481.31   30.17 5606.67   28.87 5680.98   30.49 5895.04   30.75
#Mann= 4 ,-1 , 0
 3759.68     .07       0  4275.1     .15       0 4958.68    .015       0
 5041.32     .15       0
#XS Ineff= 2 , 0
       0    4958    26.8    5042       0    26.9
Permanent Ineff=
       F       F
Bank Sta=4958.68,5041.32
XS Rating Curve= 0
Exp/Cntr=.5,.3

Type RM Length L Ch R = 1 ,17956.78,484.75,536.85,571.59
XS GIS Cut Line= 6
      3178222.86    13815901.422     3178835.273    13816461.809
     3178973.732    13816574.296      3179052.86    13816642.617
      3179275.04    13816850.637     3179667.663     13817226.36
#Sta/Elev= 30
 4041.35   30.63 4130.13   30.66 4167.95   29.14 4178.85   29.24 4205.76   29.83
 4298.86   28.73 4348.06   29.51 4445.59   29.96 4533.53   27.94 4577.44   30.25
 4715.59   31.15 4782.37   30.52 4844.35   27.58  4909.7   30.15 4958.68   27.97
 4993.85    15.3 5008.63   15.32 5041.32   28.04 5048.75   28.57 5057.23   30.07
 5142.31   29.79 5195.39   27.67  5214.2   28.65 5253.18   29.63 5311.32   29.91
 5499.63   30.19 5613.19   28.88 5675.51   29.01 5779.45   30.81  5924.8   30.99
#Mann= 4 ,-1 , 0
 4041.35     .07       0 4178.85     .15       0 4958.68    .015       0
 5041.32     .15       0
Bank Sta=4958.68,5041.32
XS Rating Curve= 0
Exp/Cntr=.3,.1

Type RM Length L Ch R = 1 ,17419.93,977.01,958.33,931.74
XS GIS Cut Line= 6
      3177477.44    13815527.693     3178455.813    13816809.983
     3178513.602    13816870.798      3178636.76    13817024.081
     3178986.984    13817419.641     3179553.567    13818038.223
#Sta/Elev= 30
 3271.57   30.32 3825.88   30.23 3886.02   28.25 4120.42   29.95 4210.06   27.58
 4284.04   30.01 4538.08   29.87 4636.32   27.64 4715.17   29.28 4862.63   27.04
  4947.7      30 4967.95   27.53 4995.24   14.31 5000.92   14.24 5004.88   14.27
 5032.05   27.63 5136.98   29.68 5196.04   27.48 5399.96   27.96 5471.55   30.17
 5601.62   30.67 5775.97   28.23 5962.91   30.94 6101.56      30 6166.87   27.81
 6333.24   30.95 6394.15   19.46 6414.45   21.59 6455.06   30.35 6533.66   30.44
#Mann= 4 ,-1 , 0
 3271.57     .07       0 3825.88     .15       0 4967.95    .015       0
 5032.05     .15       0
#Block Obstruct= 1 ,-1
    6310 6536.76   30.52
Bank Sta=4967.95,5032.05
XS Rating Curve= 0
Exp/Cntr=.3,.1

Type RM Length L Ch R = 1 ,16461.61,20.16,20.27,20.01
XS GIS Cut Line= 6
 3176958.220372713816470.8035861     3177316.977    13816952.931
     3177716.997    13817435.605     3177921.885    13817638.199
     3178112.435    13817813.424     3178325.096    13818015.081
#Sta/Elev= 30
 3648.56   30.59 3951.73   29.72 4052.51   30.18 4245.25   29.77 4310.93   27.91
 4394.59    29.7  4448.8    29.7 4556.57   29.13 4620.47   26.69 4681.45   28.35
 4766.33   28.95 4840.85   26.28 4931.08      29    4959   25.76 4996.72   13.35
 4998.11   13.34 5006.79   13.36    5041   26.17    5056   28.38  5221.3   27.98
 5300.18    29.7  5381.2   30.19 5409.75   28.59 5423.08   27.03 5438.95   23.83
 5452.57   22.03 5466.68   18.48 5495.39    24.9 5532.08   29.52 5659.07   30.63
#Mann= 3 ,-1 , 0
 3648.56     .15       0    4959    .015       0    5041     .15       0
#Block Obstruct= 2 ,-1
                         5379.62 5659.07   30.13
Bank Sta=4959,5041
XS Rating Curve= 0
Exp/Cntr=.5,.3

Type RM Length L Ch R = 1 ,16441.34,64.87,65.87,62.67
XS GIS Cut Line= 6
      3177019.35    13816602.246     3177408.257    13817095.134
     3177639.407    13817371.948     3177702.158    13817449.056
     3177907.991    13817652.593     3178307.698    13818020.881
#Sta/Elev= 30
 4050.26   30.18 4223.97   29.83 4284.69   27.95 4363.86   29.74 4554.94   29.39
 4609.92    27.3 4656.76   26.69 4683.92   27.63 4766.53   28.51 4815.51   27.46
 4859.31   27.42 4931.08   28.34 4966.55   25.76 4996.72   13.35 4998.11   13.34
 5006.79   13.36 5033.45   26.17 5063.31   28.38 5218.12   28.27 5270.25   29.56
 5372.88   29.99 5381.42   28.47 5401.65   26.71 5422.88   20.67 5442.55   20.05
 5445.66   19.42 5465.33   24.31  5483.5   25.24    5512   29.52 5649.37   30.66
#Mann= 3 ,-1 , 0
 4050.26     .15       0 4966.55    .015       0 5033.45     .15       0
#XS Ineff= 2 , 0
       0    4959    26.4    5039       0    26.9
Permanent Ineff=
       F       F
#Block Obstruct= 2 ,-1
                         5371.48 5649.37   29.93
Bank Sta=4966.55,5033.45
XS Rating Curve= 0
Exp/Cntr=.5,.3

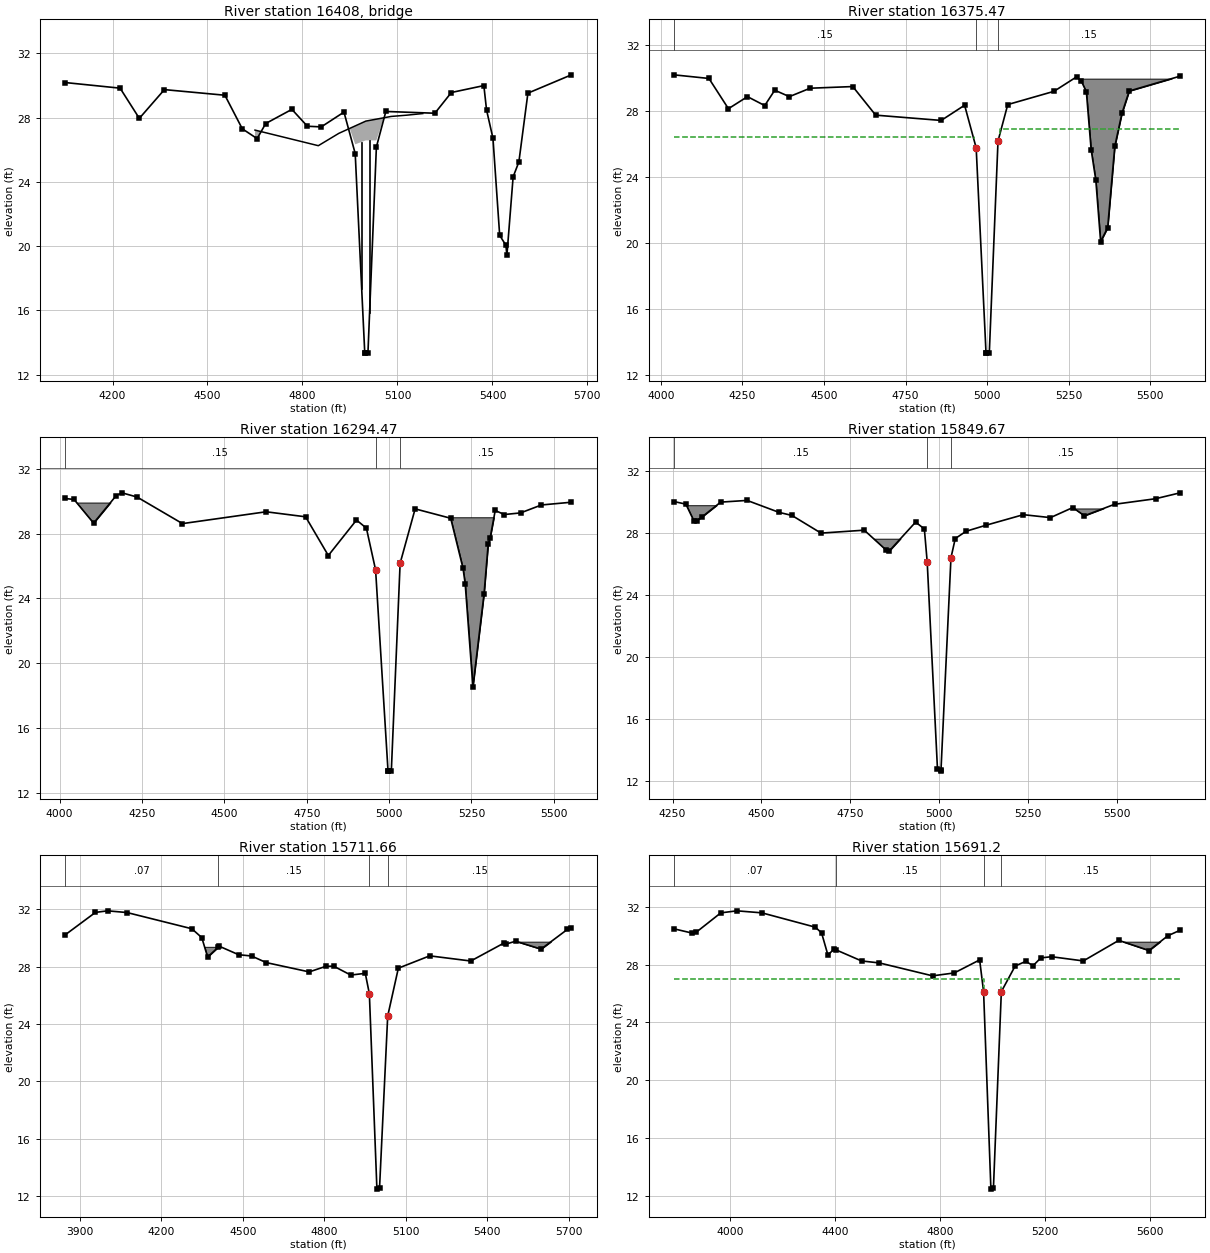
Type RM Length L Ch R = 3 ,16408   ,,,
BEGIN DESCRIPTION:
MARTHA LN
END DESCRIPTION:
Bridge Culvert--1,0,-1,-1, 0
Deck Dist Width WeirC Skew NumUp NumDn MinLoCord MaxHiCord MaxSubmerge Is_Ogee
10,40,2.6,0, 7, 7, , , .95, 0, 0,0,,
    4650    4850    4915    5000    5080    5130    5180
   27.22   26.25   27.02   27.78   28.07   28.15   28.25
           25.97   25.96   26.58   26.58
    4650    4850    4915    5000    5080    5130    5180
   27.22   26.25   27.02   27.78   28.07   28.15   28.25
           25.97   25.96   26.58   26.58
Pier Skew, UpSta & Num, DnSta & Num=  ,4987, 4 ,4987, 4 , 3 , 3 , 0 ,,
     1.2     1.2       2       2
      13   24.49    24.5      27
     1.2     1.2       2       2
      13   24.49    24.5      27
Pier Skew, UpSta & Num, DnSta & Num=  ,5012, 4 ,5012, 4 , 3 , 3 , 0 ,,
     1.2     1.2       2       2
      13   24.49    24.5      27
     1.2     1.2       2       2
      13   24.49    24.5      27
BR Coef=-1 , 1 , 0 ,, 0 ,,,.8,-1,2,0,
WSPro=,,,, 1 ,,,, 0 ,,,, 0 ,,,,-1 ,-1 ,-1 , 0 , 0 , 0 , 0 , 0
BC Design=,, 0 ,, 0 ,,,,,,
BC HTab HWMax=30.66

Type RM Length L Ch R = 1 ,16375.47,81.1,81.01,74.61
XS GIS Cut Line= 6
      3176998.17    13816722.233     3177502.299    13817302.575
     3177653.931    13817492.773     3177869.201    13817705.822
     3177956.581    13817782.331     3178223.606    13818035.379
#Sta/Elev= 30
 4039.94   30.18  4147.6   29.96 4207.31   28.13 4265.61   28.86 4318.57   28.32
 4349.24   29.25 4394.08   28.86 4457.68   29.37  4588.4   29.47 4658.54   27.74
 4859.31   27.42 4931.08   28.34 4966.55   25.76 4996.72   13.35 4998.11   13.34
 5006.79   13.36 5033.45   26.17 5063.31   28.38 5204.81   29.18 5274.47   30.06
 5288.78    29.8 5304.25   29.15 5318.84   25.66 5333.18   23.81 5347.94   20.09
 5369.53   20.93 5391.34   25.85 5413.14   27.84 5435.55    29.2 5591.49    30.1
#Mann= 3 ,-1 , 0
 4039.94     .15       0 4966.55    .015       0 5033.45     .15       0
#XS Ineff= 2 , 0
       0    4959    26.4    5039       0    26.9
Permanent Ineff=
       F       F
#Block Obstruct= 1 ,-1
 5274.85 5591.49   29.95
Bank Sta=4966.55,5033.45
XS Rating Curve= 0
Exp/Cntr=.5,.3

Type RM Length L Ch R = 1 ,16294.47,619.96,444.8,352.36
XS GIS Cut Line= 6
      3176980.53    13816835.162     3177509.755    13817442.353
     3177594.575    13817546.579     3177822.111    13817771.995
     3177950.213    13817873.612     3178165.612    13818067.276
#Sta/Elev= 30
 4016.55   30.17 4043.71   30.11 4103.01   28.65 4171.72   30.35 4189.19   30.52
 4235.01   30.26 4372.77   28.62 4626.59   29.35 4746.59   29.04 4815.51   26.65
    4901   28.84 4931.08   28.34    4959   25.76 4996.72   13.35 4998.11   13.34
 5006.79   13.36 5033.45   26.17    5079   29.53 5186.98   28.95 5224.39   25.86
 5230.98    24.9 5254.41   18.55 5288.26   24.29 5300.79   27.36 5306.79   27.75
 5322.12   29.43 5349.58   29.18 5398.96   29.28 5462.26   29.77 5553.32   29.94
#Mann= 3 ,-1 , 0
 4016.55     .15       0    4959    .015       0 5033.45     .15       0
#Block Obstruct= 2 ,-1
 4030.25 4173.11   29.92 5179.74 5381.65   29.01
Bank Sta=4959,5033.45
XS Rating Curve= 0
Exp/Cntr=.3,.1

Type RM Length L Ch R = 1 ,15849.67,247.01,138.01,88.22
XS GIS Cut Line= 6
      3176680.56    13817802.117     3177005.363    13817911.112
     3177453.043    13818051.663     3177636.372    13818125.153
     3177693.267    13818143.327     3178211.646    13818165.453
#Sta/Elev= 30
 4253.43   30.05 4287.31   29.88 4310.41   28.78 4317.41   28.81 4332.52   29.05
 4385.36   30.01 4459.75   30.12 4549.44   29.35  4585.9   29.15 4667.74   28.01
 4789.42    28.2 4850.88   26.92 4859.08   26.84 4933.97   28.72 4958.58   28.28
 4966.54   26.16 4995.48   12.79 5004.22   12.65 5005.36   12.71 5033.46   26.42
 5045.56   27.66 5076.09   28.13 5130.76   28.51 5237.19    29.2 5313.44   29.01
 5376.41   29.66 5408.89   29.13 5493.78   29.87 5609.43   30.23 5678.36   30.61
#Mann= 3 ,-1 , 0
 4253.43     .15       0 4966.54    .015       0 5033.46     .15       0
#Block Obstruct= 3 ,-1
 4242.02 4388.24   29.81 5376.41 5470.55    29.6    4800    4900   27.65
Bank Sta=4966.54,5033.46
XS Rating Curve= 0
Exp/Cntr=.3,.1

Type RM Length L Ch R = 1 ,15711.66,20.33,20.46,20.72
XS GIS Cut Line= 6
      3176310.01     13818193.84      3176991.08    13818213.336
     3177453.394    13818223.163     3177474.752    13818224.958
     3177642.648    13818227.432     3178223.507    13818249.433
#Sta/Elev= 30
 3845.37   30.22 3957.09   31.79 4002.03    31.9 4073.56   31.78 4312.21   30.65
 4348.97   30.03 4370.32   28.68 4408.71   29.35 4413.37   29.43 4484.67   28.84
 4532.08   28.75 4586.24   28.29  4744.7   27.64 4805.96   28.03  4834.7   28.04
 4897.72   27.42 4951.19   27.54 4966.22   26.12 4994.05   12.49 5003.69   12.56
 5033.78   24.56    5073    27.9 5188.49   28.76 5339.81    28.4 5463.74   29.67
 5469.31   29.58    5505   29.78 5598.74   29.23 5695.41    30.6 5710.49   30.67
#Mann= 4 ,-1 , 0
 3845.37     .07       0 4408.71     .15       0 4966.22    .015       0
 5033.78     .15       0
#Block Obstruct= 2 ,-1
 4342.65 4413.48   29.39 5506.02 5681.31   29.75
Bank Sta=4966.22,5033.78
XS Rating Curve= 0
Exp/Cntr=.5,.3

Type RM Length L Ch R = 1 ,15691.2 ,55.9,56.82,56.97
XS GIS Cut Line= 6
       3176295.9    13818225.601     3176980.523    13818233.116
     3177452.343    13818243.146      3177473.78    13818244.947
     3177642.155    13818247.427     3178222.714    13818269.417
#Sta/Elev= 30
 3786.86   30.47 3857.22   30.17 3872.75   30.24 3965.78   31.57 4027.19   31.71
 4122.34   31.57  4325.8   30.58 4349.49   30.18 4373.53   28.66 4397.22   29.07
 4403.65   29.02 4501.47   28.25 4569.86   28.11 4771.88   27.22 4854.58   27.42
 4951.19   28.32 4966.22   26.12 4994.05   12.49 5003.69   12.56 5033.78   26.13
 5086.43    27.9 5126.91   28.22 5154.52   27.92  5184.2   28.46 5225.02   28.54
 5345.88   28.25 5480.95   29.67 5595.97   28.97  5667.9   29.99 5714.34   30.37
#Mann= 4 ,-1 , 0
 3786.86     .07       0 4403.65     .15       0 4966.22    .015       0
 5033.78     .15       0
#XS Ineff= 2 , 0
       0 4966.22      27 5033.78       0      27
Permanent Ineff=
       F       F
#Block Obstruct= 1 ,-1
  5481.2 5670.04   29.58
Bank Sta=4966.22,5033.78
XS Rating Curve= 0
Exp/Cntr=.5,.3

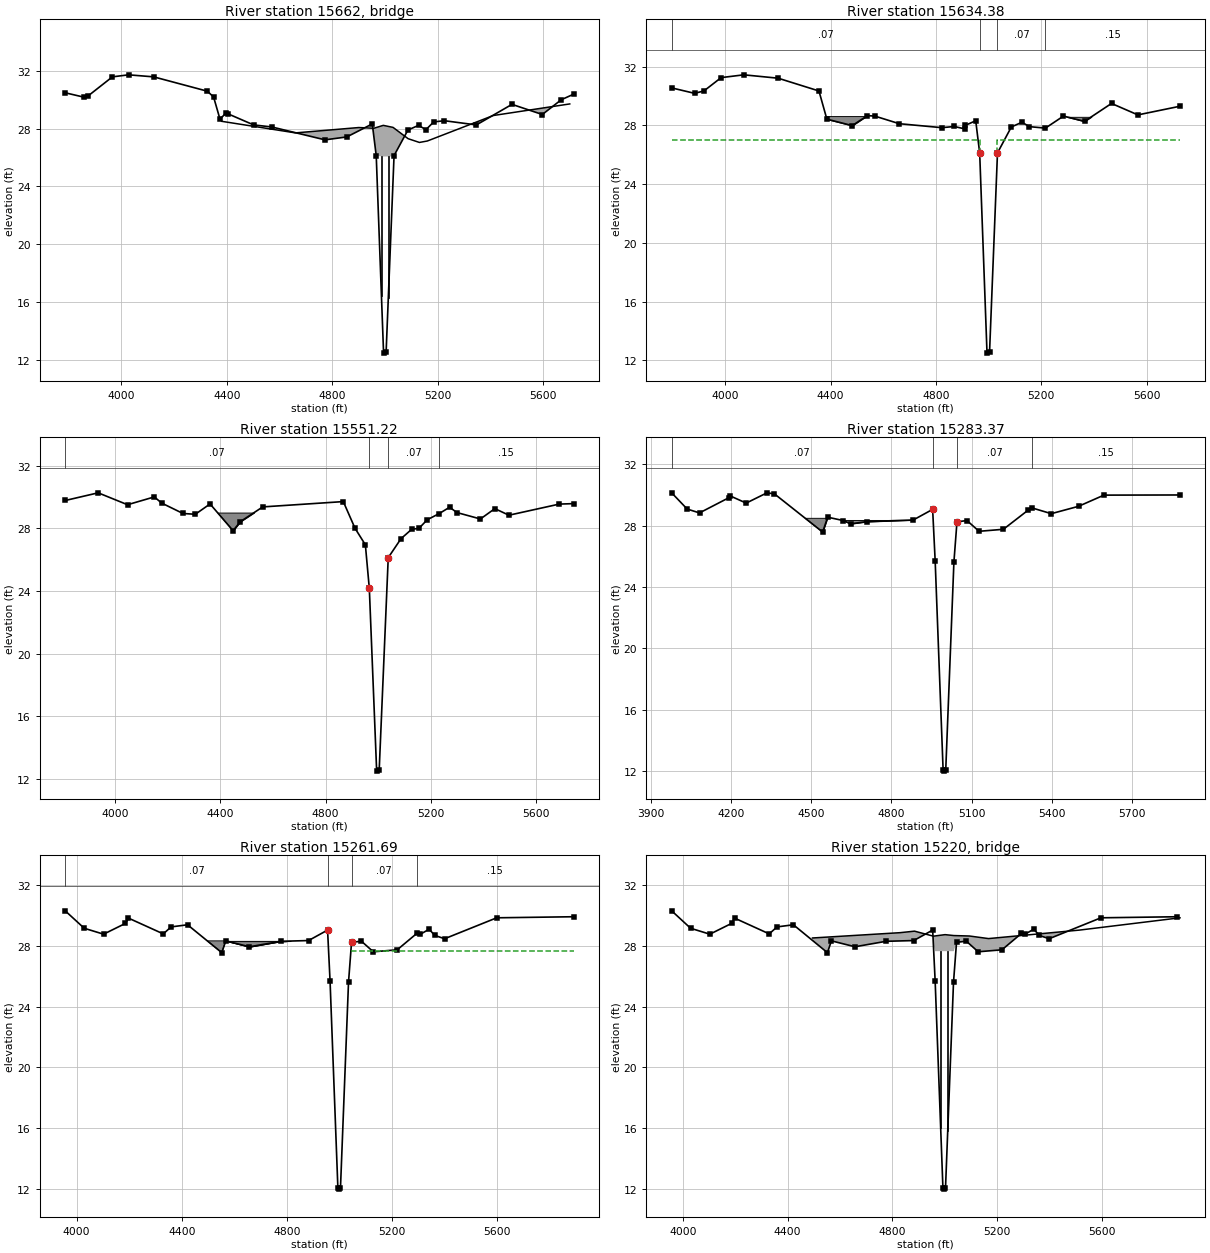
Type RM Length L Ch R = 3 ,15662   ,,,
BEGIN DESCRIPTION:
BLAKE ST
END DESCRIPTION:
Bridge Culvert--1,0,-1,-1, 0
Deck Dist Width WeirC Skew NumUp NumDn MinLoCord MaxHiCord MaxSubmerge Is_Ogee
9,37,2.6,0, 11, 11, , , .95, 0, 0,0,,
    4380    4660    4900    4957    4993    5030    5087    5130    5160    5410
    5700
    28.5    27.7   28.07   28.02   28.22   28.08    27.3   27.04   27.14    28.9
    29.7
                           26.07   26.07   26.07   26.07
        
    4380    4660    4900    4957    4993    5030    5087    5130    5160    5410
    5700
    28.5    27.7   28.07   28.02   28.22   28.08    27.3   27.04   27.14    28.9
    29.7
                           26.07   26.07   26.07   26.07
        
Pier Skew, UpSta & Num, DnSta & Num=  ,4986, 4 ,4986, 4 , 3 , 3 , 0 ,,
     1.2     1.2       2       2
      12   24.06   24.07    26.5
     1.2     1.2       2       2
      12   24.06   24.07    26.5
Pier Skew, UpSta & Num, DnSta & Num=  ,5012, 4 ,5012, 4 , 3 , 3 , 0 ,,
     1.2     1.2       2       2
      12   24.06   24.07    26.5
     1.2     1.2       2       2
      12   24.06   24.07    26.5
BR Coef=-1 , 1 , 0 ,, 0 ,,,.8,-1,2,0,
WSPro=,,,, 1 ,,,, 0 ,,,, 0 ,,,,-1 ,-1 ,-1 , 0 , 0 , 0 , 0 , 0
BC Design=,, 0 ,, 0 ,,,,,,
BC HTab HWMax=31.71

Type RM Length L Ch R = 1 ,15634.38,81.32,83.16,82.86
XS GIS Cut Line= 6
      3176292.37    13818257.362     3176948.807    13818287.454
     3177449.453    13818298.097     3177471.107    13818299.916
     3177640.801    13818302.413     3178220.536    13818324.374
#Sta/Elev= 30
 3797.08   30.56 3883.77   30.19  3919.4   30.35 3984.83   31.26 4070.97   31.45
 4201.21   31.22 4356.12   30.35 4386.15   28.43 4482.36   27.99 4539.88   28.67
 4567.95   28.64 4661.13   28.12 4822.42   27.85  4870.3   27.93 4910.93   27.76
  4911.8   28.01 4951.19   28.32 4966.22   26.12 4994.05   12.49 5003.69   12.56
 5033.78   26.13 5086.43    27.9 5126.91   28.22 5154.52   27.92 5215.75   27.82
 5284.24   28.64 5364.24   28.28 5466.59    29.5 5566.72   28.72 5726.57   29.31
#Mann= 4 ,-1 , 0
 3797.08     .07       0 4966.22    .015       0 5033.78     .07       0
 5215.75     .15       0
#XS Ineff= 2 , 0
       0 4966.22      27 5033.78       0      27
Permanent Ineff=
       F       F
#Block Obstruct= 2 ,-1
 4373.55 4538.64   28.64 5284.45 5403.79   28.59
Bank Sta=4966.22,5033.78
XS Rating Curve= 0
Exp/Cntr=.5,.3

Type RM Length L Ch R = 1 ,15551.22,249.04,267.85,265.89
XS GIS Cut Line= 6
      3176288.84    13818363.233     3176948.831    13818367.472
      3177445.25    13818378.025     3177467.219    13818379.871
     3177807.231    13818388.052     3178217.367    13818404.311
#Sta/Elev= 30
 3812.06   29.78 3937.14   30.27 4048.58   29.51  4150.4   30.01 4177.61   29.62
 4259.08   28.95 4305.87    28.9 4361.79   29.56 4449.06   27.85 4476.88   28.43
 4561.69   29.37 4867.49   29.71  4911.8   28.01 4951.19   26.95 4966.22   24.16
 4994.05   12.49 5003.69   12.56    5038   26.13 5086.43   27.34 5126.91   27.94
 5154.52      28 5186.02   28.55 5230.96   28.94 5270.99   29.35 5298.61   29.01
  5387.8    28.6 5442.56   29.26 5496.14   28.84 5687.06   29.55 5741.22   29.58
#Mann= 4 ,-1 , 0
 3812.06     .07       0 4966.22    .015       0    5038     .07       0
 5230.96     .15       0
#Block Obstruct= 1 ,-1
 4378.78 4532.69   29.01
Bank Sta=4966.22,5038
XS Rating Curve= 0
Exp/Cntr=.3,.1

Type RM Length L Ch R = 1 ,15283.37,20.32,21.68,20.74
XS GIS Cut Line= 6
      3176412.35    13818384.407     3176522.057    13818433.915
       3176733.5    13818560.859     3176891.973    13818600.859
     3177249.907    13818626.258     3178262.949    13818657.742
#Sta/Elev= 30
    3977   30.14  4035.1   29.08 4081.22   28.83 4190.03   29.81 4194.75   29.95
 4256.07   29.47 4334.06   30.14 4362.02   30.07 4542.45   27.58 4561.25   28.55
 4619.82   28.33 4647.72   28.12 4707.43   28.26 4882.07   28.37 4954.42   29.06
 4963.91   25.69 4993.64   12.05 4998.81   11.98 5003.44   12.03 5034.11   25.63
 5045.58   28.25 5083.02   28.33 5128.34   27.63 5219.35   27.76 5311.39      29
 5327.68   29.15 5398.79   28.78 5500.81   29.26 5596.01   29.99 5880.88      30
#Mann= 4 ,-1 , 0
    3977     .07       0 4954.42    .015       0 5045.58     .07       0
 5327.68     .15       0
#Block Obstruct= 2 ,-1
 4455.12 4561.88   28.51 4580.26 4909.41   28.37
Bank Sta=4954.42,5045.58
XS Rating Curve= 0
Exp/Cntr=.5,.3

Type RM Length L Ch R = 1 ,15261.69,76.19,81.02,77.65
XS GIS Cut Line= 6
      3176387.65    13818391.465     3176507.642    13818451.459
     3176708.797    13818578.504     3176793.494    13818610.266
      3177248.89    13818646.236     3178262.354    13818677.733
#Sta/Elev= 30
 3956.55   30.33 4028.92   29.18 4102.48   28.79 4185.57    29.5 4197.06   29.85
 4329.47   28.81 4359.32   29.27 4421.92   29.41 4552.07   27.57 4567.26   28.35
 4657.34   27.96 4776.26   28.32 4882.07   28.37 4954.42   29.06 4963.91   25.69
 4993.64   12.05 4998.81   11.98 5003.44   12.03 5034.11   25.63 5045.58   28.25
 5083.02   28.33 5128.34   27.63 5219.35   27.76  5293.8   28.84 5307.75   28.79
 5340.95   29.12 5361.77   28.71 5399.63   28.49 5597.71   29.87 5889.91   29.94
#Mann= 4 ,-1 , 0
 3956.55     .07       0 4954.42    .015       0 5045.58     .07       0
  5293.8     .15       0
#XS Ineff= 2 , 0
       0    4958   27.66    5043       0    27.7
Permanent Ineff=
       F       F
#Block Obstruct= 3 ,-1
 4482.87  4567.7   28.35 4567.71 4813.56   28.35 4568.26 4814.99   28.33
Bank Sta=4954.42,5045.58
XS Rating Curve= 0
Exp/Cntr=.5,.3

Type RM Length L Ch R = 3 ,15220   ,,,
BEGIN DESCRIPTION:
SOUTHMORE AVE
END DESCRIPTION:
Bridge Culvert--1,0,-1,-1, 0
Deck Dist Width WeirC Skew NumUp NumDn MinLoCord MaxHiCord MaxSubmerge Is_Ogee
10,60,2.6,0, 10, 10, , , .95, 0, 0,0,,
    4495    4830    4885    4957    5002    5035    5095    5168    5516    5900
   28.54   28.89   28.99   28.66   28.76    28.7   28.67    28.5   29.06   29.87
                           27.67   27.67   27.67   27.67
    4495    4830    4885    4957    5002    5035    5095    5168    5516    5900
   28.54   28.89   28.99   28.66   28.76    28.7   28.67    28.5   29.06   29.87
                           27.67   27.67   27.67   27.67
Pier Skew, UpSta & Num, DnSta & Num=  ,4985, 2 ,4985, 2 , 0 , 0 , 0 ,,
       2       2
      11    28.5
       2       2
      11    28.5
Pier Skew, UpSta & Num, DnSta & Num=  ,5012, 2 ,5012, 2 , 0 , 0 , 0 ,,
       2       2
      11    28.5
       2       2
      11    28.5
BR Coef=-1 , 1 , 0 ,, 0 ,,,.8,-1,2,0,
WSPro=,,,, 1 ,,,, 0 ,,,, 0 ,,,,-1 ,-1 ,-1 , 0 , 0 , 0 , 0 , 0
BC Design=,, 0 ,, 0 ,,,,,,
BC HTab HWMax=30.33