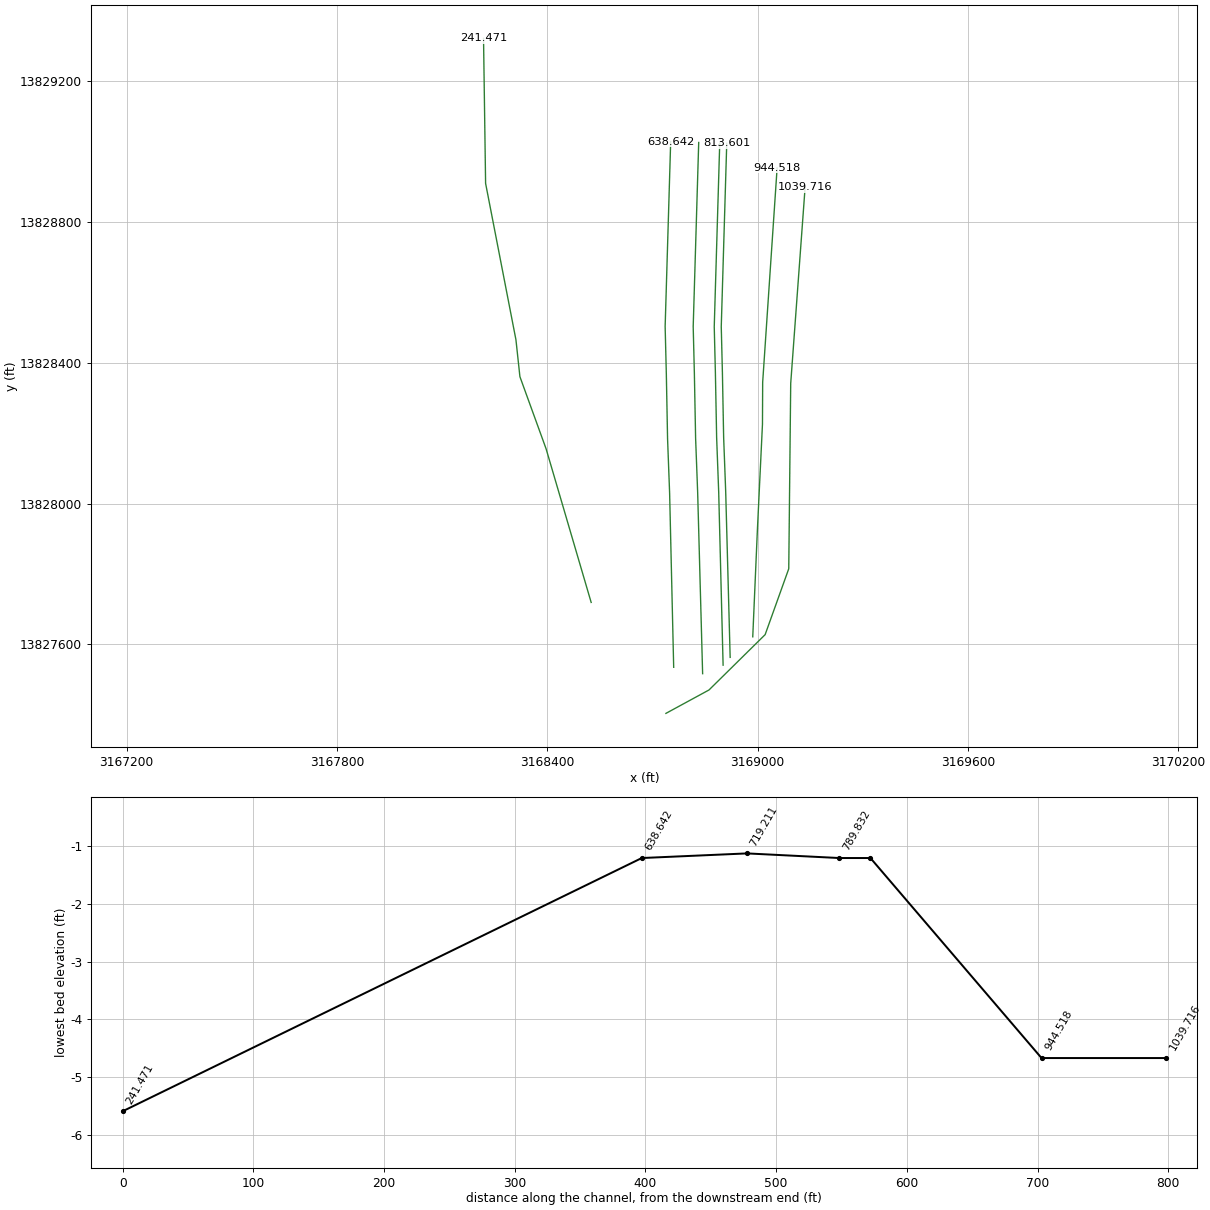
HEC-RAS study I101-00-00.prj: I101-00-00

--- I101-00-00.g02 (geometry) --- (continued)

Type RM Length L Ch R = 3 ,1065    ,,,
BEGIN DESCRIPTION:
RR BRIDGE
END DESCRIPTION:
Bridge Culvert--1,0,-1,-1, 0
Deck Dist Width WeirC Skew NumUp NumDn MinLoCord MaxHiCord MaxSubmerge Is_Ogee
8,25,2.6,0, 13, 13, , , .95, 0, 0,0,,
    4000    4400    4600    4900    4915    4930    4985    5040    5080    5100
    5360    5585    5770
   16.06   16.98   17.15   16.51   17.09   17.07   17.12   17.14   17.01   17.07
   18.64   20.62   21.32
                            14.5    14.5    14.5    14.5    14.5    14.5    14.5
                        
    4000    4400    4600    4900    4915    4930    4985    5040    5080    5100
    5360    5585    5770
   16.06   16.98   17.15   16.51   17.09   17.07   17.12   17.14   17.01   17.07
   18.64   20.62   21.32
                            14.5    14.5    14.5    14.5    14.5    14.5    14.5
                        
Pier Skew, UpSta & Num, DnSta & Num=  ,4915, 2 ,4915, 2 , 0 , 0 , 0 ,,
       1       1
      -5      15
       1       1
      -5      15
Pier Skew, UpSta & Num, DnSta & Num=  ,4930, 2 ,4930, 2 , 0 , 0 , 0 ,,
       1       1
      -5      15
       1       1
      -5      15
Pier Skew, UpSta & Num, DnSta & Num=  ,4945, 2 ,4945, 2 , 0 , 0 , 0 ,,
       1       1
      -5      15
       1       1
      -5      15
Pier Skew, UpSta & Num, DnSta & Num=  ,4960, 2 ,4960, 2 , 0 , 0 , 0 ,,
       1       1
      -5      15
       1       1
      -5      15
Pier Skew, UpSta & Num, DnSta & Num=  ,4975, 2 ,4975, 2 , 0 , 0 , 0 ,,
       1       1
      -5      15
       1       1
      -5      15
Pier Skew, UpSta & Num, DnSta & Num=  ,4990, 2 ,4990, 2 , 0 , 0 , 0 ,,
       1       1
      -5      15
       1       1
      -5      15
Pier Skew, UpSta & Num, DnSta & Num=  ,5005, 2 ,5005, 2 , 0 , 0 , 0 ,,
       1       1
      -5      15
       1       1
      -5      15
Pier Skew, UpSta & Num, DnSta & Num=  ,5020, 2 ,5020, 2 , 0 , 0 , 0 ,,
       1       1
      -5      15
       1       1
      -5      15
Pier Skew, UpSta & Num, DnSta & Num=  ,5035, 2 ,5035, 2 , 0 , 0 , 0 ,,
       1       1
      -5      15
       1       1
      -5      15
Pier Skew, UpSta & Num, DnSta & Num=  ,5050, 2 ,5050, 2 , 0 , 0 , 0 ,,
       1       1
      -5      15
       1       1
      -5      15
Pier Skew, UpSta & Num, DnSta & Num=  ,5063, 2 ,5063, 2 , 0 , 0 , 0 ,,
       1       1
      -5      15
       1       1
      -5      15
Pier Skew, UpSta & Num, DnSta & Num=  ,5072, 2 ,5072, 2 , 0 , 0 , 0 ,,
       1       1
      -5      15
       1       1
      -5      15
Pier Skew, UpSta & Num, DnSta & Num=  ,5085, 2 ,5085, 2 , 0 , 0 , 0 ,,
       1       1
      -5      15
       1       1
      -5      15
BR Coef=-1 , 1 , 1 ,1.25, 0 ,,,.8,-1,2,0,
WSPro=,,,, 1 ,,,, 0 ,,,, 0 ,,,,-1 ,-1 ,-1 , 0 , 0 , 0 , 0 , 0
BC Design=,, 0 ,, 0 ,,,,,,
BC HTab HWMax=21.65

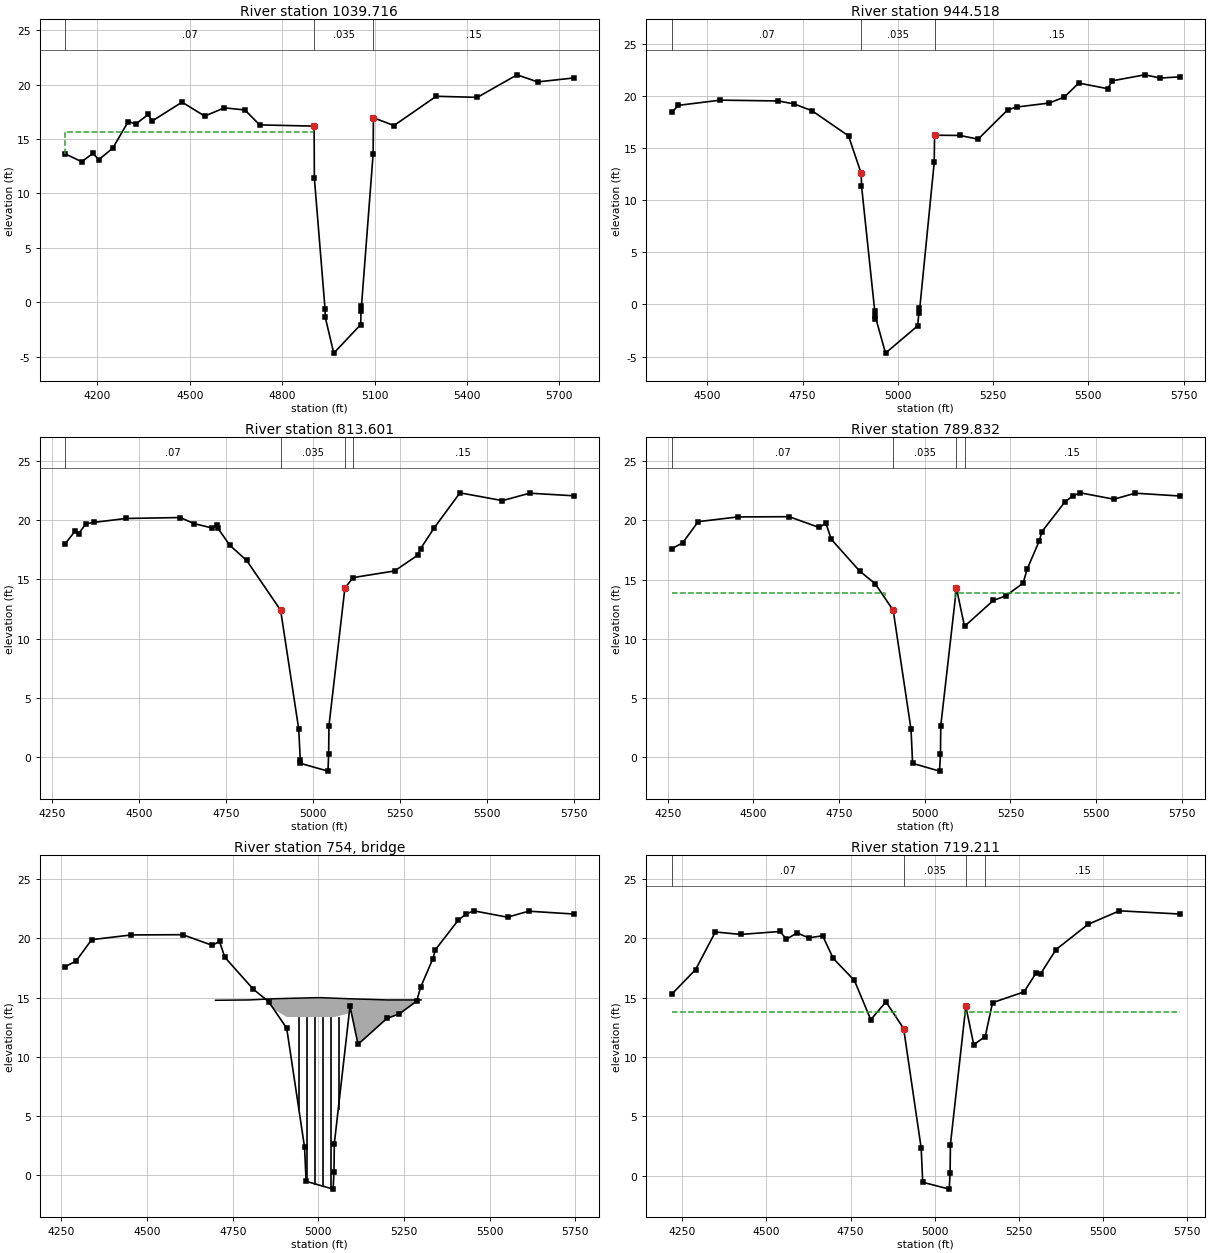
Type RM Length L Ch R = 1 ,1039.716,96.07,95.2,88.55
XS GIS Cut Line= 6
     3168738.501    13827404.128     3168861.343    13827470.584
     3169021.549    13827627.815     3169088.903    13827814.945
     3169094.468    13828341.393     3169135.635    13828899.314
#Sta/Elev= 30
 4095.85   13.63 4149.31   12.91 4185.93   13.68 4204.78    13.1 4250.34   14.16
 4300.42    16.6 4324.66   16.37 4366.02   17.26 4377.07   16.63 4475.07   18.38
 4548.72    17.1 4612.61   17.86 4679.03   17.66 4727.29   16.29 4903.78   16.18
 4904.53   11.41 4939.22    -.61 4939.88   -1.37 4967.52   -4.67    5055   -2.05
 5056.23    -.31 5056.26    -.79 5095.35   13.64 5096.22   16.95 5162.89   16.23
 5300.09   18.92 5433.51   18.82 5562.44   20.89 5629.26   20.24 5745.78    20.6
#Mann= 3 ,-1 , 0
 4095.85     .07       0 4903.78    .035       0 5096.22     .15       0
#XS Ineff= 2 , 0
       0 4903.78    15.6 5096.22       0      16
Permanent Ineff=
       F       F
Bank Sta=4903.78,5096.22
XS Rating Curve= 0
Exp/Cntr=.5,.3

Type RM Length L Ch R = 1 ,944.518 ,93.18,130.92,137.35
XS GIS Cut Line= 5
     3168986.199    13827621.619      3168999.48    13827926.255
      3169013.92    13828225.776     3169014.482     13828344.53
     3169055.714    13828953.473
#Sta/Elev= 30
 4406.42   18.44 4424.05   19.12 4534.32   19.62 4686.53   19.54 4727.29   19.26
 4774.76    18.6 4870.43   16.19 4903.78   12.58 4904.53   11.41 4939.22    -.61
 4939.88   -1.37 4940.08   -1.06 4967.52   -4.67    5052   -2.05 5056.23    -.31
 5056.26    -.79 5095.35   13.64 5096.22   16.25 5162.89   16.23 5210.42   15.87
  5288.5    18.7 5312.58   18.96 5396.84   19.34  5437.1   19.92 5474.57   21.26
 5550.27   20.72 5563.09   21.48 5647.92   22.05  5688.9   21.74 5740.31   21.86
#Mann= 3 ,-1 , 0
 4406.42     .07       0 4903.78    .035       0 5096.22     .15       0
Bank Sta=4903.78,5096.22
XS Rating Curve= 0
Exp/Cntr=.3,.1

Type RM Length L Ch R = 1 ,813.601 ,21.01,23.77,20.28
XS GIS Cut Line= 6
     3168921.757    13827563.219     3168909.011    13828034.027
     3168903.176    13828187.594     3168899.628    13828372.098
     3168896.351    13828502.365     3168912.002    13829023.313
#Sta/Elev= 30
 4288.65   18.03 4316.23   19.06 4327.24   18.88 4347.98   19.71 4371.21   19.83
 4463.44   20.16 4619.24   20.24 4658.27   19.73 4710.42   19.36 4725.67    19.6
 4726.97   19.35 4761.51    17.9 4810.05   16.61 4907.67    12.4 4959.75    2.33
 4964.15    -.27 4964.29    -.55  5043.7   -1.21 5045.66     .23 5046.54    2.63
 5092.33   14.27  5115.8   15.16 5234.92   15.72  5302.4   17.07 5309.61    17.6
 5348.54   19.35 5423.03   22.33 5545.14   21.67 5623.14    22.3 5749.34   22.08
#Mann= 4 ,-1 , 0
 4288.65     .07       0 4907.67    .035       0 5092.33     .07       0
  5115.8     .15       0
Bank Sta=4907.67,5092.33
XS Rating Curve= 0
Exp/Cntr=.5,.3

Type RM Length L Ch R = 1 ,789.832 ,62.66,70.62,60.85
XS GIS Cut Line= 6
     3168901.619    13827541.067      3168889.02      13828033.4
     3168883.183    13828187.022     3168879.633    13828371.654
     3168876.344    13828502.414     3168892.011    13829023.914
#Sta/Elev= 30
 4261.25   17.62  4292.9   18.09  4338.5    19.9 4454.12    20.3 4604.01   20.32
 4690.38   19.42  4711.6   19.75 4726.97   18.41 4810.05   15.71 4855.12   14.65
 4907.67    12.4 4959.75    2.33 4964.29    -.55    5043   -1.21 5045.66     .23
 5046.54    2.63 5092.33   14.27  5115.8   11.04 5199.73   13.23 5236.26   13.62
 5286.98    14.7 5298.26   15.86 5334.06   18.28 5341.81   19.06 5408.86   21.57
 5431.34   22.07 5453.46   22.34 5551.98    21.8 5613.86   22.31 5744.68   22.07
#Mann= 4 ,-1 , 0
 4261.25     .07       0 4907.67    .035       0 5092.33     .07       0
  5115.8     .15       0
#XS Ineff= 2 , 0
       0    4885    13.9    5089       0    13.9
Permanent Ineff=
       F       F
Bank Sta=4907.67,5092.33
XS Rating Curve= 0
Exp/Cntr=.5,.3

Type RM Length L Ch R = 3 ,754     ,,,
BEGIN DESCRIPTION:
UNNAMED ROAD
END DESCRIPTION:
Bridge Culvert--1,0,-1,-1, 0
Deck Dist Width WeirC Skew NumUp NumDn MinLoCord MaxHiCord MaxSubmerge Is_Ogee
8,43,2.6,0, 8, 8, , , .95, 0, 0,0,,
    4700    4800    4870    4990    5010    5090    5200    5300
   14.77    14.8    14.9   14.99   14.99    14.9    14.8    14.8
                   13.35   13.35   13.35   13.35
    4700    4800    4870    4990    5010    5090    5200    5300
   14.77    14.8    14.9   14.99   14.99    14.9    14.8    14.8
                   13.35   13.35   13.35   13.35
Pier Skew, UpSta & Num, DnSta & Num=  ,4943, 4 ,4943, 4 , 3 , 3 , 0 ,,
     1.5     1.5       2       2
      -2   11.35   11.35      14
     1.5     1.5       2       2
      -2   11.35   11.35      14
Pier Skew, UpSta & Num, DnSta & Num=  ,4966, 4 ,4966, 4 , 3 , 3 , 0 ,,
     1.5     1.5       2       2
      -2   11.35   11.35      14
     1.5     1.5       2       2
      -2   11.35   11.35      14
Pier Skew, UpSta & Num, DnSta & Num=  ,4989, 4 ,4989, 4 , 3 , 3 , 0 ,,
     1.5     1.5       2       2
      -2   11.35   11.35      14
     1.5     1.5       2       2
      -2   11.35   11.35      14
Pier Skew, UpSta & Num, DnSta & Num=  ,5012, 4 ,5012, 4 , 3 , 3 , 0 ,,
     1.5     1.5       2       2
      -2   11.35   11.35      14
     1.5     1.5       2       2
      -2   11.35   11.35      14
Pier Skew, UpSta & Num, DnSta & Num=  ,5035, 4 ,5035, 4 , 3 , 3 , 0 ,,
     1.5     1.5       2       2
      -2   11.35   11.35      14
     1.5     1.5       2       2
      -2   11.35   11.35      14
Pier Skew, UpSta & Num, DnSta & Num=  ,5058, 4 ,5058, 4 , 3 , 3 , 0 ,,
     1.5     1.5       2       2
      -2   11.35   11.35      14
     1.5     1.5       2       2
      -2   11.35   11.35      14
BR Coef=-1 , 1 , 1 ,1.25, 0 ,,,.8,-1,2,0,
WSPro=,,,, 1 ,,,, 0 ,,,, 0 ,,,,-1 ,-1 ,-1 , 0 , 0 , 0 , 0 , 0
BC Design=,, 0 ,, 0 ,,,,,,
BC HTab HWMax=22.34

Type RM Length L Ch R = 1 ,719.211 ,83.75,80.57,81.13
XS GIS Cut Line= 6
     3168843.219    13827516.901     3168829.048     13828031.52
     3168823.205    13828185.306     3168819.648    13828370.323
     3168816.321     13828502.56     3168832.038    13829025.715
#Sta/Elev= 30
 4218.87   15.29 4289.91   17.37 4348.54   20.54 4423.66   20.33 4540.41   20.58
  4559.8   19.93 4591.24   20.46 4626.01   20.04 4667.08   20.22 4698.69   18.31
 4761.51   16.45 4810.05   13.15 4855.12   14.65 4907.67    12.4 4959.75    2.33
 4964.29    -.55    5043   -1.13 5045.66     .23 5046.54    2.63 5092.33   14.27
  5115.8   11.04    5150   11.73  5171.6   14.58 5265.08   15.49 5300.12   17.04
 5314.25   17.01  5360.2   19.06 5455.16   21.18 5548.58   22.32  5728.3   22.05
#Mann= 4 ,-1 , 0
 4218.87     .07       0 4907.67    .035       0 5092.33     .07       0
    5150     .15       0
#XS Ineff= 2 , 0
       0    4885    13.8    5089       0    13.8
Permanent Ineff=
       F       F
Bank Sta=4907.67,5092.33
XS Rating Curve= 0
Exp/Cntr=.5,.3

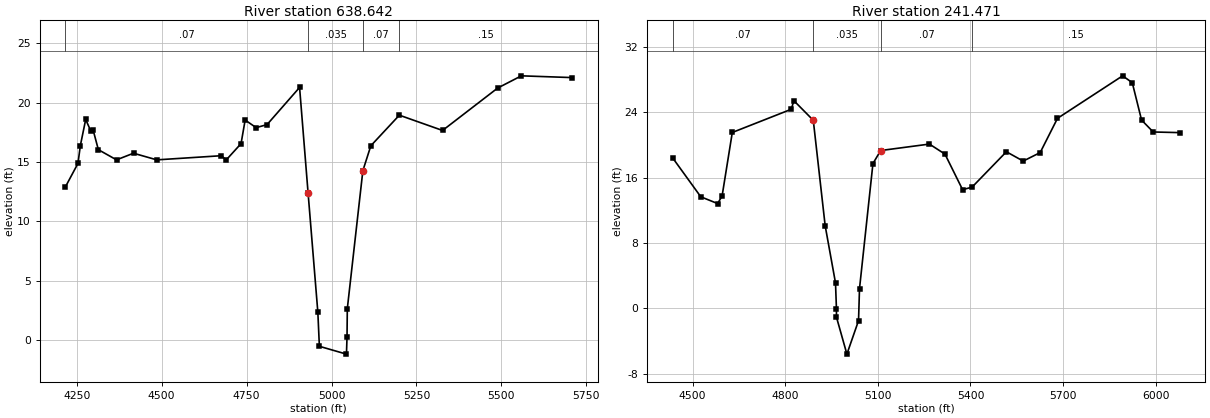
Type RM Length L Ch R = 1 ,638.642 ,312.64,397.17,454.66
XS GIS Cut Line= 6
     3168760.653    13827535.026     3168749.086    13828029.012
     3168743.234    13828183.018     3168739.667    13828368.548
     3168736.291    13828502.756     3168752.074    13829028.118
#Sta/Elev= 30
 4215.84   12.86 4253.52   14.88  4260.6   16.39 4276.33   18.59 4290.84   17.64
 4298.54   17.66 4313.57   16.04 4367.05   15.18 4417.06   15.74 4485.61   15.18
 4675.63   15.53 4689.91   15.17 4733.67   16.55 4745.74   18.54    4778    17.9
 4810.05   18.15    4906   21.29    4931    12.4 4959.75    2.33 4964.29    -.55
    5044   -1.21 5045.66     .23 5046.54    2.63 5092.33   14.27  5115.8   16.37
 5199.73   18.95 5326.95   17.66 5489.23   21.24 5559.01   22.27 5709.49   22.12
#Mann= 4 ,-1 , 0
 4215.84     .07       0    4931    .035       0 5092.33     .07       0
 5199.73     .15       0
Bank Sta=4931,5092.33
XS Rating Curve= 0
Exp/Cntr=.3,.1

Type RM Length L Ch R = 1 ,241.471 ,288.95,241.47,250.03
XS GIS Cut Line= 6
     3168525.269    13827719.244     3168396.761    13828155.369
     3168322.014    13828360.446     3168310.682    13828465.276
     3168224.126    13828909.554     3168218.241    13829321.482
#Sta/Elev= 30
 4435.64   18.41 4526.57   13.66 4581.13   12.83 4595.62   13.77  4628.6   21.53
  4819.6   24.37    4828   25.42 4890.86   23.02 4929.36   10.12 4962.84    3.12
 4965.93     -.1 4965.95   -1.06 4999.74   -5.59 5037.43   -1.49 5040.55    2.42
 5084.09   17.73 5109.14   19.32 5266.99   20.11 5317.37   18.88  5374.4   14.53
    5405   14.84 5516.19   19.17 5570.69   18.03 5625.69   19.07 5681.71   23.26
 5892.67   28.46  5923.9   27.62 5953.99   23.05 5991.66   21.59 6078.62   21.51
#Mann= 4 ,-1 , 0
 4435.64     .07       0 4890.86    .035       0 5109.14     .07       0
    5405     .15       0
Bank Sta=4890.86,5109.14
XS Rating Curve= 0
Exp/Cntr=.3,.1